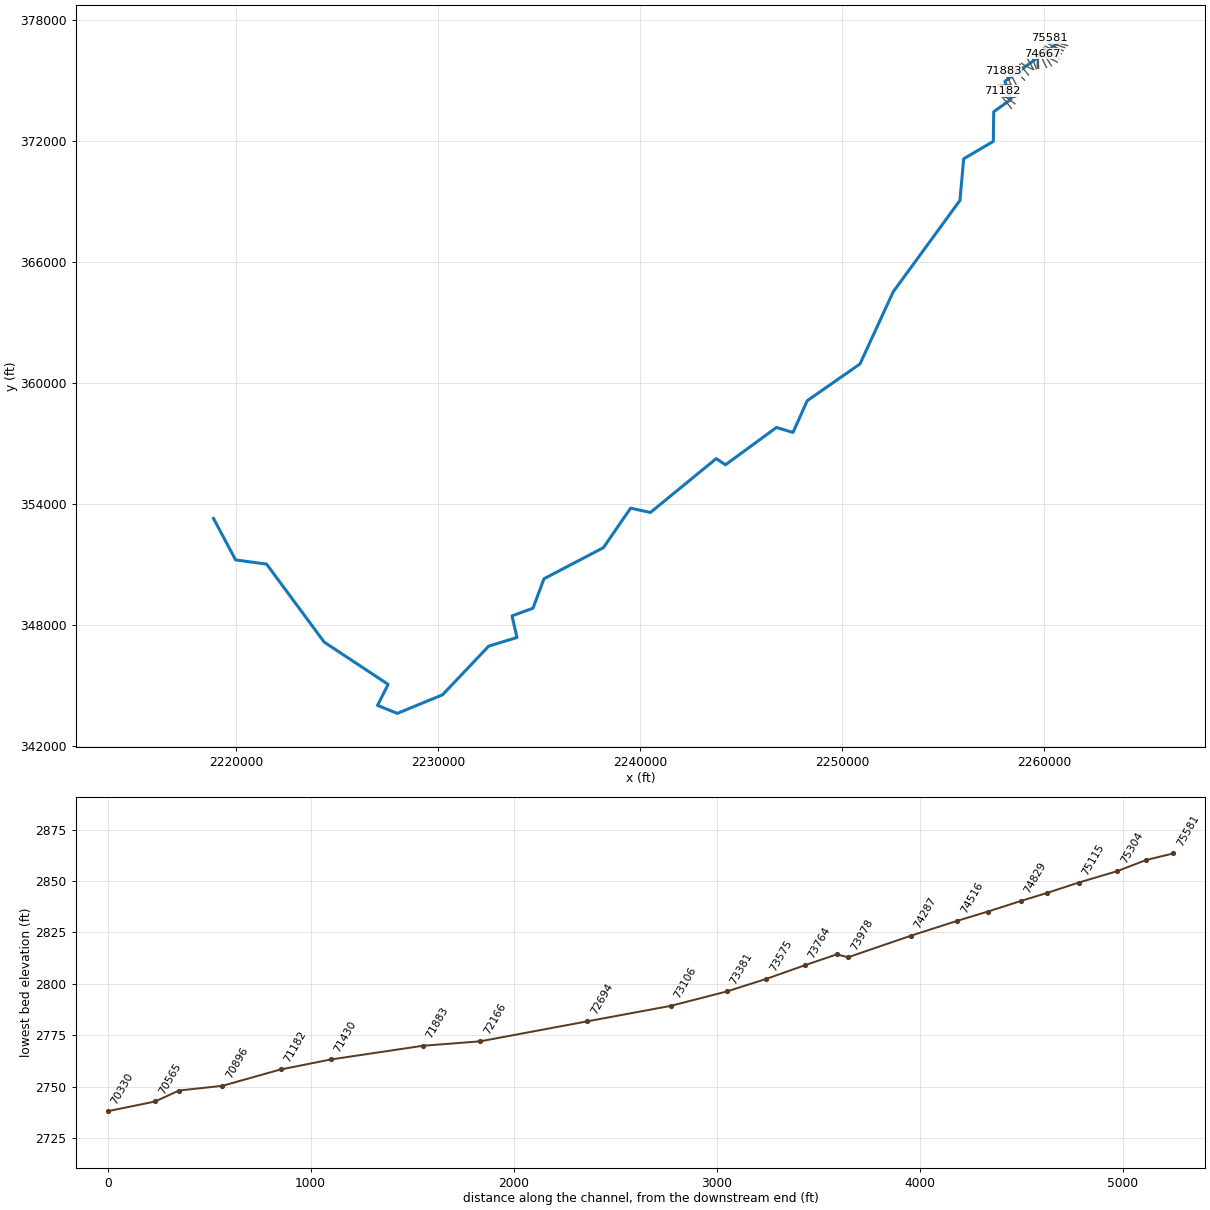
--- MEADOWCK1.prj (project) ---

Proj Title=MEADOWCK1
Current Plan=p01
Default Exp/Contr=0.3,0.1
English Units
Geom File=g01
Flow File=f01
Plan File=p01
Y Axis Title=Elevation
X Axis Title(PF)=Main Channel Distance
X Axis Title(XS)=Station
BEGIN DESCRIPTION:
Stream Name- Meadow Creek 1
Flood Zone: Zone A
Greenbrier County, WV
County-Wide Study
WVDHSEM-2018-3, Flood Risk Project
HEC-RAS Version: 5.0.7
General Notes:
For the Hydrology Regression was used.
END DESCRIPTION:
DSS Export Rating Curves= 0
DSS Export Rating Curve Sorted= 0
DSS Export Volume Flow Curves= 0
DXF Filename=A2c.
DXF OffsetX= 0
DXF OffsetY= 0
DXF ScaleX= 1
DXF ScaleY= 10

--- MEADOWCK1.p01 (plan) ---

Plan Title=Floodplain
Program Version=5.07
Short Identifier=Floodplain
Geom File=g01
Flow File=f01
Subcritical Flow
K Sum by GR= 0
Std Step Tol= 0.01
Critical Tol= 0.01
Num of Std Step Trials= 20
Max Error Tol= 0.3
Flow Tol Ratio= 0.001
Split Flow NTrial= 30
Split Flow Tol= 0.02
Split Flow Ratio= 0.02
Log Output Level= 0
Friction Slope Method= 1
Unsteady Friction Slope Method= 2
Unsteady Bridges Friction Slope Method= 1
Parabolic Critical Depth
Global Vel Dist= 0 , 0 , 0
Global Log Level= 0
CheckData=True
Encroach Param=-1 ,0,0, 0
Computation Interval=1MIN
Output Interval=1HOUR
Instantaneous Interval=1HOUR
Mapping Interval=1HOUR
Computation Time Step Use Courant=        0
Computation Time Step Use Time Series=    0
Computation Time Step Count To Double=0
Computation Time Step Max Doubling=0
Computation Time Step Max Halving=0
Computation Time Step Residence Courant=0
Run HTab= 0
Run UNet= 0
Run Sediment= 0
Run PostProcess= 0
Run WQNet= 0
Run RASMapper= 0
UNET Theta= 1
UNET Theta Warmup= 1
UNET ZTol= 0.02
UNET ZSATol= 0.02
UNET MxIter= 20
UNET Max Iter WO Improvement= 0
UNET MaxInSteps= 0
UNET DtIC= 0
UNET DtMin= 0
UNET MaxCRTS= 20
UNET WFStab= 2
UNET SFStab= 1
UNET WFX= 1
UNET SFX= 1
UNET 1D Methodology=Finite Difference
UNET DSS MLevel= 4
UNET Pardiso=0
UNET DZMax Abort= 100
UNET Use Existing IB Tables=-1
UNET Froude Reduction=False
UNET Froude Limit= 0.8
UNET Froude Power= 4
UNET D1 Cores= 0
UNET D2 Coriolis=0
UNET D2 Cores= 0
UNET D2 Theta= 1
UNET D2 Theta Warmup= 1
UNET D2 Z Tol= 0.01
UNET D2 Volume Tol= 0.01
UNET D2 Max Iterations= 20
UNET D2 Equation= 0
UNET D2 RampUpFraction=0.1
UNET D2 TimeSlices= 1
UNET D2 BCVolumeCheck=0
UNET D1D2 MaxIter= 0
UNET D1D2 ZTol=0.01
UNET D1D2 QTol=0.1
UNET D1D2 MinQTol=1
Write IC File= 0
Write IC File at Fixed DateTime=0
Write IC File at Sim End=0
Echo Input=False
Echo Parameters=False
Echo Output=False
Write Detailed= 0
HDF Write Warmup=0
HDF Write Time Slices=0
HDF Flush=0
HDF Face Node Velocities=0
HDF Compression= 1
HDF Chunk Size= 1
HDF Spatial Parts= 1
HDF Use Max Rows=0
HDF Fixed Rows= 1
Calibration Method= 0
Calibration Iterations= 20
Calibration Max Change=0.05
Calibration Tolerance=0.2
Calibration Maximum=1.5
Calibration Minimum=0.5
Calibration Optimization Method= 1
WQ AD Non Conservative
WQ ULTIMATE=-1
WQ Max Comp Step=1HOUR
WQ Output Interval=15MIN
WQ Output Selected Increments= 0
WQ Output face flow=0
WQ Output face velocity=0
WQ Output face area=0
WQ Output face dispersion=0
WQ Output cell volume=0
WQ Output cell surface area=0
WQ Output cell continuity=0
WQ Output cumulative cell continuity=0
WQ Output face conc=0
WQ Output face dconc_dx=0
WQ Output face courant=0
WQ Output face peclet=0
WQ Output face adv mass=0
WQ Output face disp mass=0
WQ Output cell mass=0
WQ Output cell source sink temp=0
WQ Output nsm pathways=0
WQ Output nsm derived pathways=0
WQ Output MaxMinRange=-1
WQ Daily Max Min Mean=-1
WQ Daily Range=0
WQ Daily Time=0
WQ Create Restart=0
WQ Fixed Restart=0
WQ System Summary=0
WQ Write To DSS=0
WQ Use Fixed Temperature=0
Sorting and Armoring Iterations= 10
XS Update Threshold= 0.02
Bed Roughness Predictor= 0
Hydraulics Update Threshold= 0.02
Energy Slope Method= 1
Volume Change Method= 1
Sediment Retention Method= 0
XS Weighting Method= 0
Number of US Weighted Cross Sections= 1
Number of DS Weighted Cross Sections= 1
Upstream XS Weight=0
Main XS Weight=1
Downstream XS Weight=0
Number of DS XS's Weighted with US Boundary= 1
Upstream Boundary Weight= 1
Weight of XSs Associated with US Boundary= 0
Number of US XS's Weighted with DS Boundary= 1
Downstream Boundary Weight= 0.5
Weight of XSs Associated with DS Boundary= 0.5
Percentile Method= 0
Sediment Output Level= 3
Mass or Volume Output= 0
Output Increment Type= 1
Profile and TS Output Increment= 1
XS Output Flag= 0
XS Output Increment= 10
Write Gradation File= 0
Read Gradation Hotstart= 0
Write HDF5 File= 1
Write Binary Output= 1
Write DSS Sediment File= 0
SV Curve= 0
Specific Gage Flag= 0

--- MEADOWCK1.f01 (steady flow) ---

Flow Title=Flow
Program Version=5.07
Number of Profiles= 6
Profile Names=f1p,f10p,f4p,f2p,f02p,f1pplus
River Rch & RM=MEADOWCK1,Main            ,75581
     529     279     371     448     740     782
River Rch & RM=MEADOWCK1,Main            ,73978
     598     316     420     506     834     884
River Rch & RM=MEADOWCK1,Main            ,71430
     678     361     478     575     945    1000
River Rch & RM=MEADOWCK1,Main            ,69203
     792     424     560     672    1100    1170
River Rch & RM=MEADOWCK1,Main            ,67339
     882     474     625     749    1220    1300
River Rch & RM=MEADOWCK1,Main            ,64109
    1010     548     721     863    1400    1500
River Rch & RM=MEADOWCK1,Main            ,61239
    1140     619     812     971    1570    1690
River Rch & RM=MEADOWCK1,Main            ,59576
    1280     700     917    1090    1770    1900
River Rch & RM=MEADOWCK1,Main            ,56054
    1450     794    1040    1240    1990    2140
River Rch & RM=MEADOWCK1,Main            ,50980
    1720     950    1240    1470    2360    2550
River Rch & RM=MEADOWCK1,Main            ,44209
    1940    1080    1400    1660    2650    2870
River Rch & RM=MEADOWCK1,Main            ,38864
    2190    1220    1580    1870    2980    3230
River Rch & RM=MEADOWCK1,Main            ,31946
    2500    1400    1810    2140    3390    3690
River Rch & RM=MEADOWCK1,Main            ,24140
    2780    1560    2020    2390    3780    4120
River Rch & RM=MEADOWCK1,Main            ,14473
    3730    2120    2720    3210    5030    5510
Boundary for River Rch & Prof#=LAURELRN2,Main            , 1
Up Type= 0
Dn Type= 3
Dn Slope=0.035124
Boundary for River Rch & Prof#=LAURELRN2,Main            , 2
Up Type= 0
Dn Type= 3
Dn Slope=0.035124
Boundary for River Rch & Prof#=LAURELRN2,Main            , 3
Up Type= 0
Dn Type= 3
Dn Slope=0.035124
Boundary for River Rch & Prof#=LAURELRN2,Main            , 4
Up Type= 0
Dn Type= 3
Dn Slope=0.035124
Boundary for River Rch & Prof#=LAURELRN2,Main            , 5
Up Type= 0
Dn Type= 3
Dn Slope=0.035124
Boundary for River Rch & Prof#=LAURELRN2,Main            , 6
Up Type= 0
Dn Type= 3
Dn Slope=0.035124
Boundary for River Rch & Prof#=MEADOWCK1,Main            , 1
Up Type= 0
Dn Type= 3
Dn Slope=0.011297
Boundary for River Rch & Prof#=MEADOWCK1,Main            , 2
Up Type= 0
Dn Type= 3
Dn Slope=0.011297
Boundary for River Rch & Prof#=MEADOWCK1,Main            , 3
Up Type= 0
Dn Type= 3
Dn Slope=0.011297
Boundary for River Rch & Prof#=MEADOWCK1,Main            , 4
Up Type= 0
Dn Type= 3
Dn Slope=0.011297
Boundary for River Rch & Prof#=MEADOWCK1,Main            , 5
Up Type= 0
Dn Type= 3
Dn Slope=0.011297
Boundary for River Rch & Prof#=MEADOWCK1,Main            , 6
Up Type= 0
Dn Type= 3
Dn Slope=0.011297
Boundary for River Rch & Prof#=MFANTNYCK,Main            , 1
Up Type= 0
Dn Type= 3
Dn Slope=0.001473
Boundary for River Rch & Prof#=MFANTNYCK,Main            , 2
Up Type= 0
Dn Type= 3
Dn Slope=0.001473
Boundary for River Rch & Prof#=MFANTNYCK,Main            , 3
Up Type= 0
Dn Type= 3
Dn Slope=0.001473
Boundary for River Rch & Prof#=MFANTNYCK,Main            , 4
Up Type= 0
Dn Type= 3
Dn Slope=0.001473
Boundary for River Rch & Prof#=MFANTNYCK,Main            , 5
Up Type= 0
Dn Type= 3
Dn Slope=0.001473
Boundary for River Rch & Prof#=MFANTNYCK,Main            , 6
Up Type= 0
Dn Type= 3
Dn Slope=0.001473
Boundary for River Rch & Prof#=NFANTNYCK,Main            , 1
Up Type= 0
Dn Type= 3
Dn Slope=0.006644
Boundary for River Rch & Prof#=NFANTNYCK,Main            , 2
Up Type= 0
Dn Type= 3
Dn Slope=0.006644
Boundary for River Rch & Prof#=NFANTNYCK,Main            , 3
Up Type= 0
Dn Type= 3
Dn Slope=0.006644
Boundary for River Rch & Prof#=NFANTNYCK,Main            , 4
Up Type= 0
Dn Type= 3
Dn Slope=0.006644
Boundary for River Rch & Prof#=NFANTNYCK,Main            , 5
Up Type= 0
Dn Type= 3
Dn Slope=0.006644
Boundary for River Rch & Prof#=NFANTNYCK,Main            , 6
Up Type= 0
Dn Type= 3
Dn Slope=0.006644
Boundary for River Rch & Prof#=TWOMILERN,Main            , 1
Up Type= 0
Dn Type= 3
Dn Slope=0.021324
Boundary for River Rch & Prof#=TWOMILERN,Main            , 2
Up Type= 0
Dn Type= 3
Dn Slope=0.021324
Boundary for River Rch & Prof#=TWOMILERN,Main            , 3
Up Type= 0
Dn Type= 3
Dn Slope=0.021324
Boundary for River Rch & Prof#=TWOMILERN,Main            , 4
Up Type= 0
Dn Type= 3
Dn Slope=0.021324
Boundary for River Rch & Prof#=TWOMILERN,Main            , 5
Up Type= 0
Dn Type= 3
Dn Slope=0.021324
Boundary for River Rch & Prof#=TWOMILERN,Main            , 6
Up Type= 0
Dn Type= 3
Dn Slope=0.021324
DSS Import GetInterval= 0
DSS Import GetPeak= 0
DSS Import FillOption= 0

--- MEADOWCK1.g01 (geometry) ---

Geom Title=Geometry
Program Version=5.07

River Reach=MEADOWCK1       ,Main
Reach XY= 30
2260734.90560606376864.4507299812258071.48540796374944.584819064
 2258373.9841468374052.8352902232257518.56722248373437.835207894
 2257496.7299958371967.9975963982256030.55018538371106.775237471
2255845.04104197 369043.663221972252537.49549171 364509.62209323
2250894.70842297360936.0675605542248280.36325797359114.362542555
2247574.76690014357540.1357041452246757.87319273357789.033500314
2244231.69222148355938.2734223162243774.74792539356245.217690304
2240513.63666546353574.3844493032239533.08121188353789.662233979
2238187.24794555 351831.328880312235241.41459839350288.967791811
2234698.35892597348830.6344223922233659.15988889348449.135185391
2233903.91464873347378.5510404712232503.91449597346949.384575978
2230215.02570106 344536.189927312227978.91468772343616.745571971
2226997.20109998 344011.42785348 2227523.2426988345054.657066226
2224355.18702705347149.7959205662221503.79837289351014.379398733
2219966.94908439351223.2546371372218873.18224305353280.180313304

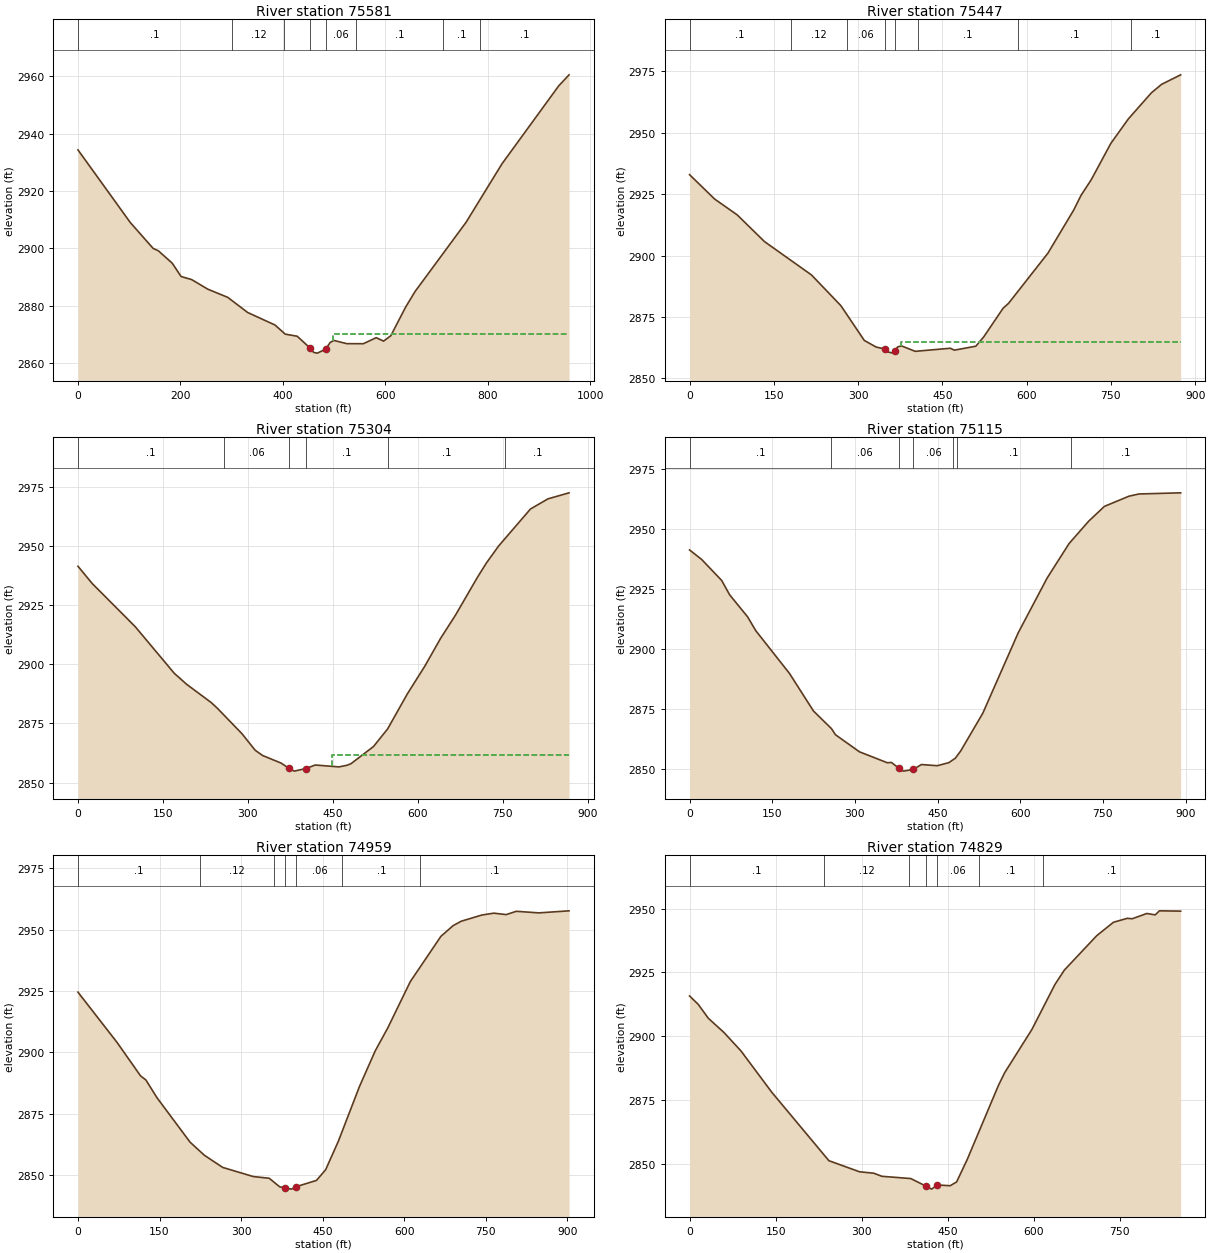
Type RM Length L Ch R = 1 ,75581   ,131.2,133.7,135.5
XS GIS Cut Line= 4
2261175.92211246376713.2617278992260854.58515672376806.768758729
 2260576.6687178 376929.685507642260292.24146514377076.109099314
#Sta/Elev= 30
       0 2934.32   102.2 2908.98   146.7 2899.98   156.9 2899.14     184 2894.82
   201.3 2890.17   221.8 2889.11   253.4 2885.76   292.5 2882.89   331.2 2877.63
   384.6 2873.26   404.5 2870.08   427.9 2869.35   452.32865.346   460.1  2863.7
   467.3 2863.46  483.412864.858   492.4  2867.2   499.6 2867.88   524.7 2866.76
     557 2866.74   582.1 2868.85   596.5 2867.64   610.6 2869.53   639.5 2879.49
     658 2884.95   757.7 2909.13   827.7 2929.49   938.4 2956.66   958.5 2960.49
#Mann= 8 ,-1 , 0
       0      .1       0  301.28     .12       0  403.07     .06       0
   452.3    .045       0  483.41     .06       0  542.83      .1       0
  712.32      .1       0  784.42      .1       0
#XS Ineff= 2 , 0
                          498.24         2870.07
Permanent Ineff=
       F       F
Bank Sta=452.3,483.41
XS Rating Curve= 0 ,0
Exp/Cntr=0.3,0.1

Type RM Length L Ch R = 1 ,75447   ,144.1,143,145.3
XS GIS Cut Line= 2
2261036.21733938376613.4354839772260212.60612573 376906.49100022
#Sta/Elev= 30
       0 2932.96    44.6 2923.04    84.8 2916.58   133.5 2905.68   217.1  2892.1
   269.3 2879.62   311.1 2865.43     332 2862.76  348.042861.916   352.9 2860.76
   362.2 2860.27  365.852861.288   370.3 2862.79   377.3 2863.22   401.7    2861
   464.3 2862.26   471.3 2861.48   509.6 2863.09   523.5 2866.83   558.2 2878.57
   567.7 2880.51   637.9 2900.97   683.7 2918.49   696.9 2924.53   715.1 2930.92
   749.9 2945.68   781.2 2955.69   822.2 2966.31   840.4 2969.76   874.2 2973.62
#Mann= 8 ,-1 , 0
       0      .1       0  180.05     .12       0  281.02     .06       0
  348.04    .045       0  365.85     .06       0  406.73      .1       0
  583.95      .1       0   785.9      .1       0
#XS Ineff= 2 , 0
                          377.17         2864.69
Permanent Ineff=
       F       F
Bank Sta=348.04,365.85
XS Rating Curve= 0 ,0
Exp/Cntr=0.3,0.1

Type RM Length L Ch R = 1 ,75304   ,188.1,189.3,186.3
XS GIS Cut Line= 2
2260962.60626614376456.4909159842260177.88375422376824.546610311
#Sta/Elev= 30
       0 2941.41      25 2934.15   101.1 2915.86     170 2896.16   191.7 2891.54
   235.2  2883.8   246.1 2881.38   289.6  2870.6   312.7 2863.67   325.8 2861.44
   358.4 2858.24  372.832855.948   381.7 2854.83   402.32855.927   418.7 2857.41
   460.7 2856.62   474.4 2857.28   481.6 2857.93   521.5 2865.21   546.4 2872.63
   581.5 2887.54   612.1 2899.17   640.1 2910.98   666.4 2920.79   704.9 2936.69
   720.8 2942.77   742.5 2949.99   798.6 2965.59   829.5 2969.88   866.7 2972.43
#Mann= 6 ,-1 , 0
       0      .1       0  257.18     .06       0  372.83    .045       0
   402.3      .1       0  547.87      .1       0  754.44      .1       0
#XS Ineff= 2 , 0
                          448.22         2861.46
Permanent Ineff=
       F       F
Bank Sta=372.83,402.3
XS Rating Curve= 0 ,0
Exp/Cntr=0.3,0.1

Type RM Length L Ch R = 1 ,75115   ,155.7,155.2,153.3
XS GIS Cut Line= 2
2260877.88399464376306.4908878952260070.93941431 376684.26867564
#Sta/Elev= 30
       0  2941.4      22 2937.43    58.3 2928.68    72.7 2922.72   105.3 2913.55
     120 2907.82   181.4 2889.94   224.9 2874.31   257.5 2866.98   264.7 2864.45
   308.2 2857.34   358.9 2852.77   366.2 2852.91  379.472850.566   387.9 2849.29
  406.192849.981   420.5 2852.03   449.5 2851.55   470.4 2852.82   482.1 2854.65
   491.9 2857.67   532.1 2873.43   596.2 2906.84   648.7 2929.67   688.6 2944.06
     724 2953.34   752.7 2959.54   797.3 2963.78   815.4  2964.7     891 2965.18
#Mann= 7 ,-1 , 0
       0      .1       0  257.37     .06       0  379.47    .045       0
  406.19     .06       0  478.51      .1       0  485.79      .1       0
  692.32      .1       0
Bank Sta=379.47,406.19
XS Rating Curve= 0 ,0
Exp/Cntr=0.3,0.1

Type RM Length L Ch R = 1 ,74959   ,129.8,130.8,131
XS GIS Cut Line= 2
 2260779.2726433376155.1020830572259988.99502438376592.602192312
#Sta/Elev= 30
       0 2924.55    71.8 2904.09   115.2 2890.41   124.9 2888.77   145.4 2881.51
   206.3 2863.38   232.6 2858.05   266.3  2853.1   322.6 2849.38   351.8 2848.69
   371.1  2845.2  381.612844.726   392.8 2844.26  401.752845.287   438.7 2847.81
   455.6 2852.18     479  2863.8   517.6 2885.98   546.7 2900.59   570.1 2910.08
   611.3 2928.85   667.6  2947.3   690.1 2951.67   705.1 2953.47   742.8 2955.98
   765.1 2956.75   787.6 2956.16   806.3 2957.51   847.6 2956.86   903.3  2957.7
#Mann= 7 ,-1 , 0
       0      .1       0  223.87     .12       0  360.15     .06       0
  381.61    .045       0  401.75     .06       0  486.26      .1       0
  629.89      .1       0
Bank Sta=381.61,401.75
XS Rating Curve= 0 ,0
Exp/Cntr=0.3,0.1

Type RM Length L Ch R = 1 ,74829   ,161.8,161.7,161
XS GIS Cut Line= 3
 2260766.7726683376063.4352716512260413.99515864376212.046522975
2259988.01110247376417.601886138
#Sta/Elev= 30
       0 2915.82      15 2912.56    32.8 2907.07    59.8 2901.57    89.8 2894.27
   143.2  2878.2   242.8 2851.41   296.2 2847.07   321.2 2846.51   335.1 2845.31
   385.5 2844.42  411.962841.474   421.7 2840.29  432.072841.914   454.2 2841.62
   465.4 2843.11   483.7 2851.79   538.3 2880.85   549.2 2885.84   596.6 2902.72
   636.7 2920.29   653.2 2925.94   709.5 2939.37   738.7 2944.63   762.9 2946.17
   771.4    2946   796.9 2948.06   811.5 2947.52   818.8  2949.1   855.8 2948.98
#Mann= 7 ,-1 , 0
       0      .1       0  234.13     .12       0  382.24     .06       0
  411.96    .045       0  432.07     .06       0  504.38      .1       0
  615.58      .1       0
Bank Sta=411.96,432.07
XS Rating Curve= 0 ,0
Exp/Cntr=0.3,0.1

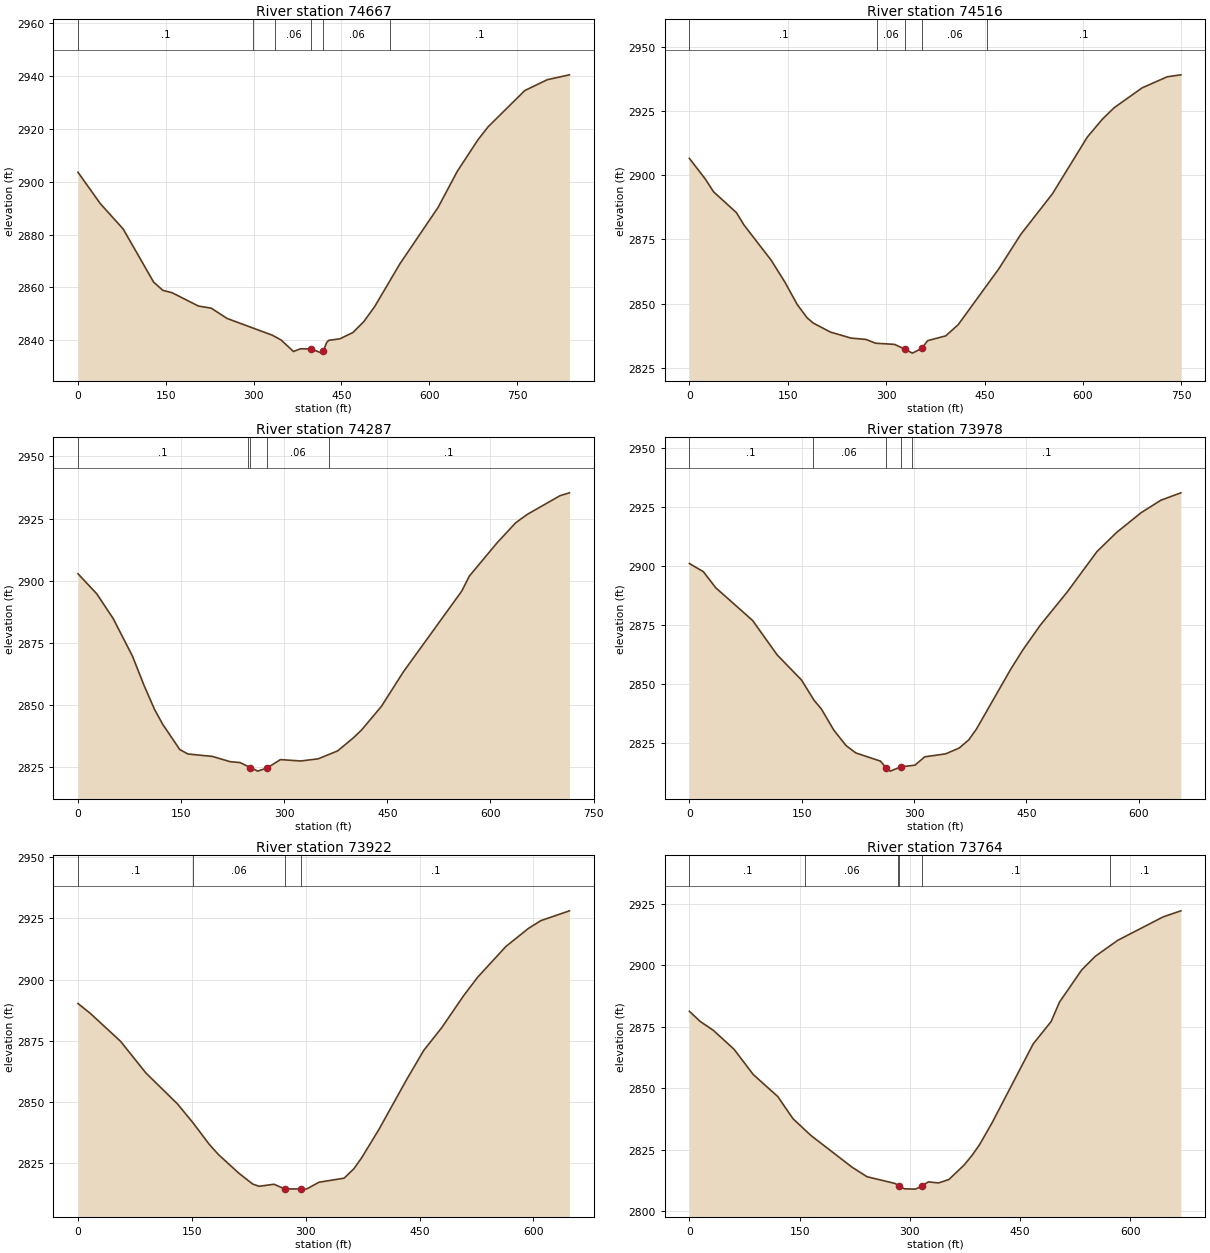
Type RM Length L Ch R = 1 ,74667   ,155.3,150.6,144.9
XS GIS Cut Line= 3
2260665.09439397 375896.421498062260134.57019256376179.812991649
2259941.48330839376318.643750727
#Sta/Elev= 30
       0 2903.54      38  2891.7    77.2 2882.08   129.2 2862.01   144.9  2858.9
   160.8 2857.99   205.4 2852.99   227.7 2852.15   254.5 2848.29   331.6 2841.97
   346.7 2840.17     368 2835.79   380.1 2836.82  398.662836.732   416.5 2835.17
  418.862835.994   424.9 2839.28   428.5 2840.02   447.2 2840.57   469.5 2842.95
   488.1 2847.08   506.7 2852.77   549.8 2868.94   614.9 2890.22     648 2903.97
     683 2915.78   700.5 2920.73     763  2934.4   801.6 2938.52   839.3 2940.35
#Mann= 6 ,-1 , 0
       0      .1       0  298.32     .12       0  336.81     .06       0
  398.66    .045       0  418.86     .06       0  533.29      .1       0
Bank Sta=398.66,418.86
XS Rating Curve= 0 ,0
Exp/Cntr=0.3,0.1

Type RM Length L Ch R = 1 ,74516   ,229.9,229.3,226.9
XS GIS Cut Line= 3
2260378.98341763375713.0882033112260115.09450972376128.365916058
2259934.53909655376311.699210808
#Sta/Elev= 30
       0 2906.56    24.6 2898.41    36.7 2893.58    71.7 2885.43    83.3 2880.59
   124.7 2866.87   145.5 2858.38   164.4 2849.62   179.3 2844.48   188.8 2842.38
     215 2838.87   246.6 2836.51   269.2    2836   283.9 2834.52   312.7 2834.07
  327.992832.288   339.9 2830.66  354.262832.496   363.2 2835.51   390.9 2837.39
   409.9 2841.77   471.7  2863.5   505.2 2876.92   553.4 2892.72   606.7 2914.87
   629.9 2921.91   647.9 2926.36   690.2 2934.04   728.5 2938.36   749.3 2939.13
#Mann= 5 ,-1 , 0
       0      .1       0  286.28     .06       0  327.99    .045       0
  354.26     .06       0  454.36      .1       0
Bank Sta=327.99,354.26
XS Rating Curve= 0 ,0
Exp/Cntr=0.3,0.1

Type RM Length L Ch R = 1 ,74287   ,312.5,308.9,301.6
XS GIS Cut Line= 2
2260135.92780139375631.1438133872259817.87233514376271.421404228
#Sta/Elev= 30
       0  2902.8    27.2 2894.77    51.1 2884.83    79.2 2869.69    96.3 2857.74
   111.4  2848.2   123.2 2842.26     148 2832.08   159.9 2830.29   195.7  2829.3
   221.3  2827.2     236 2826.83  250.572824.805   261.6 2823.39  275.472824.709
   294.5 2828.03     324 2827.47   349.5 2828.35   377.8 2831.54   400.8 2836.84
   412.5 2839.94   441.4 2849.45   473.2 2863.28   558.3 2895.85   569.3 2901.87
   609.6 2915.23   636.8 2923.33   653.6 2926.69   701.2 2934.21   714.9 2935.36
#Mann= 5 ,-1 , 0
       0      .1       0  246.66     .06       0  250.57    .045       0
  275.47     .06       0  364.51      .1       0
Bank Sta=250.57,275.47
XS Rating Curve= 0 ,0
Exp/Cntr=0.3,0.1

Type RM Length L Ch R = 1 ,73978   ,56.8,55.9,54.6
XS GIS Cut Line= 2
 2259741.4833803375590.8660068062259715.09465355376246.421454221
#Sta/Elev= 30
       0 2900.92    18.7 2897.44    35.1 2890.67    84.4 2876.77   117.2 2862.18
   149.6 2851.57   166.4 2842.98   176.3 2839.22   192.7 2830.35   209.1 2823.77
   222.2 2820.63   255.1 2817.16  262.482814.377   268.2 2812.92  282.532814.748
   301.1 2815.44   314.2 2818.99   342.1 2820.24   360.2 2822.71   372.9 2826.16
   383.2 2830.73   429.1 2856.18   445.5 2864.44   468.4 2874.76   504.6 2888.93
   544.1 2905.97   570.3 2914.07   603.1 2922.47   629.4 2927.74   656.1 2930.88
#Mann= 5 ,-1 , 0
       0      .1       0  164.51     .06       0  262.48    .045       0
  282.53     .06       0  297.28      .1       0
Bank Sta=262.48,282.53
XS Rating Curve= 0 ,0
Exp/Cntr=0.3,0.1

Type RM Length L Ch R = 1 ,73922   ,152.4,158.7,163.4
XS GIS Cut Line= 4
2259694.67817603375596.5903590752259666.78081495375767.461695682
2259684.21666562375961.3483551782259680.72949549376241.019399992
#Sta/Elev= 30
       0 2890.22    16.4 2886.14    56.3 2874.69    89.4 2861.84   131.1 2849.14
   151.4  2841.5   172.8 2832.68     185 2828.46   212.2 2820.75   230.3 2816.36
   238.6 2815.46   258.3  2816.3   272.42814.373   294.2 2814.38   297.9  2814.3
   301.2 2814.35   317.6 2817.13   350.6 2818.78   363.3 2822.56   373.6 2827.05
   396.6 2838.76   432.6  2858.9   455.6 2871.07   479.2 2880.32   508.1 2893.43
   526.6 2900.99   563.9 2913.59   593.4 2920.92   609.8 2924.11   647.5 2928.13
#Mann= 4 ,-1 , 0
       0      .1       0   151.4     .06       0   272.4    .045       0
   294.2      .1       0
Bank Sta=272.4,294.2
XS Rating Curve= 0 ,0
Exp/Cntr(USF)=0,0
Exp/Cntr=0.3,0.1

Type RM Length L Ch R = 1 ,73764   ,187,189,190.6
XS GIS Cut Line= 2
2259622.03906539375568.6436103142259399.81674081376199.199107721
#Sta/Elev= 30
       0 2881.34    14.8  2877.2    32.5 2873.61    60.7 2865.92    86.8 2855.64
   120.3 2846.64   140.9 2837.65   165.1 2830.88   221.1 2817.95   241.6 2814.03
   279.9 2811.28  285.122810.144   292.6 2809.11   307.7 2808.98   315.8 2810.15
   325.1 2811.93     339  2811.5     353 2812.88   373.8  2818.8   384.3 2822.63
   394.7 2827.04   412.1 2836.15   467.7 2868.06   492.1 2877.18   503.5 2885.08
   533.8 2898.21   552.4 2903.77   582.5 2910.18   644.5 2919.76   668.6 2922.23
#Mann= 6 ,-1 , 0
       0      .1       0  157.44     .06       0  284.45      .1       0
  285.12    .045       0   315.8      .1       0  571.56      .1       0
Bank Sta=285.12,315.8
XS Rating Curve= 0 ,0
Exp/Cntr=0.3,0.1

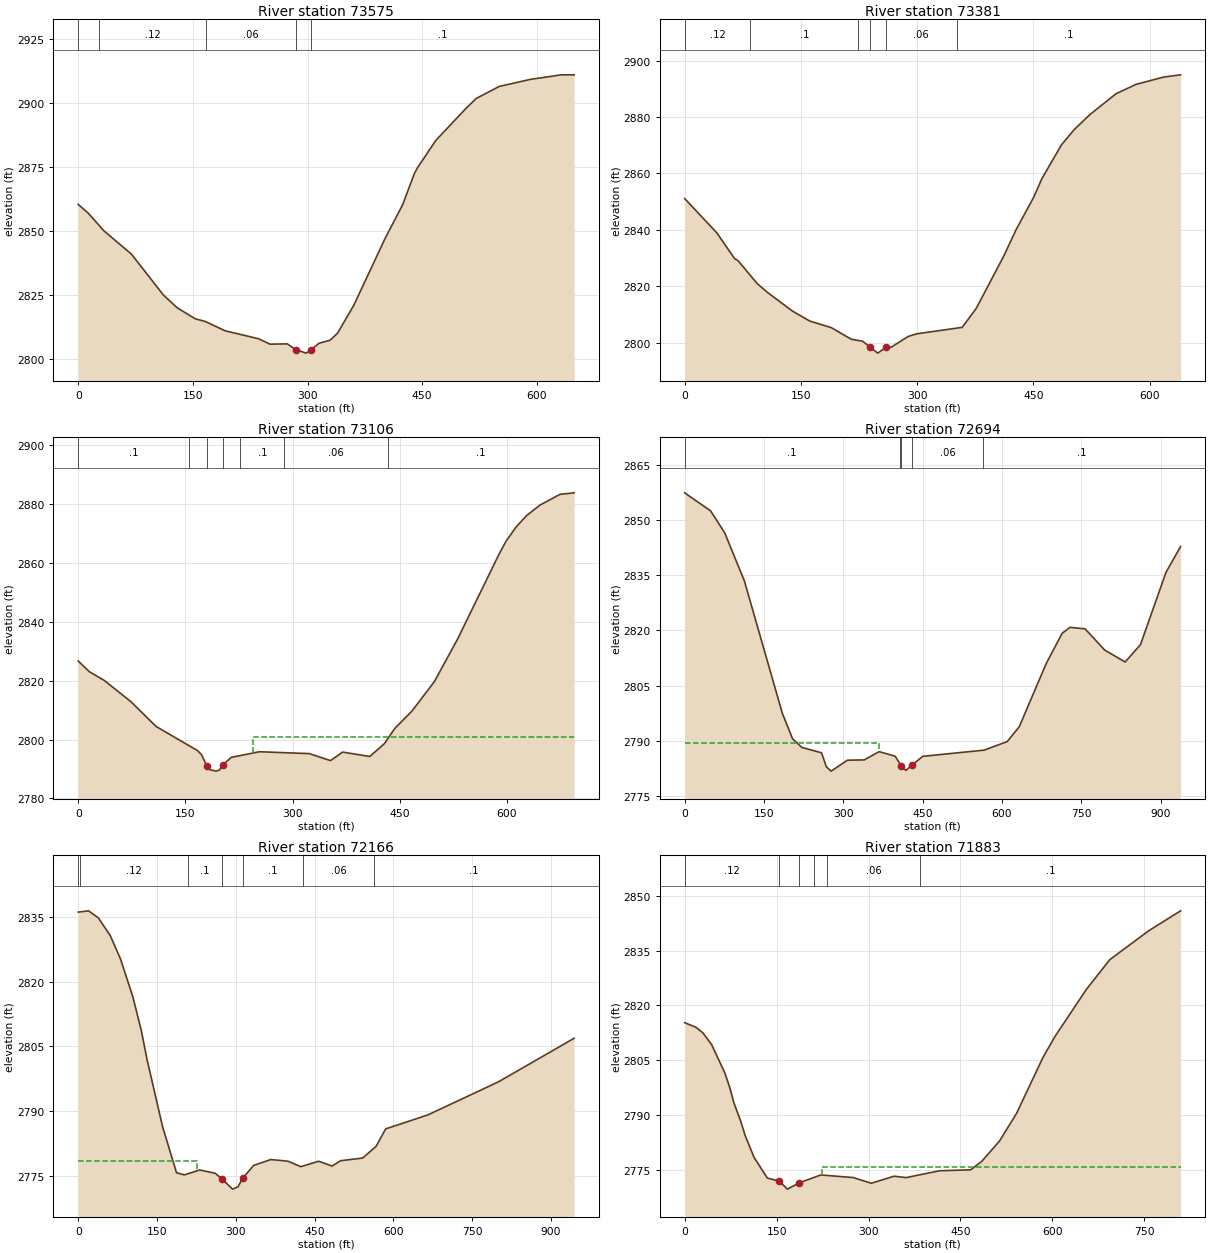
Type RM Length L Ch R = 1 ,73575   ,187.8,194,199.6
XS GIS Cut Line= 2
2259491.48355222 375532.532462062259170.65020439376096.421426147
#Sta/Elev= 30
       0 2860.44    13.1 2857.02    33.6 2850.11    69.7 2841.01   111.2 2825.12
   129.4 2820.08   152.8  2815.8   166.1 2814.72   192.4 2811.06   235.8 2807.99
   250.9 2805.86   273.6 2805.97  284.332803.753   298.3 2802.36  304.382803.634
   315.1 2806.22   329.5  2807.4   339.2 2810.11   360.4 2820.97   401.7 2847.27
   424.5 2860.34   439.6 2872.35   443.4 2874.52   467.7 2885.35   507.6 2898.01
   520.8  2901.8   550.9 2906.49   591.8 2909.25   632.1 2911.01   648.8    2911
#Mann= 5 ,-1 , 0
       0      .1       0   27.57     .12       0  166.94     .06       0
  284.33    .045       0  304.38      .1       0
Bank Sta=284.33,304.38
XS Rating Curve= 0 ,0
Exp/Cntr=0.3,0.1

Type RM Length L Ch R = 1 ,73381   ,280.2,274.9,270.9
XS GIS Cut Line= 3
2259455.37240396 375532.532462062259016.48351797375753.366009891
 2258898.4279798375843.643716484
#Sta/Elev= 30
       0  2851.1    41.5 2838.92    64.3 2829.84    69.1    2829    93.6 2820.92
   107.4 2817.68   139.2 2811.16   161.2 2807.67   189.1 2805.32   214.9 2801.21
   229.6 2800.49  239.552798.336   249.1 2796.27  259.56 2798.31   266.3 2798.35
   288.3 2802.17   299.3 2803.12   358.1 2805.41   376.2 2812.15   412.2 2830.95
   427.5 2839.99   449.9 2851.33   460.9 2858.15   486.1 2870.11   502.7 2875.59
   523.2 2880.96   556.6 2888.28   582.3 2891.59   618.2  2894.2   639.9 2894.98
#Mann= 6 ,-1 , 0
       0     .12       0    84.9      .1       0  224.25     .06       0
  239.55    .045       0  259.56     .06       0  350.79      .1       0
Bank Sta=239.55,259.56
XS Rating Curve= 0 ,0
Exp/Cntr=0.3,0.1

Type RM Length L Ch R = 1 ,73106   ,411.6,411.6,412.7
XS GIS Cut Line= 2
2259244.26127763375253.3660256422258806.76116839375792.254711643
#Sta/Elev= 30
       0 2826.65    15.7    2823    36.6 2820.03    73.7 2812.86   108.9 2804.46
   167.3  2796.2   172.6 2794.85   179.9 2791.11   184.1 2789.78   192.9 2789.28
   197.6 2789.63   202.2 2791.33   214.2 2793.95   253.6 2795.86   323.5 2795.22
   353.1 2792.84     370 2795.74   408.1 2794.25   428.5  2798.6   443.2 2803.81
   467.2 2809.67   498.5 2819.66   531.1 2834.15     589 2862.91   598.7 2867.25
   612.7 2872.08   627.8 2876.05   646.2 2879.54   674.3 2883.19   694.1 2883.71
#Mann= 7 ,-1 , 0
       0      .1       0  155.32     .12       0   179.9    .045       0
   202.2     .12       0  226.78      .1       0  288.38     .06       0
  433.78      .1       0
#XS Ineff= 2 , 0
                          244.03         2800.95
Permanent Ineff=
       F       F
Bank Sta=179.9,202.2
XS Rating Curve= 0 ,0
Exp/Cntr=0.3,0.1

Type RM Length L Ch R = 1 ,72694   ,530.7,527.9,515.7
XS GIS Cut Line= 3
2259043.21968497375006.7224900572258565.58907856375501.330096647
2258444.26123722375720.264041975
#Sta/Elev= 30
       0 2857.45      49 2852.55    75.7 2846.57   112.8 2833.53   184.7 2797.47
     204 2790.54   221.4 2788.19   258.8 2786.72   267.9 2782.92     277 2781.73
   307.7  2784.7   339.5 2784.78   367.8 2787.03   398.2 2785.78  409.63 2783.11
   418.4 2781.93  429.662783.331   450.3 2785.75   566.2 2787.44     610 2789.77
   632.8 2793.82   683.6 2810.96   713.8 2819.22   728.8 2820.85   757.2 2820.44
   794.3 2814.68     833 2811.42     862 2816.14   910.3 2835.84   937.9 2842.84
#Mann= 5 ,-1 , 0
       0      .1       0  406.53     .06       0  409.63    .045       0
  429.66     .06       0  564.93      .1       0
#XS Ineff= 2 , 0
          367.29 2789.25
Permanent Ineff=
       F       F
Bank Sta=409.63,429.66
XS Rating Curve= 0 ,0
Exp/Cntr=0.3,0.1

Type RM Length L Ch R = 1 ,72166   ,279,283.4,279.8
XS GIS Cut Line= 3
2258623.08076148374794.9168113172258498.08068338375031.027887642
2258204.40312114375640.851471141
#Sta/Elev= 30
       0 2836.04    19.7 2836.34    38.2 2834.74    60.9 2830.63    80.4 2825.25
   103.9 2816.49   119.9 2808.77   131.3 2801.81   160.7 2786.38   187.2 2775.78
     202 2775.29   231.3 2776.43     261 2775.66   273.72774.349   293.8    2772
   304.1 2772.53  312.942774.497   333.9 2777.48   366.7 2778.84   399.4 2778.45
   423.8 2777.19   457.7 2778.45   483.2 2777.33   499.4 2778.57   541.5 2779.19
     567 2781.89   585.2 2785.92   665.8 2789.17     800 2796.81     944 2806.88
#Mann= 7 ,-1 , 0
       0      .1       0    3.77     .12       0  208.14      .1       0
   273.7    .045       0  312.94      .1       0  427.44     .06       0
  563.48      .1       0
#XS Ineff= 2 , 0
          226.37 2778.53
Permanent Ineff=
       F       F
Bank Sta=273.7,312.94
XS Rating Curve= 0 ,0
Exp/Cntr=0.3,0.1

Type RM Length L Ch R = 1 ,71883   ,438.9,453.3,465.6
XS GIS Cut Line= 3
2258382.18065272374765.8515807242258276.62508956374988.073577225
2257969.68082155375460.296057984
#Sta/Elev= 30
       0  2815.3    18.3 2814.05    29.6 2812.55    44.1 2809.27    65.4 2801.62
    73.2 2797.77    80.5 2793.32    91.4  2788.4    98.6 2784.49   113.2  2778.5
   134.9 2772.84  154.482771.984   167.6 2769.82  186.972771.541   222.1 2773.69
   275.1 2772.98   304.4 2771.43   341.6 2773.35   361.4 2772.97   415.9 2774.84
   466.8  2775.1   484.7  2777.4   513.7 2782.96   541.6 2790.55   584.4 2805.73
   603.7  2811.4   655.4 2824.39   693.7 2832.53   757.4 2840.44   809.2 2845.86
#Mann= 6 ,-1 , 0
       0     .12       0  154.48    .045       0  186.97     .12       0
   211.8      .1       0  232.43     .06       0  383.85      .1       0
#XS Ineff= 2 , 0
                          224.67         2775.95
Permanent Ineff=
       F       F
Bank Sta=154.48,186.97
XS Rating Curve= 0 ,0
Exp/Cntr=0.3,0.1

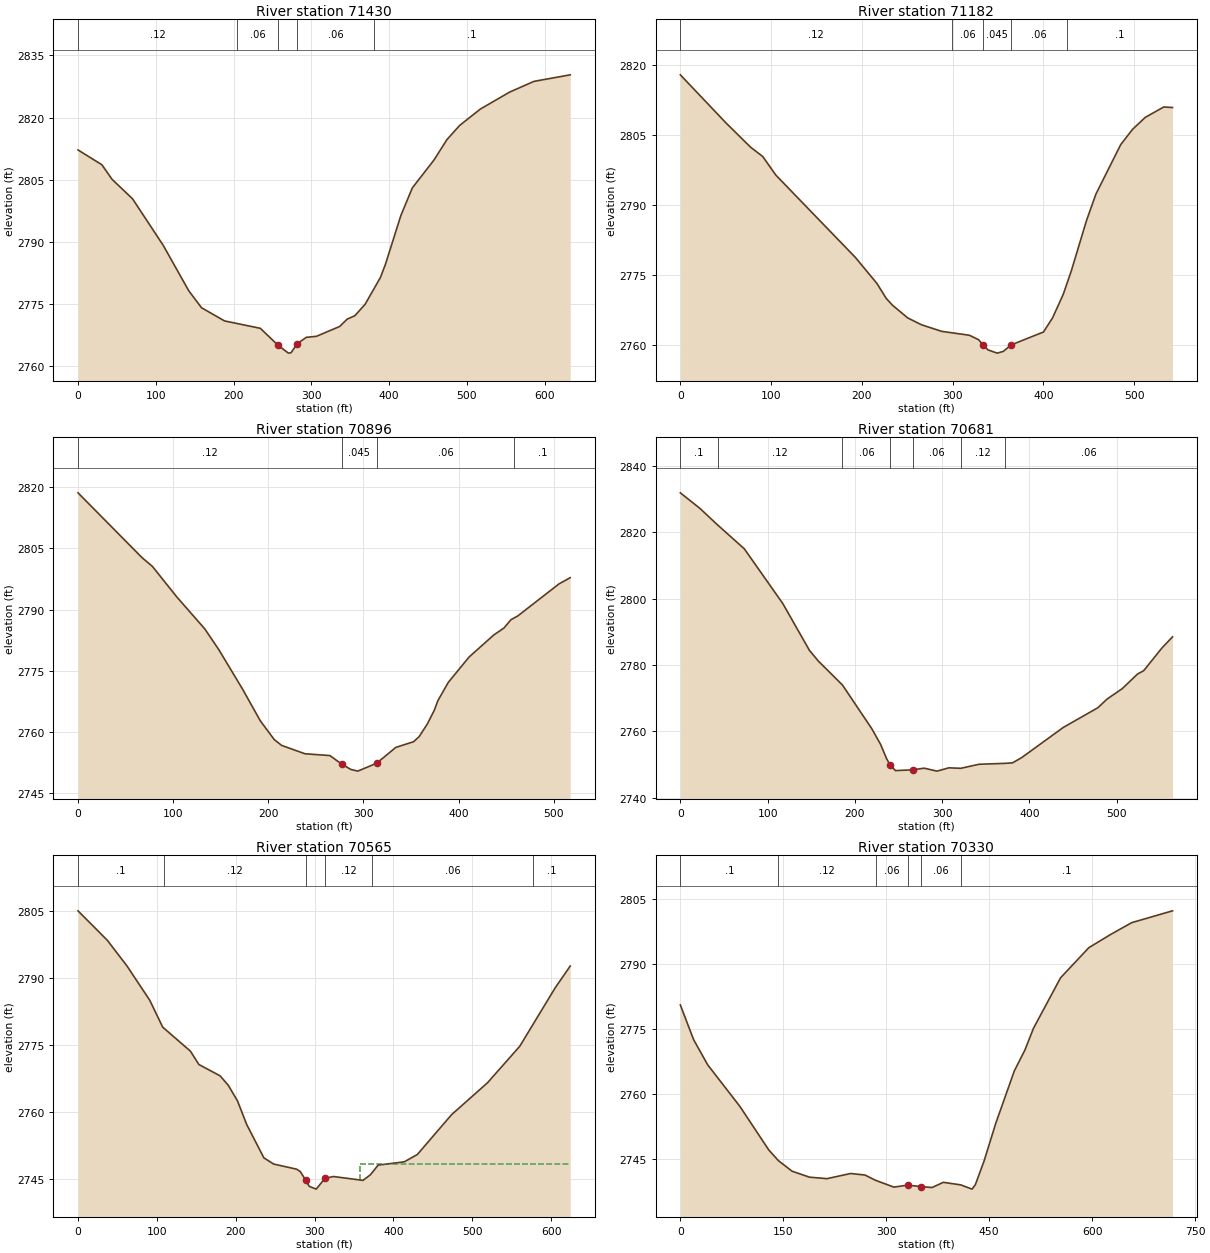
Type RM Length L Ch R = 1 ,71430   ,242.9,247.5,249.9
XS GIS Cut Line= 2
2258355.79192597374770.0182390662257723.84732372 374738.07374914
#Sta/Elev= 30
       0 2812.18    30.7  2808.6    43.8 2805.08    70.1 2800.39   109.5 2789.17
   142.4 2778.19   158.8  2774.1   188.4 2770.92   234.4 2769.14   256.8 2765.11
   270.5 2763.15   273.8 2763.24  281.952765.435   293.5 2766.96   306.6 2767.21
   336.4 2769.58   346.1 2771.36   355.9 2772.17   369.1 2774.93   388.8  2781.4
   395.2 2784.55     415 2796.31   429.8 2803.01   457.8 2809.78   474.2 2814.64
   490.6 2818.08   517.4 2822.05   554.9 2826.13   586.2 2828.72   632.8  2830.3
#Mann= 5 ,-1 , 0
       0     .12       0  204.69     .06       0   256.8    .045       0
  281.95     .06       0  380.68      .1       0
Bank Sta=256.8,281.95
XS Rating Curve= 0 ,0
Exp/Cntr=0.3,0.1

Type RM Length L Ch R = 1 ,71182   ,281.9,286,287.3
XS GIS Cut Line= 2
2258439.12509264374607.5182359812257915.51426323374465.851524562
#Sta/Elev= 30
       0 2817.81    50.1 2807.56    77.3 2802.35    90.9 2800.31   105.2 2796.37
   192.9 2778.75   216.7 2773.17   226.9 2769.99   233.6 2768.56   250.6 2765.81
   265.7 2764.35     288 2762.94   318.6  2762.1   328.8 2761.14   333.32760.095
     339 2758.97   349.2 2758.28     356 2758.66  364.532760.034   400.2  2762.8
   410.2 2765.82   421.9 2770.82   430.8 2775.83   447.6 2786.64     458 2792.31
   485.3 2802.88   498.4 2806.16   512.3  2808.7   532.7 2810.93   542.4 2810.82
#Mann= 5 ,-1 , 0
       0     .12       0  299.48     .06       0   333.3    .045       0
  364.53     .06       0  425.59      .1       0
Bank Sta=333.3,364.53
XS Rating Curve= 0 ,0
Exp/Cntr=0.3,0.1

Type RM Length L Ch R = 1 ,70896   ,216.2,214.7,213.5
XS GIS Cut Line= 2
2258500.23619089374408.9070846442258036.34735489374179.740220144
#Sta/Elev= 30
       0 2818.65    67.2 2802.76    78.2 2800.59   103.8 2793.11   133.3 2785.24
     148 2780.16   173.3 2770.34   191.6  2762.7   206.3 2758.08   214.1 2756.65
   238.6  2754.6   264.8 2754.16   277.2 2752.06   286.8 2750.76   294.1 2750.34
  313.922752.274   334.1 2756.17   352.7 2757.55   358.6  2758.8   367.3 2761.95
   374.6 2765.31   378.2 2767.58   389.2 2772.11   411.2 2778.37     437 2783.75
   447.8 2785.47   455.1  2787.5   462.4 2788.45   505.6 2796.29   517.4 2797.82
#Mann= 4 ,-1 , 0
       0     .12       0   277.2    .045       0  313.92     .06       0
  458.79      .1       0
Bank Sta=277.2,313.92
XS Rating Curve= 0 ,0
Exp/Cntr=0.3,0.1

Type RM Length L Ch R = 1 ,70681   ,126.1,116.5,103.4
XS GIS Cut Line= 3
2258612.41425513374175.362868851 2258304.1200447374092.083393825
2258074.30072419374176.163633034
#Sta/Elev= 30
       0 2831.93    22.3 2827.27    42.7 2822.25    73.3 2815.06   117.5 2798.53
     148 2784.43   158.2 2781.21   185.8    2774   219.4 2760.84   229.6 2756.06
   236.4 2751.79   240.7 2749.76   246.6  2748.2   266.82748.434   279.4 2748.93
   294.2 2748.04   307.8 2749.04   321.4 2748.89   342.4 2750.11     372 2750.38
   380.8 2750.54   391.3 2752.13   438.9 2761.21   478.6 2767.16   489.1 2769.76
   506.4 2772.89     524 2777.31     531  2778.3     552 2785.17   564.1 2788.52
#Mann= 7 ,-1 , 0
       0      .1       0    42.7     .12       0   185.8     .06       0
   240.7    .045       0   266.8     .06       0   321.4     .12       0
     372     .06       0
Bank Sta=240.7,266.8
XS Rating Curve= 0 ,0
Exp/Cntr(USF)=0,0
Exp/Cntr=0.3,0.1

Type RM Length L Ch R = 1 ,70565   ,234.6,234.5,230.1
XS GIS Cut Line= 3
2258571.06971064373829.7402639842258186.34738298374125.573661804
2258054.40309305374168.629349977
#Sta/Elev= 30
       0 2805.14    37.1 2798.54    61.9 2792.82    90.9  2785.1   107.4 2779.04
   142.5 2773.67   153.3 2770.66   180.2 2768.12   190.5 2766.01   202.2 2762.52
   213.9  2757.2   235.7 2749.72   248.2 2748.33   277.1 2747.19   281.8 2746.66
  288.562744.757   293.2 2743.34     302 2742.71  313.132745.136   323.9 2745.54
   361.3 2744.67   370.7 2745.92   380.6  2748.1   413.7 2748.83   430.3 2750.48
   473.6  2759.4   519.2 2766.56   560.2 2774.77   604.9 2787.82   624.1 2792.75
#Mann= 6 ,-1 , 0
       0      .1       0  108.47     .12       0  288.56    .045       0
  313.13     .12       0  373.36     .06       0  576.44      .1       0
#XS Ineff= 2 , 0
                          356.93         2748.44
Permanent Ineff=
       F       F
Bank Sta=288.56,313.13
XS Rating Curve= 0 ,0
Exp/Cntr=0.3,0.1

Type RM Length L Ch R = 1 ,70330   ,184.2,187.3,188.9
XS GIS Cut Line= 2
2258396.85274568373603.5406308132257943.03448983374158.826850501
#Sta/Elev= 30
       0 2780.51    19.3  2772.5    39.9 2766.66    86.6 2757.11   128.9    2747
   142.9 2744.54   162.8  2742.1   188.2 2740.72   213.7 2740.38   248.1 2741.57
   268.9 2741.22   284.4    2740   311.1 2738.43   331.1 2738.88   350.12738.559
   366.7 2738.33   383.2 2739.53   408.6 2738.94     425 2737.96   429.8 2738.98
   442.5 2744.45   459.4 2753.08   486.6 2765.27     502 2770.08   514.5 2775.11
     554 2786.78   595.2 2793.74   626.6 2796.76   657.7 2799.52   717.1 2802.25
#Mann= 6 ,-1 , 0
       0      .1       0   142.9     .12       0   284.4     .06       0
   331.1    .045       0   350.1     .06       0   408.6      .1       0
Bank Sta=331.1,350.1
XS Rating Curve= 0 ,0
Exp/Cntr(USF)=0,0
Exp/Cntr=0.3,0.1