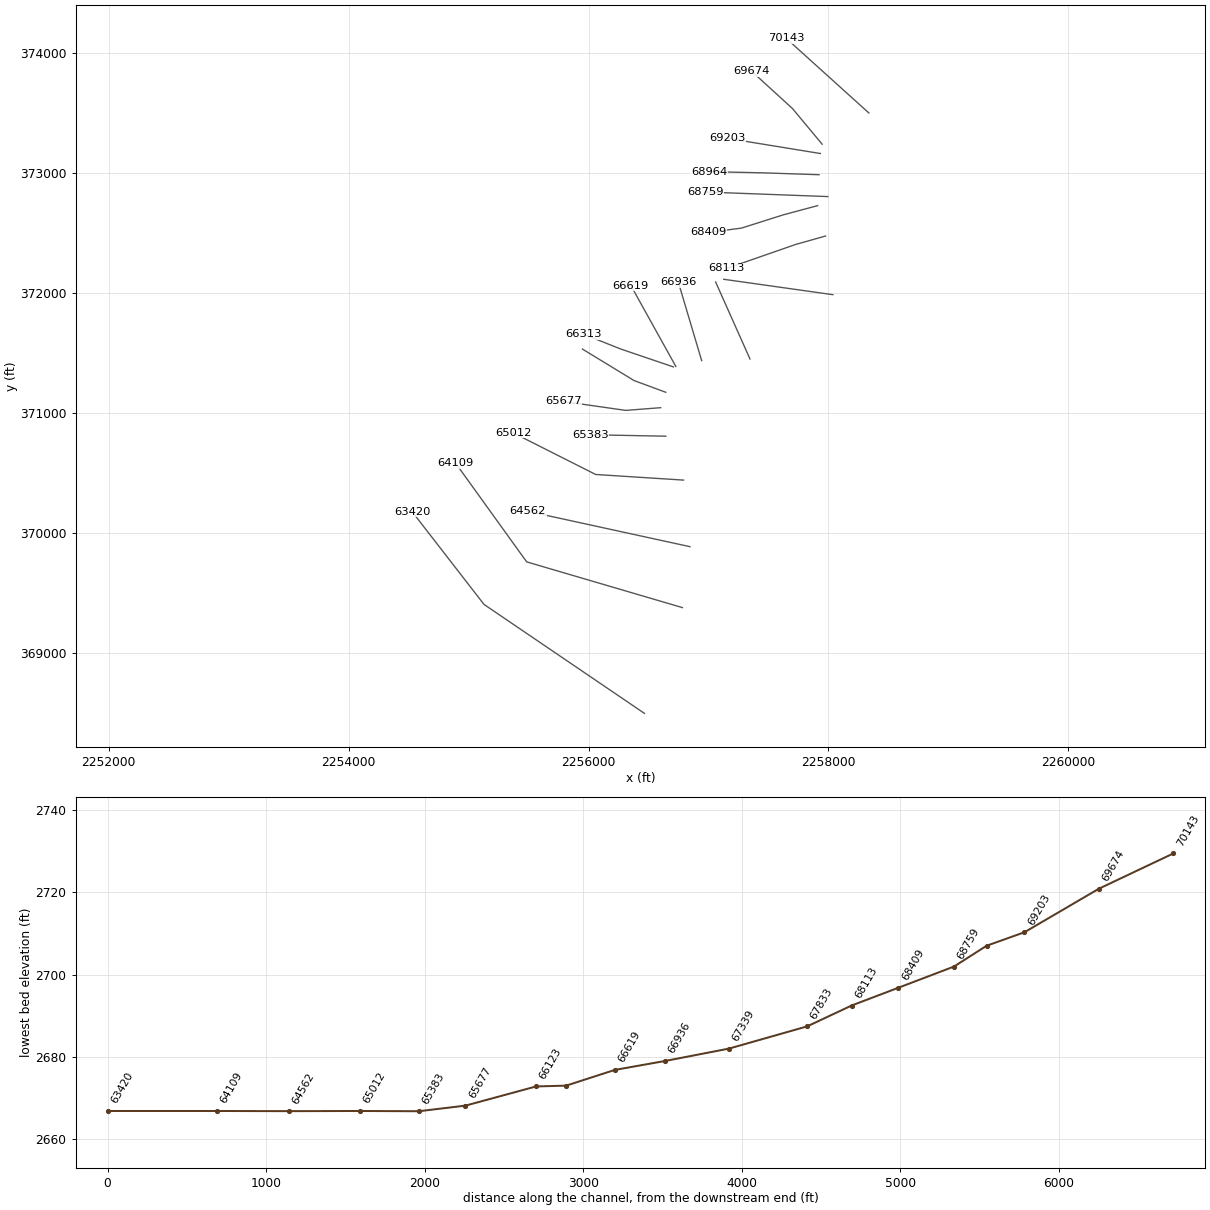
HEC-RAS study MEADOWCK1.prj: MEADOWCK1

--- MEADOWCK1.g01 (geometry) --- (continued)

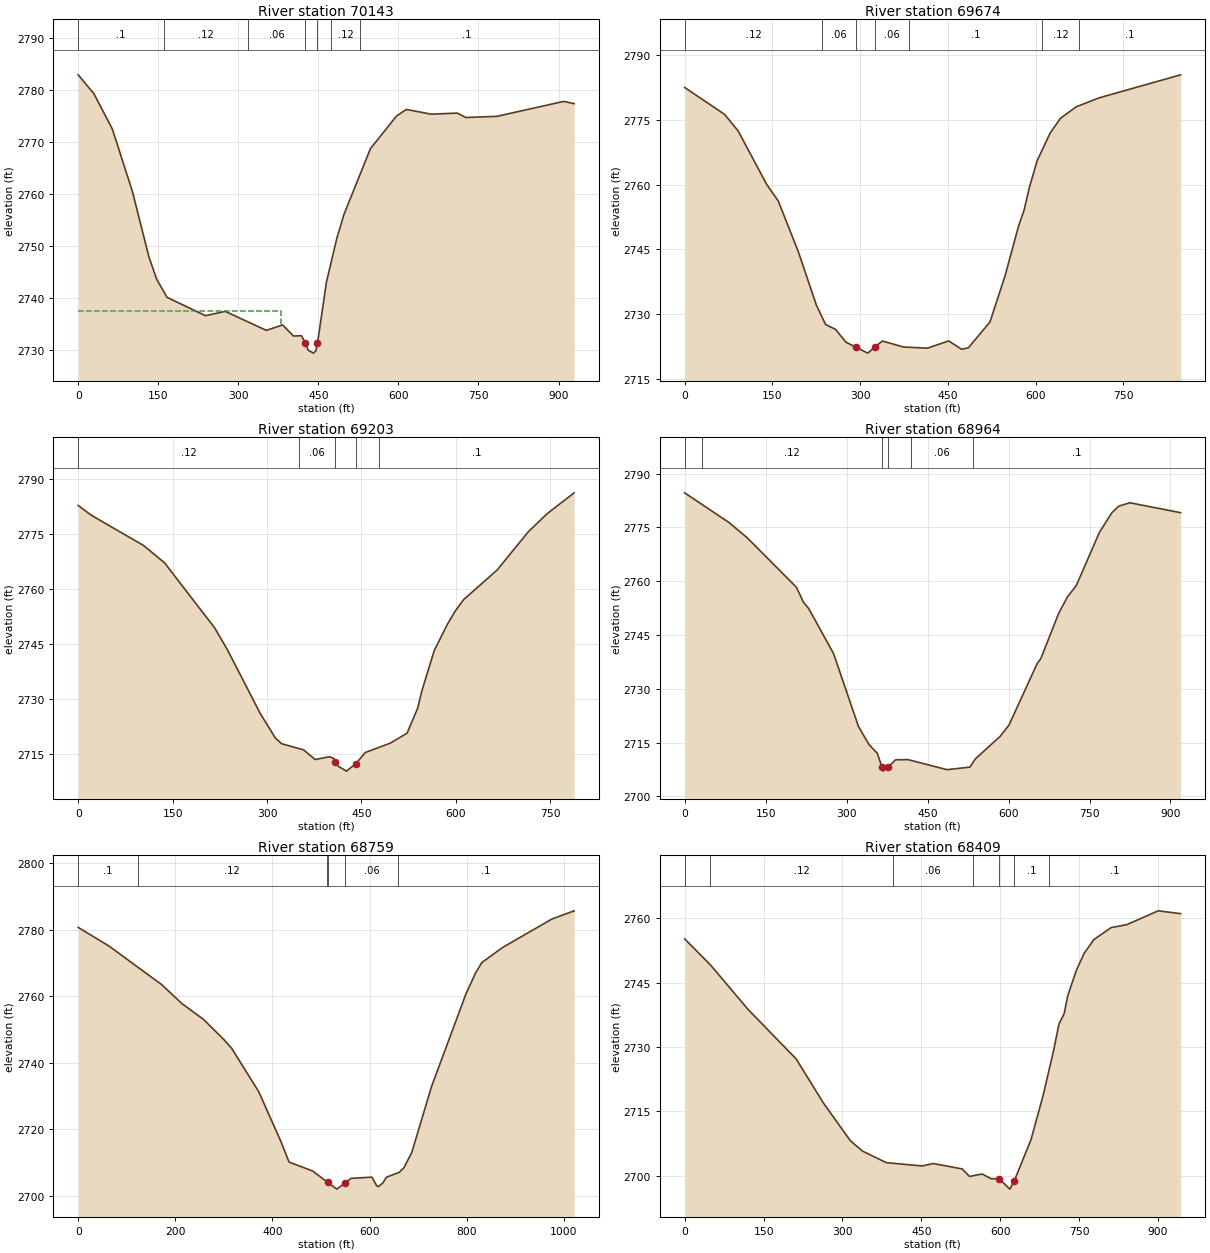
Type RM Length L Ch R = 1 ,70143   ,466.9,468.9,459.3
XS GIS Cut Line= 2
2258337.06591356373503.0831088872257647.48231897374125.999842063
#Sta/Elev= 30
       0 2783.01    29.3 2779.39    63.9  2772.6   101.5 2760.59   132.4 2748.02
   147.1 2743.68   166.4  2740.2   238.5 2736.68   275.7  2737.5   352.6 2733.84
     383  2734.9   403.4 2732.76   418.4 2732.82  425.372731.466   430.9 2730.04
   440.5 2729.47   445.3 2729.88  448.282731.333   465.2 2743.17   484.7 2751.59
     498 2756.16   547.5 2768.79   596.2 2775.06   614.8 2776.35   661.6 2775.44
   710.2 2775.65   726.3  2774.8   784.4 2775.02   909.8  2777.9   929.3 2777.46
#Mann= 7 ,-1 , 0
       0      .1       0  159.84     .12       0  317.68     .06       0
  425.37    .045       0  448.28     .06       0   473.6     .12       0
   527.9      .1       0
#XS Ineff= 2 , 0
          380.31  2737.5
Permanent Ineff=
       F       F
Bank Sta=425.37,448.28
XS Rating Curve= 0 ,0
Exp/Cntr=0.3,0.1

Type RM Length L Ch R = 1 ,69674   ,447.8,471,473.9
XS GIS Cut Line= 3
2257947.48237513373242.6666349772257699.56587622373540.583361983
2257359.98256588373850.999735892
#Sta/Elev= 30
       0 2782.51    68.3 2776.26    91.4 2772.43   140.6 2759.93   159.7 2756.27
   193.9 2744.56   225.1 2732.05   240.8 2727.57   257.9 2726.43   275.6 2723.46
  293.132722.269   312.9 2720.92   325.72722.412     338 2723.73   373.9 2722.34
   414.9 2722.07   451.3 2723.75   473.4 2721.81     485 2722.17   521.9 2728.15
   547.7 2738.88   570.9 2750.47   580.2 2754.09   589.1 2759.28   602.4  2765.5
   624.6 2771.92   642.4 2775.38   669.1 2778.01   707.9 2780.08   847.7 2785.44
#Mann= 7 ,-1 , 0
       0     .12       0   235.3     .06       0  293.13    .045       0
   325.7     .06       0  383.71      .1       0  610.93     .12       0
  674.62      .1       0
Bank Sta=293.13,325.7
XS Rating Curve= 0 ,0
Exp/Cntr=0.3,0.1

Type RM Length L Ch R = 1 ,69203   ,234,239.2,242.8
XS GIS Cut Line= 2
 2257932.1700698373165.062459484 2257154.3920978373291.798426479
#Sta/Elev= 30
       0 2782.85    20.7 2780.17   103.8 2771.91     137 2767.22   216.8 2749.42
   236.8 2743.53   289.6 2725.94   313.2 2719.38   323.2  2717.8   358.2 2716.12
   376.4 2713.49   399.6 2714.24   406.3 2713.72  408.732712.873   412.9 2711.69
   426.2 2710.32  441.432712.385   456.1  2715.4     496 2717.97   522.6 2720.69
   539.3 2727.48   545.9 2732.15   565.8 2743.27   586.8 2750.47   599.1 2754.03
   612.5 2757.15   665.6 2765.21   715.4 2775.69   745.3 2780.61     788 2786.28
#Mann= 5 ,-1 , 0
       0     .12       0  350.12     .06       0  408.73    .045       0
  441.43     .06       0   478.6      .1       0
Bank Sta=408.73,441.43
XS Rating Curve= 0 ,0
Exp/Cntr=0.3,0.1

Type RM Length L Ch R = 1 ,68964   ,196.5,204.6,209.6
XS GIS Cut Line= 3
2257921.75342397372987.9791522322257459.94758905 373003.60412097
2257003.35040514 373014.02076681
#Sta/Elev= 30
       0 2784.65    82.2 2776.36   115.1 2772.22     207 2758.32   220.1 2754.13
     230 2752.32   275.9 2739.79   321.9 2719.52   341.6 2714.41   356.8 2712.02
  365.382708.257   367.8 2707.03  376.87 2708.16   390.7 2710.18   413.8 2710.24
     486 2707.44   528.7 2708.16   538.5 2710.44   584.4 2716.71   600.9  2719.9
   653.2 2737.07   659.9 2738.44   692.7 2750.98   709.2 2755.62   725.6 2758.82
   768.2 2773.57   791.2 2779.06   804.3 2780.95   824.8 2781.88   918.8 2779.11
#Mann= 6 ,-1 , 0
       0      .1       0   31.76     .12       0  365.38    .045       0
  376.87     .12       0   419.9     .06       0  534.24      .1       0
Bank Sta=365.38,376.87
XS Rating Curve= 0 ,0
Exp/Cntr=0.3,0.1

Type RM Length L Ch R = 1 ,68759   ,339.5,350.8,347.9
XS GIS Cut Line= 2
2257994.66994481372805.6875220542256973.83668464372843.881671399
#Sta/Elev= 30
       0 2780.63    63.3 2775.04   171.6 2763.48   213.7 2757.74   258.1 2752.99
   299.7 2746.97   316.1 2744.31   371.9 2731.25   417.9 2716.18   434.3 2710.12
   483.2 2707.43  514.052703.996   532.8    2702  550.062703.941   562.3 2705.24
     605  2705.6   614.8 2703.01   618.1 2702.75     628 2703.93   634.5 2705.56
   661.1 2707.04   670.8  2708.4   687.1 2713.02   727.5 2732.72   798.7 2760.67
   818.4 2766.92   831.5 2770.09   874.2  2774.6     976 2783.17  1021.5 2785.61
#Mann= 6 ,-1 , 0
       0      .1       0  122.71     .12       0  511.49     .06       0
  514.05    .045       0  550.06     .06       0  659.04      .1       0
Bank Sta=514.05,550.06
XS Rating Curve= 0 ,0
Exp/Cntr=0.3,0.1

Type RM Length L Ch R = 1 ,68409   ,292.6,295.2,294.6
XS GIS Cut Line= 4
2257909.92470747372730.1502715652257625.20250788372653.761316732
 2257274.5079993372542.6503184742256996.73001155372506.192058057
#Sta/Elev= 30
       0 2755.24    49.1 2749.16   120.4  2738.8   212.1 2727.21   263.1 2717.06
     315 2708.14     338 2705.73   383.4 2703.02   451.9 2702.26   472.6 2702.83
   527.6 2701.56   541.4 2699.81   565.5 2700.38   582.7 2699.26  597.562699.285
   618.2 2696.85  626.712698.812   658.4  2708.4   681.8  2718.9   701.6 2729.33
   711.5 2735.35   721.5 2737.81   728.1 2741.93   744.6 2747.91   759.1  2751.8
   777.7 2755.06   810.8 2757.88   840.6 2758.57   900.1 2761.79   942.8 2761.13
#Mann= 7 ,-1 , 0
       0      .1       0   48.87     .12       0   395.9     .06       0
  547.16      .1       0  597.56    .045       0  626.71      .1       0
  693.27      .1       0
Bank Sta=597.56,626.71
XS Rating Curve= 0 ,0
Exp/Cntr=0.3,0.1

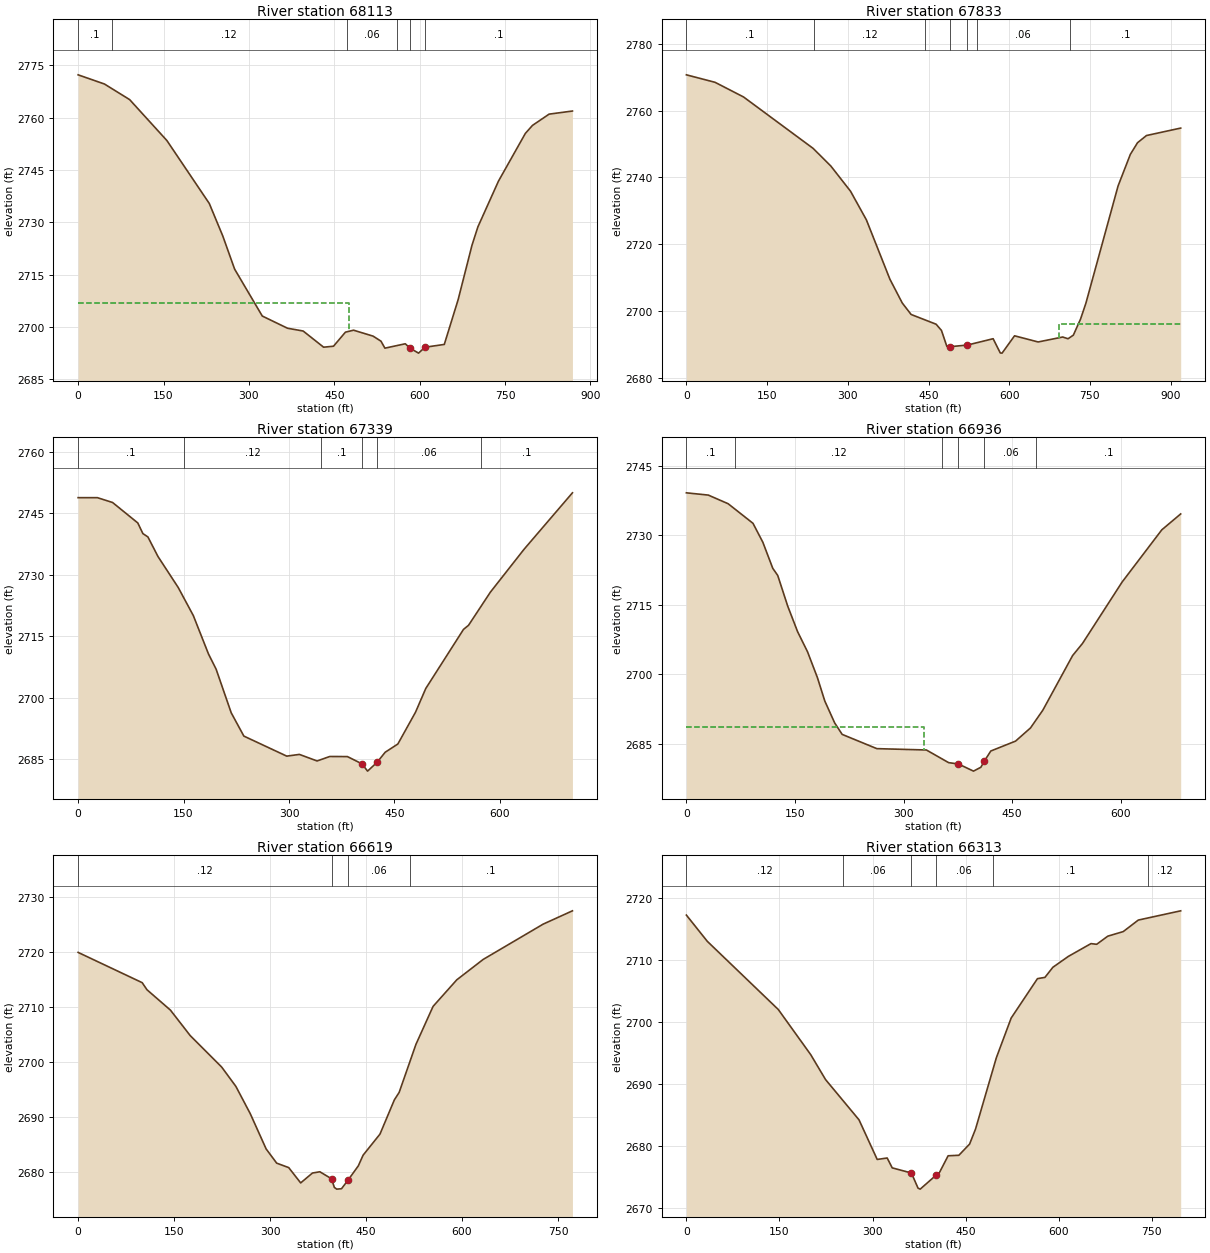
Type RM Length L Ch R = 1 ,68113   ,290.3,280.7,275
XS GIS Cut Line= 3
2257975.89668839 372476.678009482257724.16064331372405.497705638
2257151.24413823 372205.84488973
#Sta/Elev= 30
       0 2772.24    46.2 2769.61    90.5 2765.14   155.9 2753.42   230.4 2735.39
   254.2 2726.04   274.9 2716.59   323.5 2703.15   367.8 2699.66   395.3 2698.86
   431.2 2694.23   448.6 2694.51   469.5 2698.53   483.8  2699.1   518.1  2697.4
     532 2695.95   538.9 2693.95   574.7 2695.21     5832693.943     598 2692.53
   609.22694.215   643.2 2695.02   667.5 2707.83   691.8  2723.4   702.2 2728.68
   738.4  2741.8   785.6 2755.46   798.1 2757.75   827.3 2760.98   868.3 2761.87
#Mann= 6 ,-1 , 0
       0      .1       0   58.68     .12       0   471.6     .06       0
  560.02      .1       0     583    .045       0   609.2      .1       0
#XS Ineff= 2 , 0
          476.51 2707.01
Permanent Ineff=
       F       F
Bank Sta=583,609.2
XS Rating Curve= 0 ,0
Exp/Cntr=0.3,0.1

Type RM Length L Ch R = 1 ,67833   ,507.9,493.5,481
XS GIS Cut Line= 2
2258036.66067447371987.0946710562257126.93841255372115.566855058
#Sta/Elev= 30
       0 2770.71    53.3 2768.47   106.3 2764.08   235.5 2748.71   268.6  2743.4
   305.1 2735.88   334.5 2727.34   378.2 2709.59   401.2 2702.46   417.7 2699.02
   464.1 2696.11   474.1 2694.24     484 2689.51  490.442689.394  522.332689.876
   570.1 2691.77   583.4 2687.51   586.7 2687.46   609.9 2692.64   653.8  2690.8
   699.4 2692.28   709.3 2691.76   719.2 2692.84   732.5 2697.62   742.4 2702.33
   802.3 2737.46   825.1 2746.91   838.5 2750.41   855.1 2752.55   918.7 2754.78
#Mann= 7 ,-1 , 0
       0      .1       0  236.56     .12       0   443.7      .1       0
  490.44    .045       0  522.33      .1       0  539.64     .06       0
  712.71      .1       0
#XS Ineff= 2 , 0
                          692.13         2696.21
Permanent Ineff=
       F       F
Bank Sta=490.44,522.33
XS Rating Curve= 0 ,0
Exp/Cntr=0.3,0.1

Type RM Length L Ch R = 1 ,67339   ,400.7,403.6,402.6
XS GIS Cut Line= 2
2257345.68863122371450.6364263892257059.23021464 372092.99767448
#Sta/Elev= 30
       0  2748.8    27.4  2748.8      49 2747.62    84.9 2742.63    92.1 2740.04
    99.3 2739.21   113.6 2734.44   142.4 2726.88   163.9 2720.02   185.5 2710.64
   196.3 2706.96   217.8  2696.3   235.8 2690.61   296.8 2685.72   314.8 2686.14
     340 2684.54     358 2685.63   383.1 2685.61     4042683.828   411.8 2682.06
  425.272684.196   436.9 2686.67   454.9 2688.68   480.1 2696.46   494.6 2702.22
   548.3 2716.65   555.5 2717.66   586.6 2725.75   634.5 2736.21   703.3 2749.98
#Mann= 6 ,-1 , 0
       0      .1       0  150.98     .12       0  345.94      .1       0
     404    .045       0  425.27     .06       0  572.82      .1       0
Bank Sta=404,425.27
XS Rating Curve= 0 ,0
Exp/Cntr=0.3,0.1

Type RM Length L Ch R = 1 ,66936   ,313.6,316.8,318.5
XS GIS Cut Line= 2
2256942.91056539371436.7476746442256748.46640047372091.261457473
#Sta/Elev= 30
       0 2739.21    30.3 2738.72    57.7 2736.85      92 2732.62   105.6 2728.53
   119.3  2722.9   126.2 2721.34   139.9 2714.75   153.6  2709.2   167.3 2704.86
     181 2699.26   191.2  2694.2   204.9 2689.45   215.2 2686.99   263.1 2683.91
   331.5 2683.62   362.3 2680.88   375.72680.599   396.6 2679.05   406.8 2679.89
  411.632681.236   420.5  2683.4   454.7 2685.54   475.3 2688.38   492.4 2692.23
   533.5 2704.03   547.2 2706.66   601.9 2719.93   656.7 2731.21   682.8 2734.65
#Mann= 6 ,-1 , 0
       0      .1       0   67.43     .12       0  352.95     .06       0
   375.7    .045       0  411.63     .06       0  483.31      .1       0
#XS Ineff= 2 , 0
          327.62 2688.64
Permanent Ineff=
       F       F
Bank Sta=375.7,411.63
XS Rating Curve= 0 ,0
Exp/Cntr=0.3,0.1

Type RM Length L Ch R = 1 ,66619   ,294.1,306,317
XS GIS Cut Line= 2
2256727.63278072371388.1365513952256352.63287455372063.483625889
#Sta/Elev= 30
       0 2719.98   100.1 2714.47   107.6 2713.18   144.2 2709.48   175.2 2704.83
   224.5 2699.08   246.5 2695.59     269 2690.62   293.8  2684.2   310.3 2681.61
   329.1  2680.8   347.8 2678.01   366.2 2679.81   377.8 2680.04  396.062678.757
   400.4  2677.2   404.1 2676.88   411.6 2676.95  422.24 2678.59   437.9 2681.12
   445.4 2683.07   471.7 2686.89   494.2 2693.13   501.7 2694.49   527.9 2703.23
   554.7 2710.15   591.7 2714.98     633  2718.7   726.8 2725.13   772.5 2727.55
#Mann= 4 ,-1 , 0
       0     .12       0  396.06    .045       0  422.24     .06       0
   518.4      .1       0
Bank Sta=396.06,422.24
XS Rating Curve= 0 ,0
Exp/Cntr=0.3,0.1

Type RM Length L Ch R = 1 ,66313   ,193,190.1,184.8
XS GIS Cut Line= 3
2256706.79948905371384.6641173962256267.56349088371533.969921142
2255958.53556564371657.233782232
#Sta/Elev= 30
       0 2717.28    33.7 2713.05   148.1 2702.05   200.4 2694.76   224.3 2690.74
   278.2 2684.25   307.5 2677.86   323.6 2678.09   331.7  2676.5  362.642675.671
   373.3 2673.23   376.8 2673.07  401.84 2675.27     408 2675.78   421.8 2678.45
   439.1 2678.53   456.4 2680.34     466 2682.77   499.5 2694.26   523.4 2700.67
   565.8 2707.03   577.8 2707.23   590.6 2708.86   615.6 2710.62     652 2712.68
   661.2 2712.57   679.1 2713.88     704 2714.62   728.3 2716.48   796.6 2717.97
#Mann= 6 ,-1 , 0
       0     .12       0  253.08     .06       0  362.64    .045       0
  401.84     .06       0  493.59      .1       0  744.36     .12       0
Bank Sta=362.64,401.84
XS Rating Curve= 0 ,0
Exp/Cntr=0.3,0.1

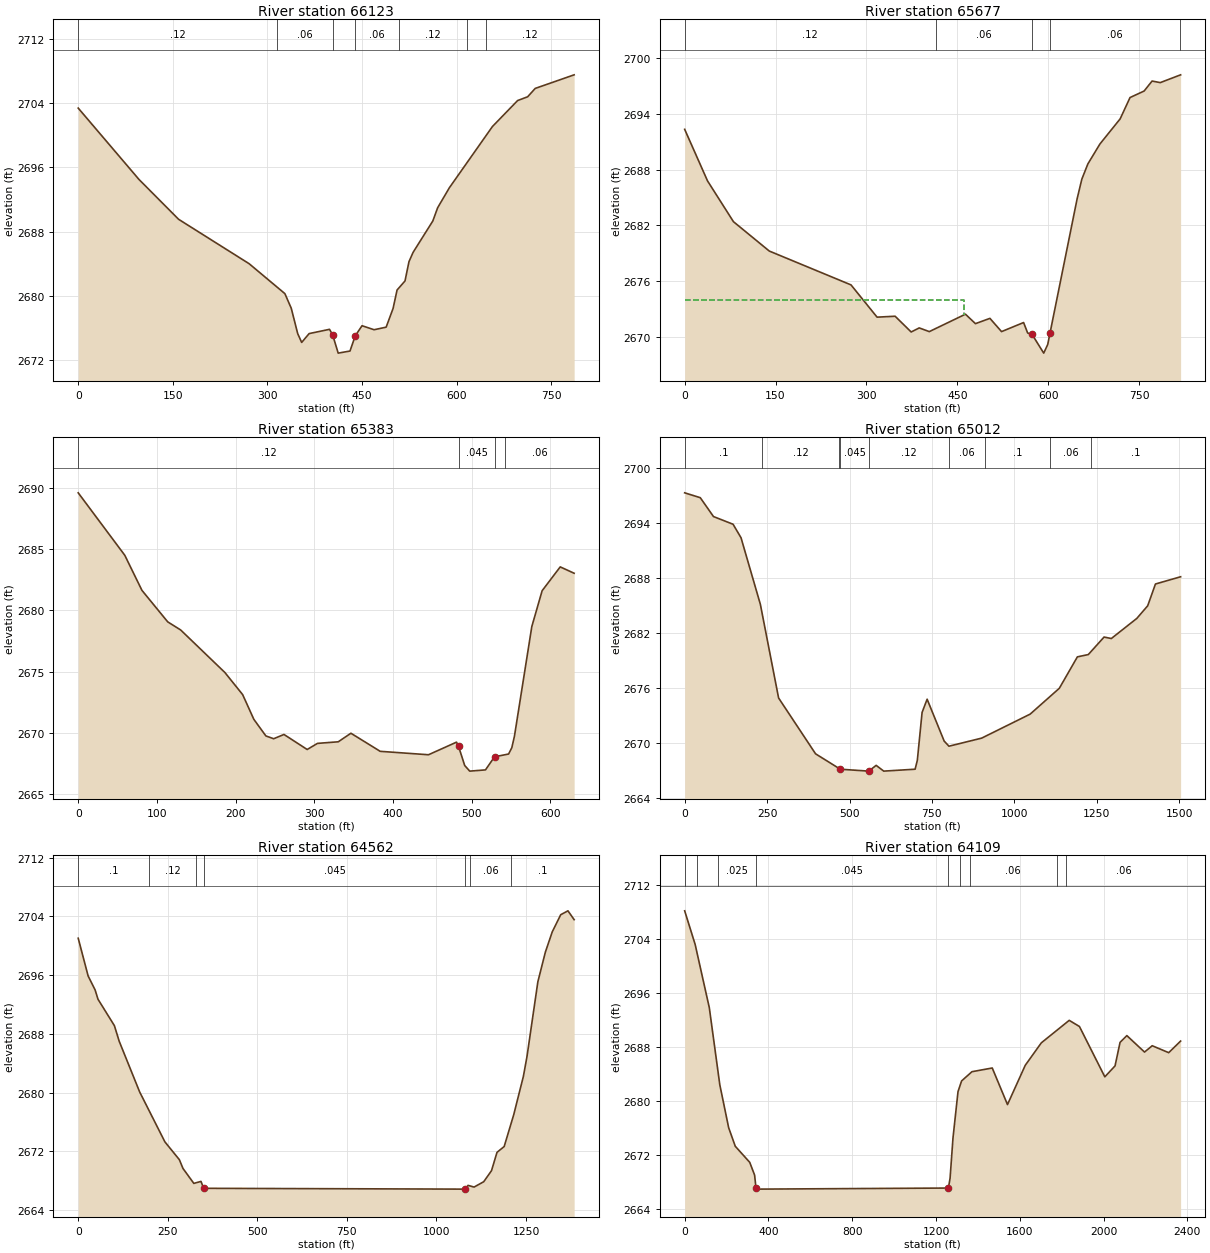
Type RM Length L Ch R = 1 ,66123   ,432.7,445.6,441.2
XS GIS Cut Line= 3
2256643.61687264371172.8761551382256379.03341231371270.792625979
2255948.82495514371533.292757139
#Sta/Elev= 30
       0 2703.35    96.4 2694.47   159.1 2689.52     271 2683.99   327.6 2680.27
   337.7 2678.45   347.9  2675.3   354.2  2674.2     366  2675.3   398.3 2675.83
   403.22675.167   412.1 2672.87   430.8 2673.13   439.22675.034   449.9 2676.28
     469 2675.78   488.1  2676.1   499.1 2678.43   505.4 2680.72     518 2681.85
   524.3 2684.25     531 2685.43   562.1 2689.31   569.7 2690.95   588.3 2693.44
   656.6 2701.06   696.5 2704.29   712.4 2704.76   724.4  2705.8   786.1 2707.49
#Mann= 7 ,-1 , 0
       0     .12       0  315.13     .06       0   403.2    .045       0
   439.2     .06       0  508.78     .12       0  616.04      .1       0
  646.05     .12       0
Bank Sta=403.2,439.2
XS Rating Curve= 0 ,0
Exp/Cntr=0.3,0.1

Type RM Length L Ch R = 1 ,65677   ,296.3,294.3,292.4
XS GIS Cut Line= 3
2256600.90829664371044.2996406412256309.24155714371021.730131984
2255788.40828122 371096.38286981
#Sta/Elev= 30
       0 2692.35    37.7 2686.79    80.5 2682.39   139.7 2679.22   274.6 2675.57
   317.6 2672.09   347.4 2672.19   373.9 2670.49   387.2 2670.93   403.8 2670.53
   463.5 2672.41     480 2671.39   503.9 2671.96   523.1 2670.53   559.5 2671.51
   566.2 2670.38   573.5 2670.23   592.7 2668.21   599.3 2669.14     6032670.341
   647.8 2684.84   655.6 2686.97   665.6 2688.62   685.5 2690.77   718.9 2693.48
   735.2 2695.78   758.4 2696.48   771.6 2697.56   785.1 2697.39   818.7 2698.23
#Mann= 5 ,-1 , 0
       0     .12       0  414.73     .06       0   573.5    .045       0
     603     .06       0  817.61      .1       0
#XS Ineff= 2 , 0
          461.23 2673.97
Permanent Ineff=
       F       F
Bank Sta=573.5,603
XS Rating Curve= 0 ,0
Exp/Cntr=0.3,0.1

Type RM Length L Ch R = 1 ,65383   ,392.9,370.6,372.2
XS GIS Cut Line= 2
2256644.31109697370806.4523473082256014.10271172 370818.60521014
#Sta/Elev= 30
       0 2689.62    59.2 2684.51      81 2681.64   113.8 2679.06   130.2  2678.4
   186.4 2674.92     209 2673.11   223.2 2671.09   238.5 2669.73   248.4  2669.5
   261.5 2669.85     291 2668.62   304.1 2669.12   330.5 2669.25   346.6 2669.95
   383.8 2668.47   445.2 2668.19   480.8 2669.22  483.36 2668.88   491.2 2667.31
   497.6 2666.85   517.6 2666.95  529.082668.021     547 2668.25   551.1 2668.77
   554.4  2669.7   576.5 2678.68   589.6 2681.61   612.6 2683.56   630.3 2683.04
#Mann= 4 ,-1 , 0
       0     .12       0  483.36    .045       0  529.08     .12       0
  542.07     .06       0
Bank Sta=483.36,529.08
XS Rating Curve= 0 ,0
Exp/Cntr=0.3,0.1

Type RM Length L Ch R = 1 ,65012   ,545.7,449.7,579.7
XS GIS Cut Line= 3
2256791.88068372370440.1328699742256059.24172905370487.008104309
2255371.74179173370834.230178893
#Sta/Elev= 30
       0 2697.28    47.3 2696.75    87.4 2694.69   146.8 2693.85   170.9 2692.38
   229.6 2685.11   284.9 2674.89     397  2668.8  471.95 2667.12   557.8 2666.91
  560.432666.965   580.8 2667.54   603.8 2666.91     699 2667.12   705.7 2668.09
   720.1 2673.31   735.4 2674.76   787.1 2670.19   801.6 2669.63   900.8 2670.51
  1047.9 2673.13  1136.4 2675.95  1191.2 2679.38  1224.3 2679.63  1272.1 2681.54
  1294.1 2681.38  1371.3 2683.57  1404.4 2684.95    1428 2687.33  1504.3 2688.12
#Mann= 9 ,-1 , 0
       0      .1       0  234.46     .12       0  468.95    .045       0
  471.95    .045       0  560.43     .12       0  800.81     .06       0
  910.66      .1       0 1108.66     .06       0 1232.36      .1       0
Bank Sta=471.95,560.43
XS Rating Curve= 0 ,0
Exp/Cntr=0.3,0.1

Type RM Length L Ch R = 1 ,64562   ,489.2,453.4,440.3
XS GIS Cut Line= 2
2256845.70012988 369884.577550652255493.26943581370179.716396064
#Sta/Elev= 30
       0 2701.02    27.7 2695.88    47.2 2693.98    55.2 2692.72     101 2689.12
   114.4    2687   171.5  2680.1     242  2673.3   282.3 2670.88   292.5 2669.68
   322.7 2667.65   342.7 2667.92   350.2 2666.98  1077.9 2666.87  1080.7 2666.88
  1088.2 2667.38    1105 2667.15  1131.9 2667.88  1153.6 2669.38    1169 2671.88
    1189 2672.67  1215.7 2677.01  1242.7 2682.24  1252.8 2684.96    1283 2695.09
  1303.9 2699.12  1323.2 2701.89  1346.8 2704.22    1367 2704.75  1384.3 2703.55
#Mann= 7 ,-1 , 0
       0      .1       0  197.52     .12       0  328.56    .025       0
   350.2    .045       0  1080.7      .1       0 1092.75     .06       0
 1208.41      .1       0
Bank Sta=350.2,1080.7
XS Rating Curve= 0 ,0
Exp/Cntr=0.3,0.1

Type RM Length L Ch R = 1 ,64109   ,838.8,689.6,523.6
XS GIS Cut Line= 3
2256781.98261643369376.4051934292255483.79221902369757.870040504
2254891.19972331370581.783058949
#Sta/Elev= 30
       0 2708.15    50.1 2703.16   117.6  2693.8   167.8 2682.36   210.1    2676
   241.6 2673.26   310.6 2670.88   333.9 2668.99   340.7 2667.03   344.2 2666.91
  1259.4 2667.07  1267.3 2668.55  1281.1 2674.48  1305.1 2681.36  1322.2 2682.94
  1371.6 2684.31  1468.6 2684.86  1541.4 2679.44  1626.2 2685.26    1703 2688.59
  1836.1 2691.92  1884.9 2691.01  2006.1 2683.55  2054.9 2685.17  2078.9 2688.66
  2111.3 2689.66  2195.7 2687.22  2232.4 2688.16  2311.1 2687.13    2368 2688.85
#Mann= 9 ,-1 , 0
       0      .1       0   59.71      .1       0  159.83    .025       0
   340.7    .045       0  1259.4     .06       0  1315.5      .1       0
 1361.31     .06       0 1776.08     .12       0 1823.02     .06       0
Bank Sta=340.7,1259.4
XS Rating Curve= 0 ,0
Exp/Cntr=0.3,0.1

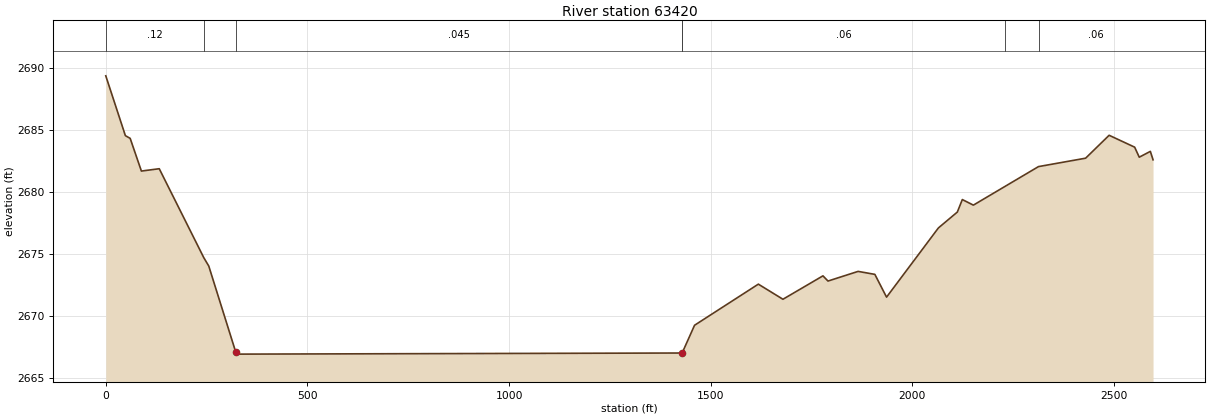
Type RM Length L Ch R = 1 ,63420   ,778.6,722.7,719.2
XS GIS Cut Line= 3
2256465.74478528368493.7834614122255127.99162306369402.980088636
2254528.36699574370177.294027435
#Sta/Elev= 30
       0 2689.38    48.6 2684.55    60.5 2684.33    88.3 2681.69   132.6 2681.88
     243  2674.7   255.4 2674.02   322.3 2667.07   326.3 2666.91  1429.2    2667
  1429.3 2667.01  1459.9 2669.24  1618.1 2672.56  1679.1 2671.34  1778.3 2673.23
  1790.8 2672.81  1865.5 2673.59    1907 2673.35    1936 2671.51  2064.6  2677.1
  2111.5 2678.38  2123.9 2679.39  2151.3 2678.94  2312.7 2682.05  2429.6 2682.73
  2487.9 2684.58  2551.2 2683.62  2562.6 2682.81  2590.1 2683.28  2596.8  2682.6
#Mann= 7 ,-1 , 0
       0     .12       0     243    .025       0   322.3    .045       0
  1429.2    .045       0  1429.3     .06       0 2230.19     .12       0
 2313.69     .06       0
Bank Sta=322.3,1429.2
XS Rating Curve= 0 ,0
Exp/Cntr=0.3,0.1