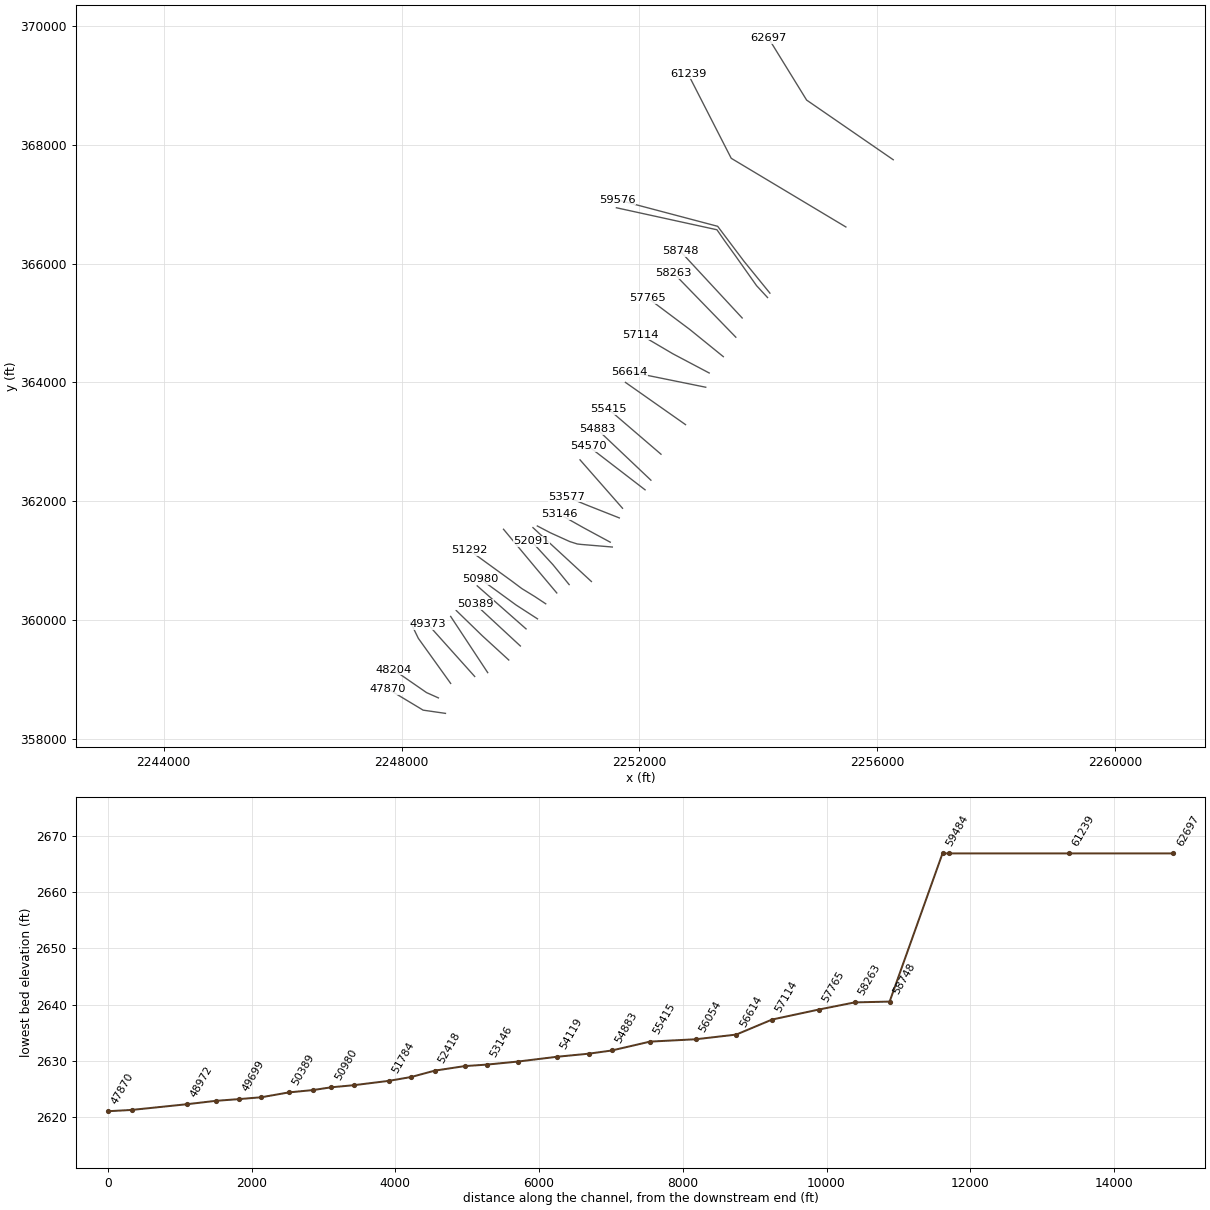
HEC-RAS study MEADOWCK1.prj: MEADOWCK1

--- MEADOWCK1.g01 (geometry) --- (continued)

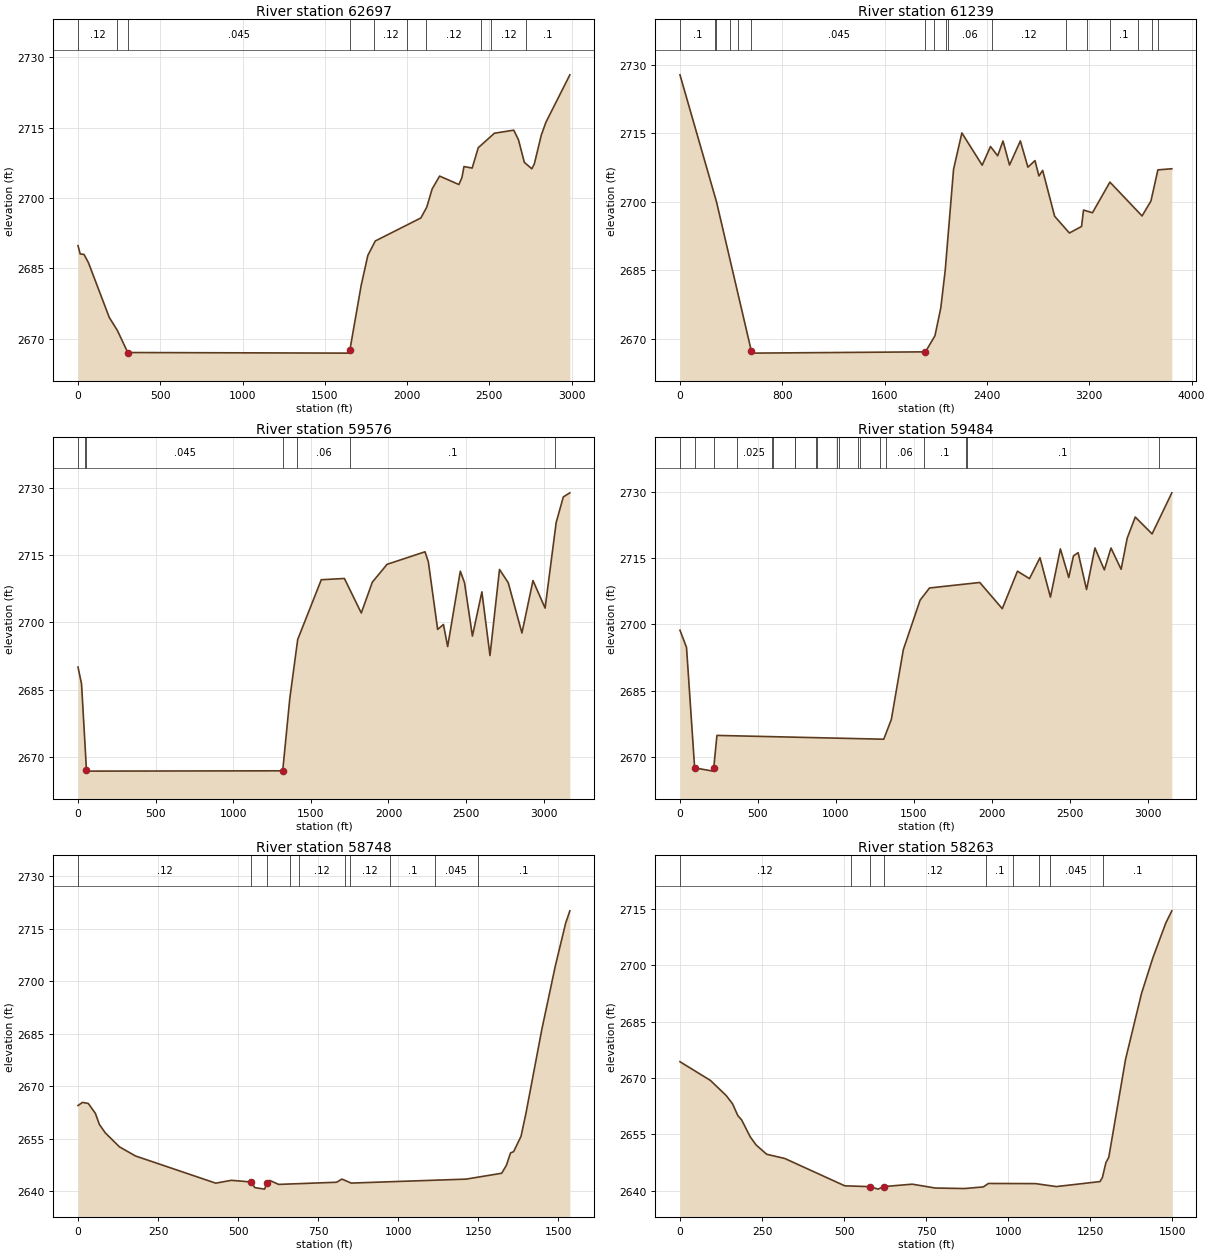
Type RM Length L Ch R = 1 ,62697   ,1445,1458.2,1531.1
XS GIS Cut Line= 3
2256267.76597588367746.6027855952254811.26325388368750.552587733
2254171.79591787369789.330545105
#Sta/Elev= 30
       0 2689.82    13.1 2688.07    36.7 2687.95    63.4  2686.2     190 2674.52
   238.7 2671.78   302.5 2667.04  1645.4 2666.91  1652.4 2667.63  1720.5 2681.32
    1761 2687.73  1806.4 2690.82  2083.4 2695.73  2119.3 2698.04  2151.9 2701.91
  2197.3 2704.66  2314.6 2702.86  2333.2 2704.37  2345.4 2706.69  2395.2 2706.37
  2432.2 2710.71  2530.4  2713.8    2648 2714.45  2676.6  2712.4  2712.3 2707.58
  2757.7 2706.22  2773.1 2707.29  2815.4 2713.42  2843.5 2716.15  2988.8 2726.25
#Mann= 10 ,-1 , 0
       0     .12       0   238.7    .025       0   302.5    .045       0
  1652.4     .06       0 1800.82     .12       0  2001.7     .06       0
  2112.7     .12       0 2450.65      .1       0 2508.49     .12       0
 2722.64      .1       0
Bank Sta=302.5,1652.4
XS Rating Curve= 0 ,0
Exp/Cntr=0.3,0.1

Type RM Length L Ch R = 1 ,61239   ,1593.4,1662.6,1151.7
XS GIS Cut Line= 3
2255471.17991306 366615.493537652253543.40227255367771.049297392
2252816.24276079369193.406669507
#Sta/Elev= 30
       0 2727.79   285.8 2699.98   558.4 2667.31   562.7 2666.91  1919.2 2667.19
  1993.4 2670.72  2038.8  2676.8  2073.6 2685.07  2138.7 2707.14  2203.7 2715.08
  2362.5 2708.02  2427.3 2712.11  2483.4 2710.08  2525.3 2713.31  2576.2 2708.06
  2660.9 2713.33  2719.9 2707.59  2775.1 2709.02  2806.3 2705.66  2835.2 2706.89
  2928.9 2696.85  3044.1 2693.19  3139.2 2694.62  3154.7 2698.21  3224.6 2697.62
    3361 2704.32  3612.3 2696.92  3681.6 2700.18  3736.1    2707    3845 2707.24
#Mann= 17 ,-1 , 0
       0      .1       0  271.04     .12       0  278.83      .1       0
  392.93     .12       0     455    .025       0   558.4    .045       0
  1919.2     .05       0 1988.27     .06       0 2082.72    .025       0
 2095.19     .06       0 2441.25     .12       0 3014.72    .055       0
 3183.07     .12       0 3359.26      .1       0 3576.98     .12       0
 3686.49      .1       0 3736.46     .12       0
Bank Sta=558.4,1919.2
XS Rating Curve= 0 ,0
Exp/Cntr=0.3,0.1

Type RM Length L Ch R = 1 ,59576   ,86.5,92.2,93.5
XS GIS Cut Line= 4
2254194.31107572365501.8228647262253758.20007131366037.933997229
 2253315.4056813366626.6775703882251632.29126538367071.975236222
#Sta/Elev= 30
       0 2690.06    22.8 2686.32    54.3 2667.23    57.7 2666.91  1318.8 2666.98
  1364.5 2683.09  1415.4  2696.2  1567.3  2709.5  1716.3 2709.78    1825  2702.1
  1896.2 2708.96  1991.2 2712.93  2235.6 2715.72  2257.1 2713.49    2317 2698.45
  2354.4 2699.55  2381.5 2694.62    2463  2711.4  2490.1 2708.84    2541 2696.97
  2602.1  2706.8  2654.2 2692.64  2715.5 2711.79  2771.8 2708.84    2860 2697.65
  2931.3 2709.32  3009.3 2703.19  3080.6 2722.23  3126.6 2727.93  3168.8 2728.84
#Mann= 7 ,-1 , 0
       0     .06       0   48.23    .025       0    54.3    .045       0
  1318.8      .1       0 1408.44     .06       0 1753.59      .1       0
 3073.99     .12       0
Bank Sta=54.3,1318.8
XS Rating Curve= 0 ,0
Exp/Cntr=0.3,0.1

Type RM Length L Ch R = 1 ,59484   ,740.1,735.6,748
XS GIS Cut Line= 6
2254154.40367521365427.7488658882253969.68160371365627.748793975
2253614.12588438366130.5266598172253428.01470806366388.859804556
2253303.42440605 366568.441794472251612.84675047366938.641841471
#Sta/Elev= 30
       0  2698.7      42 2694.82   94.062667.648   211.8 2666.91   216.3 2667.55
   237.2 2674.97  1307.4 2674.11  1356.1 2678.58    1433 2694.33  1540.5 2705.49
  1600.9 2708.24  1923.4 2709.48  2067.8 2703.57  2165.2 2712.03  2242.4 2710.35
  2309.6 2715.06  2376.8 2706.18  2440.6 2717.06  2494.3  2710.6  2524.5 2715.48
  2554.5 2716.21  2608.5 2707.88  2662.2 2717.27  2722.7 2712.32  2765.2 2717.26
  2830.2 2712.46  2869.1 2719.46  2920.9 2724.25  3028.9 2720.44  3155.6 2729.71
#Mann= 20 ,-1 , 0
       0     .06       0   94.06    .045       0   216.3     .06       0
  365.82    .025       0  588.96     .06       0   598.9      .1       0
     735    .025       0  735.63      .1       0  871.11    .055       0
  877.08      .1       0 1007.99    .025       0 1017.66      .1       0
 1144.98    .055       0 1158.16    .025       0 1280.68      .1       0
 1322.37     .06       0 1566.92      .1       0 1831.93     .12       0
 1840.15      .1       0 3073.27     .12       0
Bank Sta=94.06,216.3
XS Rating Curve= 0 ,0
Exp/Cntr=0.3,0.1

Type RM Length L Ch R = 1 ,58748   ,473.1,484.9,465.7
XS GIS Cut Line= 2
2253727.64435814365084.1839362232252684.24158931366210.919871733
#Sta/Elev= 30
       0 2664.44      14 2665.34    32.1 2665.04    54.3  2662.2    66.9 2659.01
    85.5  2656.6   129.6 2652.62   179.5 2650.02   429.9 2642.25     479 2643.06
   540.5 2642.59   552.1 2640.97   582.3 2640.54   590.8 2642.31   598.5 2643.03
   626.4 2641.89   807.5 2642.51   824.2 2643.41   853.1 2642.27  1211.5  2643.4
  1322.9 2645.08  1337.6 2647.37  1350.5  2650.9    1360 2651.25  1383.2 2655.64
  1398.8 2662.32  1448.3 2686.26    1490 2704.23  1522.5 2716.58  1535.7 2720.12
#Mann= 10 ,-1 , 0
       0     .12       0   540.5    .045       0   590.8     .12       0
  662.65      .1       0  691.17     .12       0  832.74      .1       0
  849.06     .12       0  975.08      .1       0 1115.01    .045       0
  1247.5      .1       0
Bank Sta=540.5,590.8
XS Rating Curve= 0 ,0
Exp/Cntr=0.3,0.1

Type RM Length L Ch R = 1 ,58263   ,493.6,498.7,496.2
XS GIS Cut Line= 2
2253621.04713039364760.5727068042252577.29724939365835.572853386
#Sta/Elev= 30
       0 2674.33    92.7 2669.35   140.7 2665.33     160 2663.15   176.2 2659.99
   187.8 2658.84   213.9 2654.34   231.9 2652.16   264.2 2649.68     319 2648.57
     502 2641.28   579.7 2641.06   603.1  2640.4   621.7 2641.08   707.4 2641.72
     778 2640.69   867.5 2640.56     924 2640.99   939.6 2641.91  1082.7 2641.87
  1146.7 2641.08  1279.3 2642.41  1286.7 2643.48  1297.6 2647.48  1306.2 2648.86
  1357.3 2674.96  1405.9 2692.49  1440.7 2702.05  1480.2 2711.33  1498.3 2714.51
#Mann= 9 ,-1 , 0
       0     .12       0  519.82      .1       0   579.7    .045       0
   621.7     .12       0  931.07      .1       0  1014.9     .12       0
 1093.11      .1       0 1126.13    .045       0 1288.18      .1       0
Bank Sta=579.7,621.7
XS Rating Curve= 0 ,0
Exp/Cntr=0.3,0.1

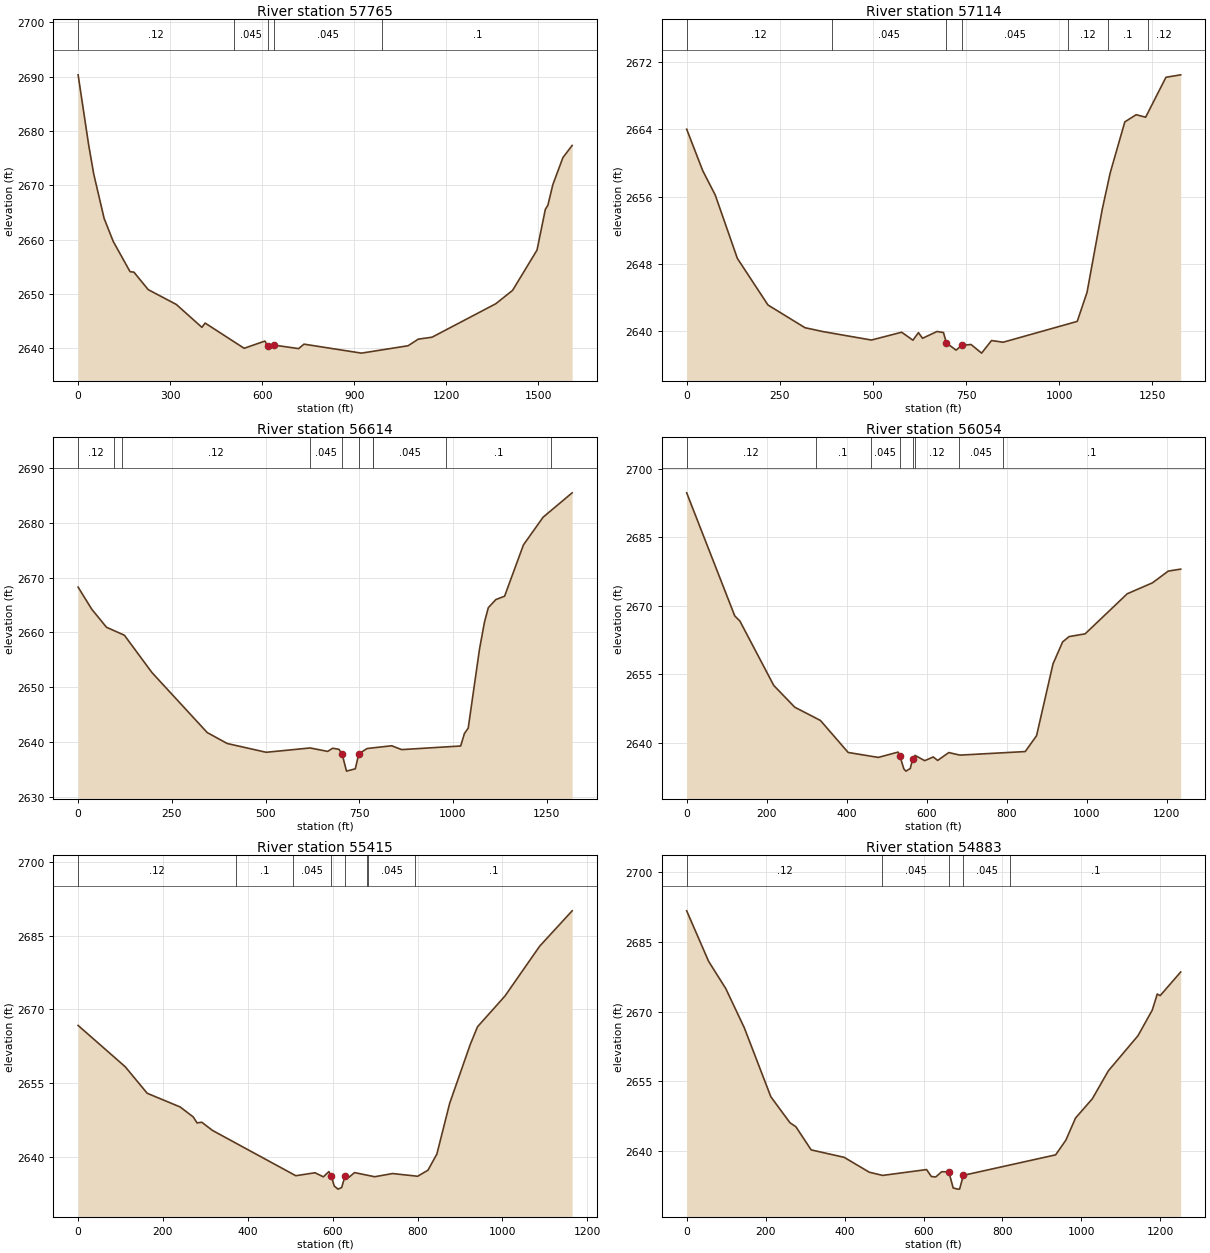
Type RM Length L Ch R = 1 ,57765   ,615.7,651.1,640.7
XS GIS Cut Line= 3
2253410.63055646364433.4893714792252848.13069722364889.739443228
2252139.79714014365420.989364982
#Sta/Elev= 30
       0 2690.32      34 2677.56    50.9 2672.07    84.7 2663.92   114.3 2659.69
   169.2 2654.12   181.9 2654.02   228.4 2650.81   320.1 2648.08   403.4 2643.87
   413.9 2644.66     541 2640.02   608.6 2641.35  617.772640.454   622.2 2639.94
  639.292640.602   718.4 2639.96     736 2640.78   923.3 2639.13  1075.3 2640.49
  1108.2  2641.7  1153.3 2642.06  1360.8 2648.21  1415.6 2650.67  1495.3 2658.09
  1522.4 2665.58  1530.6 2666.32  1546.8 2670.12  1579.6  2675.1  1609.7 2677.33
#Mann= 5 ,-1 , 0
       0     .12       0  506.29    .045       0  617.77    .045       0
  639.29    .045       0  991.66      .1       0
Bank Sta=617.77,639.29
XS Rating Curve= 0 ,0
Exp/Cntr=0.3,0.1

Type RM Length L Ch R = 1 ,57114   ,484,499.2,496.7
XS GIS Cut Line= 3
2253173.13070339364158.4895933872252562.71394522  364481.4062704
2252014.79739013364804.322947398
#Sta/Elev= 30
       0 2664.03    43.3 2659.07    76.7 2656.19   136.1 2648.64   218.4 2643.08
   317.7 2640.38   365.5 2639.92   496.1 2638.91   577.3 2639.84   607.5 2638.89
   622.3 2639.79   633.4 2639.12   672.3 2639.93   689.6  2639.8   697.5 2638.56
   723.4 2637.71   738.6 2638.27   763.6 2638.38   791.9 2637.35   818.6 2638.85
   849.8 2638.65  1048.7 2641.13  1075.1  2644.6  1115.8 2654.47  1137.4 2658.85
  1176.5  2664.9  1206.9 2665.76  1232.4 2665.46    1287 2670.22  1326.6 2670.51
#Mann= 7 ,-1 , 0
       0     .12       0     389    .045       0   697.5    .045       0
   738.6    .045       0 1024.49     .12       0 1131.09      .1       0
  1237.7     .12       0
Bank Sta=697.5,738.6
XS Rating Curve= 0 ,0
Exp/Cntr=0.3,0.1

Type RM Length L Ch R = 1 ,56614   ,556,560.6,536
XS GIS Cut Line= 2
2253114.79715864363918.9060830622251823.13045064364181.406214222
#Sta/Elev= 30
       0 2668.26    36.4 2664.23    75.7 2660.94   123.5 2659.48   197.1 2652.66
   344.5 2641.71     398 2639.71   501.8 2638.11     619  2638.9   665.9 2638.27
   679.2 2638.85     696 2638.65   704.5 2637.73   716.1 2634.67   739.5 2635.09
     749 2637.85   771.3  2638.8   836.6  2639.3   863.1  2638.6  1020.7 2639.26
  1030.8 2641.55  1040.8 2642.52  1070.9 2656.93  1084.3 2661.91  1094.4 2664.51
  1114.5 2665.99  1137.9 2666.61  1188.1 2675.97  1240.6 2681.03  1318.1 2685.48
#Mann= 10 ,-1 , 0
       0     .12       0   95.36      .1       0  116.92     .12       0
  618.18    .045       0   704.5    .045       0     749    .045       0
  786.93     .12       0   787.3    .045       0  982.39      .1       0
 1260.76     .12       0
Bank Sta=704.5,749
XS Rating Curve= 0 ,0
Exp/Cntr=0.3,0.1

Type RM Length L Ch R = 1 ,56054   ,631.7,638.8,630.7
XS GIS Cut Line= 2
2252775.21384831363289.7393623892251764.79723397364000.156248644
#Sta/Elev= 30
       0  2694.7   120.2 2667.79     133 2666.67   217.7 2652.58   270.2 2647.82
   334.4 2644.92   403.8 2637.92   479.1 2636.84   528.6    2638   533.3 2637.06
     543 2634.33   548.1 2633.84     559  2634.4   565.2 2636.59     571 2637.28
   595.1 2636.13   616.5 2636.94   627.5 2636.18   655.3  2637.9   683.3 2637.34
   846.5 2638.12   874.8 2641.59   915.9 2657.29     940  2662.1     956 2663.26
   996.2 2663.86  1101.4 2672.62  1164.4 2675.01    1204 2677.58  1235.2 2678.02
#Mann= 8 ,-1 , 0
       0     .12       0  322.62      .1       0  459.89    .045       0
   533.3    .045       0   565.2    .045       0  570.31     .12       0
  680.72    .045       0  791.13      .1       0
Bank Sta=533.3,565.2
XS Rating Curve= 0 ,0
Exp/Cntr=0.3,0.1

Type RM Length L Ch R = 1 ,55415   ,518.3,532.4,516.9
XS GIS Cut Line= 2
2252362.71401714 362791.822707312251479.38048197363550.156164393
#Sta/Elev= 30
       0 2666.72   110.9 2658.33   162.8 2652.92   240.6 2650.13   271.2 2648.11
   280.3 2646.89   291.4 2647.03   316.5 2645.37     513 2636.15   558.3 2636.75
   577.9 2635.92   590.9 2636.98   596.8 2636.07   603.6 2634.05   612.5 2633.42
   621.1 2633.75   629.3 2636.18   638.6 2635.86   651.4 2636.78     699 2635.94
     741 2636.59   800.1 2636.04   824.4 2637.27   845.4 2640.55   875.6 2650.88
   923.8 2662.79   941.1 2666.44    1006 2672.72  1087.7 2682.85  1164.2 2690.04
#Mann= 8 ,-1 , 0
       0     .12       0     373      .1       0  505.23    .045       0
   596.8    .045       0   629.3    .045       0  680.82     .07       0
  683.14    .045       0  794.91      .1       0
Bank Sta=596.8,629.3
XS Rating Curve= 0 ,0
Exp/Cntr=0.3,0.1

Type RM Length L Ch R = 1 ,54883   ,301.7,313.1,300.2
XS GIS Cut Line= 2
2252192.97419913362354.9617043882251284.64104205 363216.07284306
#Sta/Elev= 30
       0 2691.71    55.5 2680.86    99.1 2674.98     146 2666.55   213.3  2651.7
   261.8 2646.11   276.6 2645.27   315.4 2640.28     399 2638.68   462.6 2635.48
   496.4 2634.79   607.8 2636.05   619.9 2634.55     631 2634.46   646.1 2635.59
   664.2 2635.54   675.1  2632.1   686.7 2631.84   691.4 2631.85     701 2634.81
   934.7 2639.21   960.6 2642.37   985.1 2647.13  1027.9  2651.3  1068.2 2657.28
  1143.4 2664.85  1179.5 2670.35  1192.2 2673.81  1199.6 2673.47  1251.6 2678.56
#Mann= 5 ,-1 , 0
       0     .12       0  496.01    .045       0   664.2    .045       0
     701    .045       0     820      .1       0
Bank Sta=664.2,701
XS Rating Curve= 0 ,0
Exp/Cntr=0.3,0.1

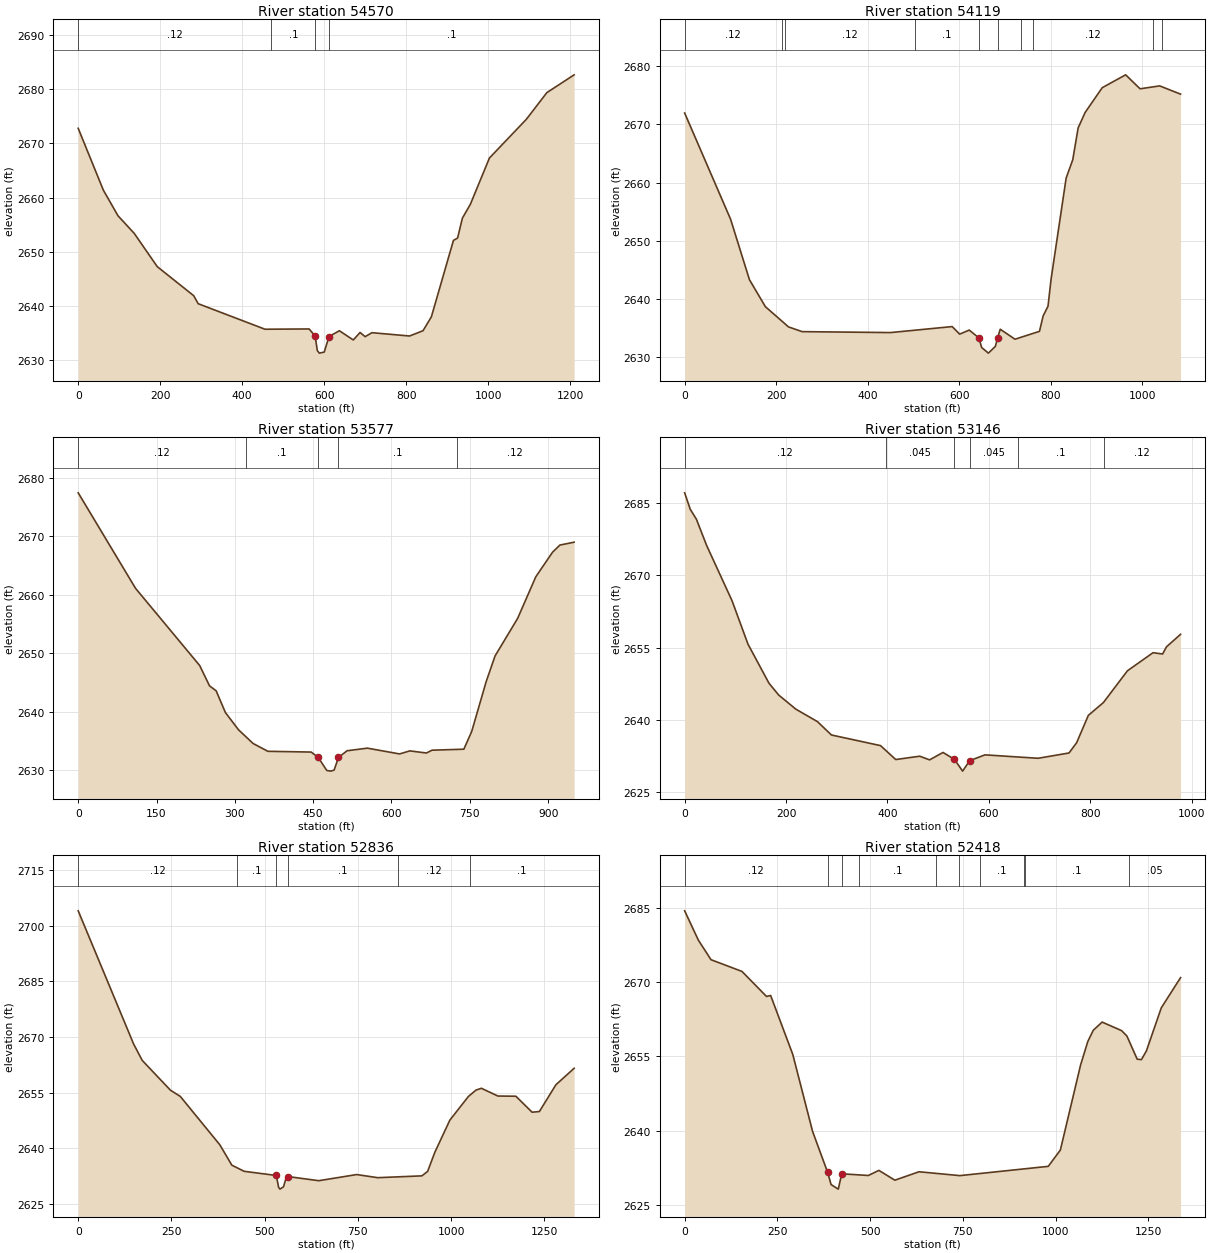
Type RM Length L Ch R = 1 ,54570   ,444.2,450.2,433.1
XS GIS Cut Line= 2
2252094.90943463362192.8921466472251136.57604948362930.392312065
#Sta/Elev= 30
       0 2672.77    61.3 2661.36    96.9 2656.64   136.7 2653.37   192.8 2647.24
   281.6 2641.88   292.6  2640.4   455.5 2635.69   563.1 2635.74   577.8 2634.43
   583.1 2631.74     588 2631.28   599.9 2631.47   611.6 2634.34   636.9 2635.41
   670.8 2633.71   687.3 2635.09   699.7 2634.32   716.3 2635.05   808.1 2634.44
   840.9 2635.42   861.2 2637.98     915 2652.08   925.1 2652.52   936.8 2656.18
   956.4 2658.77  1002.7 2667.28    1093 2674.45  1142.7 2679.35  1209.3 2682.64
#Mann= 4 ,-1 , 0
       0     .12       0  471.01      .1       0   577.8    .045       0
   611.6      .1       0
Bank Sta=577.8,611.6
XS Rating Curve= 0 ,0
Exp/Cntr=0.3,0.1

Type RM Length L Ch R = 1 ,54119   ,528.8,542.3,543.9
XS GIS Cut Line= 2
2251715.74287014361882.4754446452251001.15965363362697.058789223
#Sta/Elev= 30
       0 2671.96   100.4 2653.71   141.6 2643.33   176.4  2638.7     227 2635.22
   256.8 2634.41     450 2634.25   584.6 2635.28   600.9 2633.98   621.8 2634.68
   642.8 2633.34     649 2631.68   663.7 2630.72   678.9 2631.88   683.8 2633.34
   689.6 2634.82   721.8 2633.11   775.3 2634.46   783.3 2637.11   793.9 2638.77
   800.8  2643.5   833.6  2660.8     848 2663.92   859.8 2669.41   875.2 2672.07
   912.4 2676.31   963.6 2678.52   995.1 2676.12    1038 2676.62  1083.6  2675.2
#Mann= 10 ,-1 , 0
       0     .12       0  212.58      .1       0  218.75     .12       0
  502.86      .1       0   642.8    .045       0   683.8    .045       0
  735.58      .1       0   760.4     .12       0 1024.32      .1       0
 1042.85     .12       0
Bank Sta=642.8,683.8
XS Rating Curve= 0 ,0
Exp/Cntr=0.3,0.1

Type RM Length L Ch R = 1 ,53577   ,430.1,431.3,418.1
XS GIS Cut Line= 3
 2251661.5763118 361719.97544156 2251103.2427828361940.808989391
 2250780.3261058362074.142384142
#Sta/Elev= 30
       0 2677.45   109.9 2661.11   232.7 2647.92   251.5 2644.45   264.2  2643.6
   281.9 2639.89   307.1 2636.93   334.9  2634.6   363.2 2633.26   446.2 2633.13
   459.8  2632.2   476.1 2629.98   484.1 2629.87   490.2 2630.06   498.4  2632.2
   514.9 2633.35   553.7  2633.8   615.5 2632.81   635.1 2633.33     667 2632.97
   677.7 2633.45   738.6 2633.62   753.7 2636.67   781.3 2645.16   798.4 2649.57
   841.6 2655.98   876.4  2663.1   908.4 2667.29   922.6 2668.52   949.8 2669.01
#Mann= 5 ,-1 , 0
       0     .12       0  321.03      .1       0   459.8    .045       0
   498.4      .1       0  724.61     .12       0
Bank Sta=459.8,498.4
XS Rating Curve= 0 ,0
Exp/Cntr=0.3,0.1

Type RM Length L Ch R = 1 ,53146   ,304.4,310.1,315.9
XS GIS Cut Line= 3
2251509.49295455361311.6422687322251055.32621197361557.475438476
2250653.24302664361784.558973804
#Sta/Elev= 30
       0 2687.16    11.1 2683.73    23.2 2681.67    43.2 2676.26    93.4 2664.76
   124.9 2655.72   166.3  2647.6   185.4 2645.15   219.3 2642.21   261.9 2639.62
   289.5 2636.84   386.4 2634.63   416.3 2631.74   463.7 2632.43   483.1 2631.67
   509.6 2633.21   532.1 2631.78   548.3 2629.33   562.2  2631.5   592.4 2632.71
   697.1    2632   758.2  2633.1   773.2 2635.24   796.3 2640.92     826 2643.58
   873.4 2650.18   923.9 2653.94   942.8 2653.67   950.3 2655.15   978.2 2657.76
#Mann= 6 ,-1 , 0
       0     .12       0  397.13    .045       0   532.1    .045       0
   562.2    .045       0  657.95      .1       0  826.17     .12       0
Bank Sta=532.1,562.2
XS Rating Curve= 0 ,0
Exp/Cntr=0.3,0.1

Type RM Length L Ch R = 1 ,52836   ,417.5,417.6,406.5
XS GIS Cut Line= 6
 2251544.1139483361230.2621821462251028.83610748361273.317542225
2250955.22503422361281.6508588942250828.83617939361321.928665474
2250501.05829164361470.5399168132250283.19061714361584.595791057
#Sta/Elev= 30
       0 2703.95   148.6  2668.1   171.7 2663.69   247.4 2655.67   273.7 2654.01
   379.7 2640.99     412  2635.5   444.9 2633.86   531.2 2632.73   537.2 2629.59
   540.9 2629.06   550.4 2629.69     557 2631.92  561.272632.453     645 2631.33
   746.6 2632.98   803.1 2632.14   921.4 2632.63   936.8 2633.83   956.1 2638.96
   996.4 2647.62    1046 2653.98  1066.5 2655.71  1080.9  2656.2  1125.2 2654.11
  1173.4 2654.06  1216.9 2649.76  1236.4 2649.94  1280.8 2657.15  1329.6 2661.58
#Mann= 6 ,-1 , 0
       0     .12       0  425.54      .1       0   531.2    .045       0
  561.27      .1       0  858.02     .12       0 1050.91      .1       0
Bank Sta=531.2,561.27
XS Rating Curve= 0 ,0
Exp/Cntr=0.3,0.1

Type RM Length L Ch R = 1 ,52418   ,327.7,326.7,325.6
XS GIS Cut Line= 3
2251192.31412697360650.0776469712250760.60731322361048.771731481
2250209.54640748361556.662119895
#Sta/Elev= 30
       0 2684.33      37 2678.42    71.1 2674.48   154.5 2672.12   220.8 2667.07
   231.8 2667.28   291.5  2655.4   344.9 2639.89  385.632631.606   394.8 2629.17
   414.2 2628.25  423.532631.339   495.3    2631   523.7 2632.03   566.8 2630.05
   631.8 2631.75   741.9 2630.97   980.4 2632.84    1013 2636.13  1067.5 2653.26
  1086.9 2657.98  1101.8 2660.27  1125.6 2661.91  1178.1 2660.19  1192.4  2659.1
  1220.2 2654.43  1231.6 2654.35    1245 2656.11  1285.1 2664.78  1337.1 2670.87
#Mann= 10 ,-1 , 0
       0     .12       0  385.63    .045       0  423.53     .12       0
   470.5      .1       0  677.76     .12       0  739.58    .045       0
   796.8      .1       0  914.79     .12       0  916.39      .1       0
 1197.47     .05       0
Bank Sta=385.63,423.53
XS Rating Curve= 0 ,0
Exp/Cntr=0.3,0.1

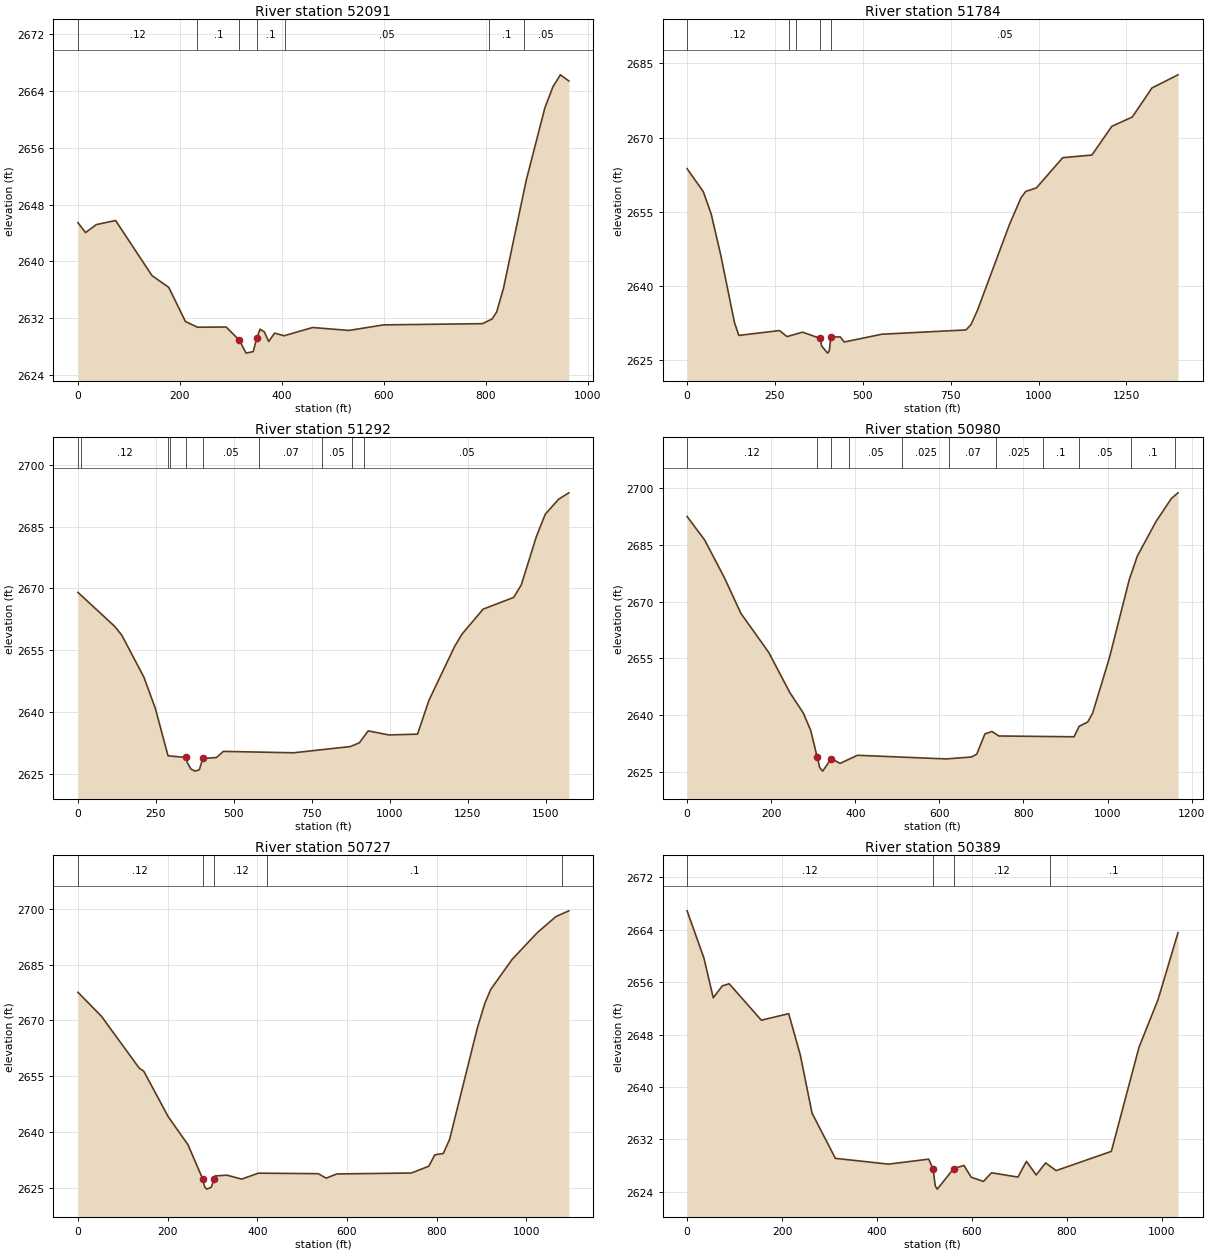
Type RM Length L Ch R = 1 ,52091   ,298.1,307.4,302
XS GIS Cut Line= 3
2250818.33357573 360598.224732312250545.76423897 360933.29427214
2250186.38930155361323.919147059
#Sta/Elev= 30
       0 2645.45    14.9 2644.06    35.9 2645.18    73.8 2645.76   145.2 2638.02
   178.1 2636.36   210.8 2631.56   234.5 2630.76   290.7 2630.79   316.7 2628.92
   329.7 2627.12   343.7 2627.34   350.7  2629.2   357.2 2630.49   365.6  2630.1
   374.1 2628.75   385.7 2629.93   404.3 2629.56   460.1 2630.72   531.5 2630.31
   599.5 2631.09   793.2 2631.26   812.3 2631.92   821.2 2632.92   834.6 2636.26
   879.2 2651.43   915.7 2661.59   931.5 2664.55   946.1 2666.23   962.7 2665.37
#Mann= 7 ,-1 , 0
       0     .12       0  233.61      .1       0   316.7    .045       0
   350.7      .1       0  406.41     .05       0  806.11      .1       0
  873.86     .05       0
Bank Sta=316.7,350.7
XS Rating Curve= 0 ,0
Exp/Cntr=0.3,0.1

Type RM Length L Ch R = 1 ,51784   ,459.5,491.7,448.8
XS GIS Cut Line= 3
2250610.00033097360457.5996854752250262.77792831360870.794069067
2249714.71309254361529.356471889
#Sta/Elev= 30
       0 2663.72      46 2659.09    68.5 2654.58    95.6 2646.31   134.7 2632.64
   147.1 2630.02   262.8    2631   284.2 2629.78   328.5 2630.68   378.5 2629.42
   382.8 2627.87   399.9 2626.44   404.2 2626.84   409.2 2629.69   435.6 2629.72
     447 2628.69   554.1 2630.26   793.6 2631.13   807.5 2632.19   826.2 2635.13
     917 2652.42   949.6  2657.8   963.3 2659.12   993.8 2659.84  1068.5 2665.94
  1151.7 2666.48  1208.2 2672.28  1266.5 2674.16  1322.4 2680.03  1396.5 2682.69
#Mann= 5 ,-1 , 0
       0     .12       0  290.16      .1       0  310.68     .05       0
   378.5    .045       0   409.2     .05       0
Bank Sta=378.5,409.2
XS Rating Curve= 0 ,0
Exp/Cntr=0.3,0.1

Type RM Length L Ch R = 1 ,51292   ,308.4,311.7,308.4
XS GIS Cut Line= 6
 2250424.3405973360275.2558900562250239.96563797360397.130974397
2250023.29874846360530.4643691482249847.79678676 360661.93355137
2249190.30179302361139.255379076 2249134.1989149361174.465947743
#Sta/Elev= 30
       0 2669.02   118.4 2660.73   140.9 2658.59   211.7  2648.4   248.2 2640.84
   288.7 2629.38   346.7 2628.97   350.7  2627.7   362.1 2626.16   375.9 2625.66
   389.1    2626   400.2 2628.74   443.7 2628.96   466.2 2630.45     691 2630.11
   873.2 2631.62   901.9 2632.53   930.3 2635.43   996.5 2634.44  1088.4 2634.63
  1124.9 2642.82  1207.1 2655.88    1231 2658.91  1298.7 2664.96  1396.5  2667.8
  1420.9 2670.83  1469.5 2682.61  1497.9    2688  1541.1 2691.66  1573.4 2693.18
#Mann= 10 ,-1 , 0
       0      .1       0   10.95     .12       0  289.06      .1       0
  294.38     .05       0   346.7    .045       0   400.2     .05       0
  580.36     .07       0  781.08     .05       0  879.34     .07       0
  918.35     .05       0
Bank Sta=346.7,400.2
XS Rating Curve= 0 ,0
Exp/Cntr=0.3,0.1

Type RM Length L Ch R = 1 ,50980   ,253.3,253.1,246.2
XS GIS Cut Line= 3
 2250286.1459918  360021.52345792249926.77105439360254.162100226
2249329.54882364360689.925992474
#Sta/Elev= 30
       0 2692.46    41.9 2686.23    88.8 2676.29   127.8 2666.93   194.3 2656.58
   244.2 2646.03   276.4 2640.61   294.1 2635.99  309.172629.079   315.4 2626.23
   322.5 2625.29   342.8 2628.59   363.7 2627.33   405.3 2629.47   615.6 2628.51
   676.5 2629.02   688.7 2629.75   708.2 2635.09   724.9 2635.75   741.5 2634.56
   920.2 2634.35   932.4 2637.12   952.7 2638.25   964.3 2640.54  1004.6 2655.29
  1051.5 2675.78  1070.5 2681.97  1115.2 2691.15  1151.7  2697.2  1167.4  2698.7
#Mann= 11 ,-1 , 0
       0     .12       0  309.17    .045       0   342.8     .12       0
  384.44     .05       0  511.79    .025       0  623.17     .07       0
  734.55    .025       0  845.93      .1       0  932.73     .05       0
 1054.93      .1       0 1160.41     .05       0
Bank Sta=309.17,342.8
XS Rating Curve= 0 ,0
Exp/Cntr=0.3,0.1

Type RM Length L Ch R = 1 ,50727   ,333.2,338.4,336
XS GIS Cut Line= 2
 2250093.4377158359853.1205794812249272.25727156360577.078777224
#Sta/Elev= 30
       0 2677.55    52.4 2671.13   136.7 2657.22   146.7 2656.42   201.2 2644.23
   245.3 2636.71   277.9 2627.62   282.5 2625.42   287.2  2624.8   297.3 2625.31
   303.4 2627.49   305.8 2628.34   332.3 2628.54     365 2627.48   402.3 2629.08
   535.9 2628.94   553.5 2627.74   577.2 2628.87   743.4 2629.12   782.3 2630.93
   795.9 2633.99   814.8 2634.36   828.8 2638.14   890.8 2668.06   907.8 2674.75
   920.6 2678.34   968.2 2686.37  1024.8 2693.59  1065.9 2697.85  1094.7 2699.39
#Mann= 5 ,-1 , 0
       0     .12       0   277.9    .045       0   303.4     .12       0
  421.97      .1       0 1079.55     .05       0
Bank Sta=277.9,303.4
XS Rating Curve= 0 ,0
Exp/Cntr=0.3,0.1

Type RM Length L Ch R = 1 ,50389   ,378.4,381.1,369
XS GIS Cut Line= 2
2249997.95168631359564.9259458932249239.27111705360268.051180065
#Sta/Elev= 30
       0  2666.9    35.5 2659.67    55.1 2653.62    74.4 2655.44    88.8 2655.75
   156.4 2650.19   214.1 2651.19   238.5 2644.89   263.3 2635.99   312.5 2629.08
   424.4  2628.2   509.1 2628.96   518.4 2627.44   518.4  2627.4     523 2624.85
   527.2 2624.38   561.8 2627.52   583.4    2628   598.8 2626.19   624.6 2625.56
   641.4 2626.88   697.2 2626.22   715.1 2628.63   735.6 2626.54   755.4 2628.39
   777.7 2627.21     894 2630.15   952.2 2646.04   992.5 2653.36  1034.4 2663.55
#Mann= 4 ,-1 , 0
       0     .12       0   518.4    .045       0   561.8     .12       0
  765.75      .1       0
Bank Sta=518.4,561.8
XS Rating Curve= 0 ,0
Exp/Cntr=0.3,0.1

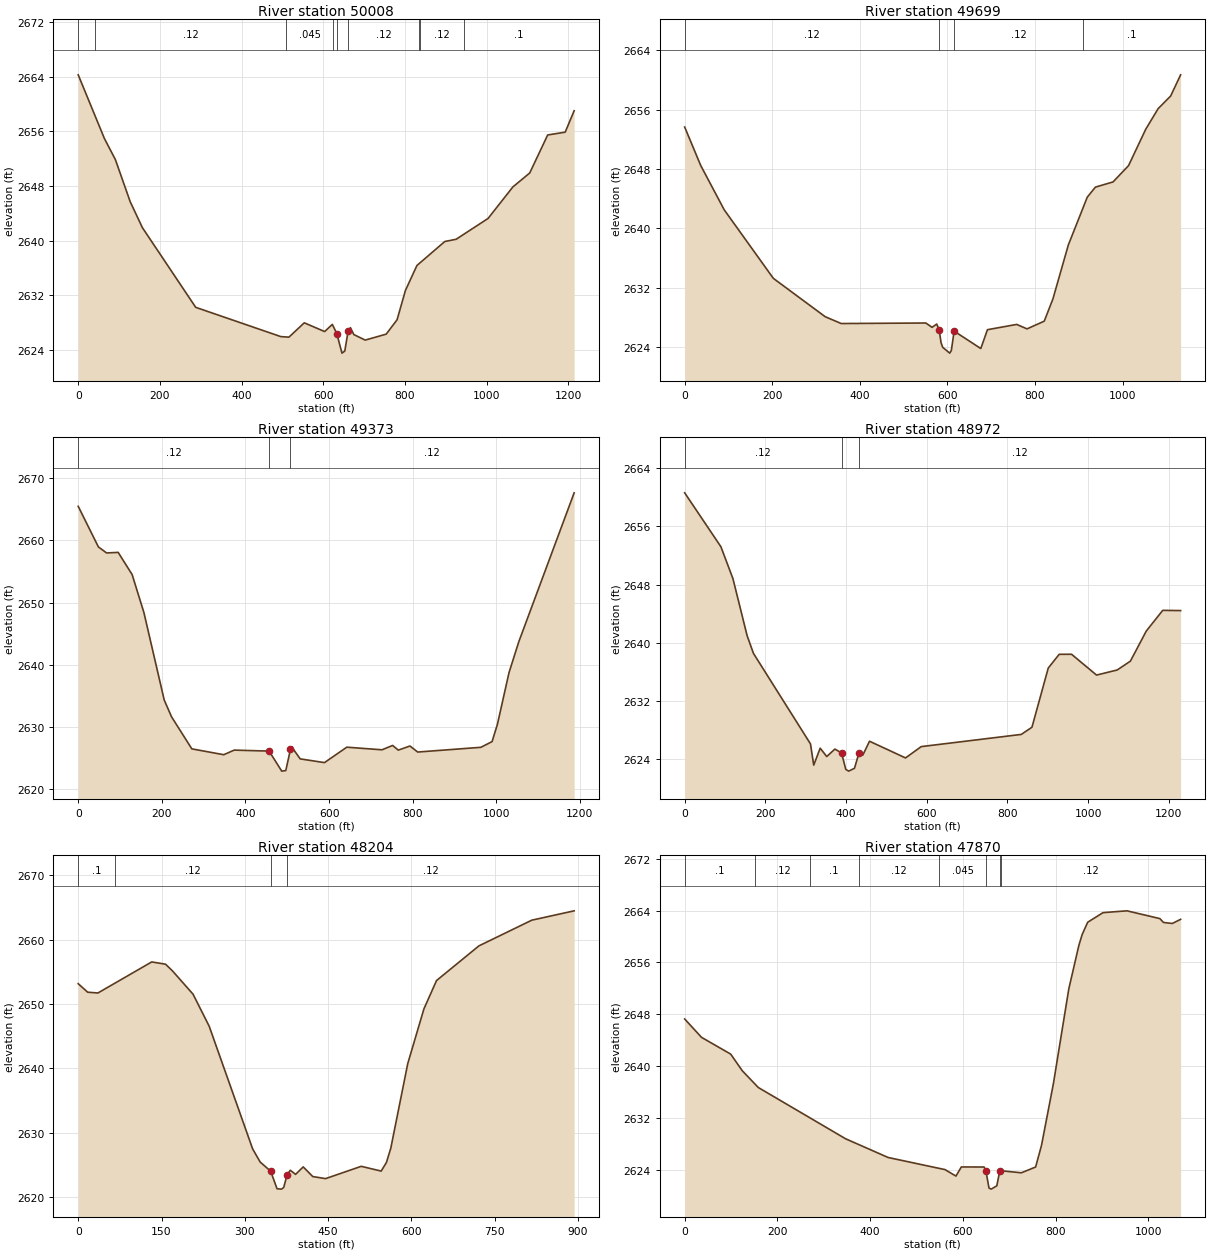
Type RM Length L Ch R = 1 ,50008   ,308.2,309.3,303.7
XS GIS Cut Line= 3
2249802.98685314359329.2672964782249357.15375531  359737.6007974
2248919.65364605360162.600931644
#Sta/Elev= 30
       0 2664.29    64.3 2654.94      91 2651.88   127.4 2645.69   157.2  2641.9
   287.7 2630.23   496.2 2625.94     516 2625.86   553.6 2627.96   603.5 2626.68
   622.3 2627.73   633.2 2626.39   645.9 2623.52   652.8 2623.82     661 2626.77
   666.6 2627.25   674.9 2626.24   702.8 2625.43   754.2  2626.3   780.9 2628.41
   801.3  2632.7   829.5 2636.36   897.7 2639.87   925.5  2640.2  1003.7 2643.25
  1064.5 2647.87  1105.7 2649.91  1149.7 2655.48  1192.6 2655.89  1214.5 2659.03
#Mann= 9 ,-1 , 0
       0      .1       0   40.42     .12       0  509.58    .045       0
  624.24     .12       0   633.2    .045       0     661     .12       0
  834.97      .1       0  837.66     .12       0   945.2      .1       0
Bank Sta=633.2,661
XS Rating Curve= 0 ,0
Exp/Cntr=0.3,0.1

Type RM Length L Ch R = 1 ,49699   ,312.2,325.6,319.3
XS GIS Cut Line= 2
2249448.82023863359116.7673933952248825.90350547360062.600803554
#Sta/Elev= 30
       0 2653.67    36.7 2648.48    90.4  2642.5   202.5 2633.27   320.9  2628.1
   357.5 2627.18   550.7 2627.25   564.9 2626.67   575.6 2627.11   581.4 2626.26
   585.4 2624.61   589.3 2623.97   605.2 2623.19   608.9 2623.53  615.332626.154
   676.2 2623.81   691.4 2626.35   758.2 2627.06   781.8 2626.46   821.1  2627.5
   840.7 2630.46   876.1 2637.77   919.3 2644.21   937.9 2645.57   978.2 2646.27
  1013.6 2648.47  1052.8 2653.37  1081.2 2656.15  1109.7 2657.85  1132.5 2660.71
#Mann= 4 ,-1 , 0
       0     .12       0   581.4    .045       0  615.33     .12       0
  910.38      .1       0
Bank Sta=581.4,615.33
XS Rating Curve= 0 ,0
Exp/Cntr=0.3,0.1

Type RM Length L Ch R = 1 ,49373   ,400.7,401.1,386.7
XS GIS Cut Line= 2
2249230.07034805 359052.184189232248438.40362431359935.517396316
#Sta/Elev= 30
       0 2665.47    48.3 2658.94    67.9 2657.97    95.6 2658.06     129 2654.49
   157.2 2648.37   205.7 2634.32   223.3 2631.61   271.8 2626.46   348.1 2625.52
   373.1 2626.26   456.6  2626.1   486.8 2622.88   496.5 2622.97   507.7 2626.39
   510.4  2626.8   530.9 2624.85     589 2624.25   642.4 2626.73   726.6 2626.31
     752 2627.01   765.6 2626.26   793.5 2626.92     812 2625.95   963.1 2626.71
   989.9 2627.63  1002.6 2630.39  1030.4 2638.72  1053.7 2643.67  1186.2 2667.64
#Mann= 3 ,-1 , 0
       0     .12       0   456.6    .045       0   507.7     .12       0
Bank Sta=456.6,507.7
XS Rating Curve= 0 ,0
Exp/Cntr=0.3,0.1

Type RM Length L Ch R = 1 ,48972   ,751.5,768.2,753.5
XS GIS Cut Line= 3
2248825.90350547358935.5174278172248282.15360872  359693.8508849
 2248152.9868723359960.517346308
#Sta/Elev= 30
       0 2660.64    89.8 2653.21   119.6 2648.82   154.9 2640.93   170.6  2638.5
   311.9 2626.03   319.9 2623.11   335.9 2625.44   352.2 2624.29   372.4 2625.32
  388.862624.787   399.4 2622.52   406.5 2622.28   420.9 2622.67   432.3 2624.82
   441.7  2624.5   458.2  2626.4   547.5  2624.1   586.4 2625.66   834.4 2627.34
   860.9 2628.33   901.3 2636.49   928.4 2638.38     959 2638.39    1021 2635.52
  1072.1 2636.22  1104.9 2637.44  1144.3 2641.59  1185.1 2644.44  1229.4 2644.41
#Mann= 3 ,-1 , 0
       0     .12       0  388.86    .045       0   432.3     .12       0
Bank Sta=388.86,432.3
XS Rating Curve= 0 ,0
Exp/Cntr=0.3,0.1

Type RM Length L Ch R = 1 ,48204   ,323.7,333.5,330.8
XS GIS Cut Line= 3
2248619.65358989 358691.76758723 2248419.6536618358781.350741386
2247865.48711923359164.683964223
#Sta/Elev= 30
       0 2653.14    17.1 2651.82    35.5  2651.7   132.4 2656.52   157.2 2656.17
   169.6 2655.14   206.8 2651.51   235.8 2646.55   314.1  2627.5   327.7 2625.46
   346.6 2624.04     358 2621.32     366 2621.26     370 2621.51   376.2  2623.5
   381.9 2624.19   391.4 2623.55   405.1 2624.71   422.4 2623.21   445.4 2622.89
   509.6  2624.8   545.5 2624.06     555  2625.4   562.9 2627.63   593.4 2640.75
   622.5 2649.23   645.2 2653.63   721.5 2659.01   816.8    2663     893 2664.45
#Mann= 4 ,-1 , 0
       0      .1       0   65.71     .12       0   346.6    .045       0
   376.2     .12       0
Bank Sta=346.6,376.2
XS Rating Curve= 0 ,0
Exp/Cntr=0.3,0.1

Type RM Length L Ch R = 1 ,47870   ,235.9,241.1,241.4
XS GIS Cut Line= 3
2248738.40368047358431.3507852262248363.40377431358485.517343566
2247771.73697864358841.767615303
#Sta/Elev= 30
       0 2647.27    36.3 2644.44    99.3 2641.85   124.2 2639.29   158.8  2636.7
   347.2 2628.79   438.7 2625.91   561.4 2624.04     585 2623.04   596.6 2624.45
   645.7 2624.44   649.5 2623.87   656.3 2621.19     661 2621.03   673.1 2621.54
   679.7 2623.88   726.1 2623.55   756.8 2624.44   769.5 2627.77   795.2 2637.32
   828.4 2651.92     850  2658.6   857.1 2660.28   869.1 2662.19   902.2 2663.67
   953.9 2663.95  1024.8 2662.75  1032.5 2662.16  1051.6    2662  1069.5 2662.64
#Mann= 8 ,-1 , 0
       0      .1       0  152.48     .12       0  269.29      .1       0
  374.85     .12       0  548.65    .045       0   649.5    .045       0
   679.7    .045       0  681.91     .12       0
Bank Sta=649.5,679.7
XS Rating Curve= 0 ,0
Exp/Cntr=0.5,0.3