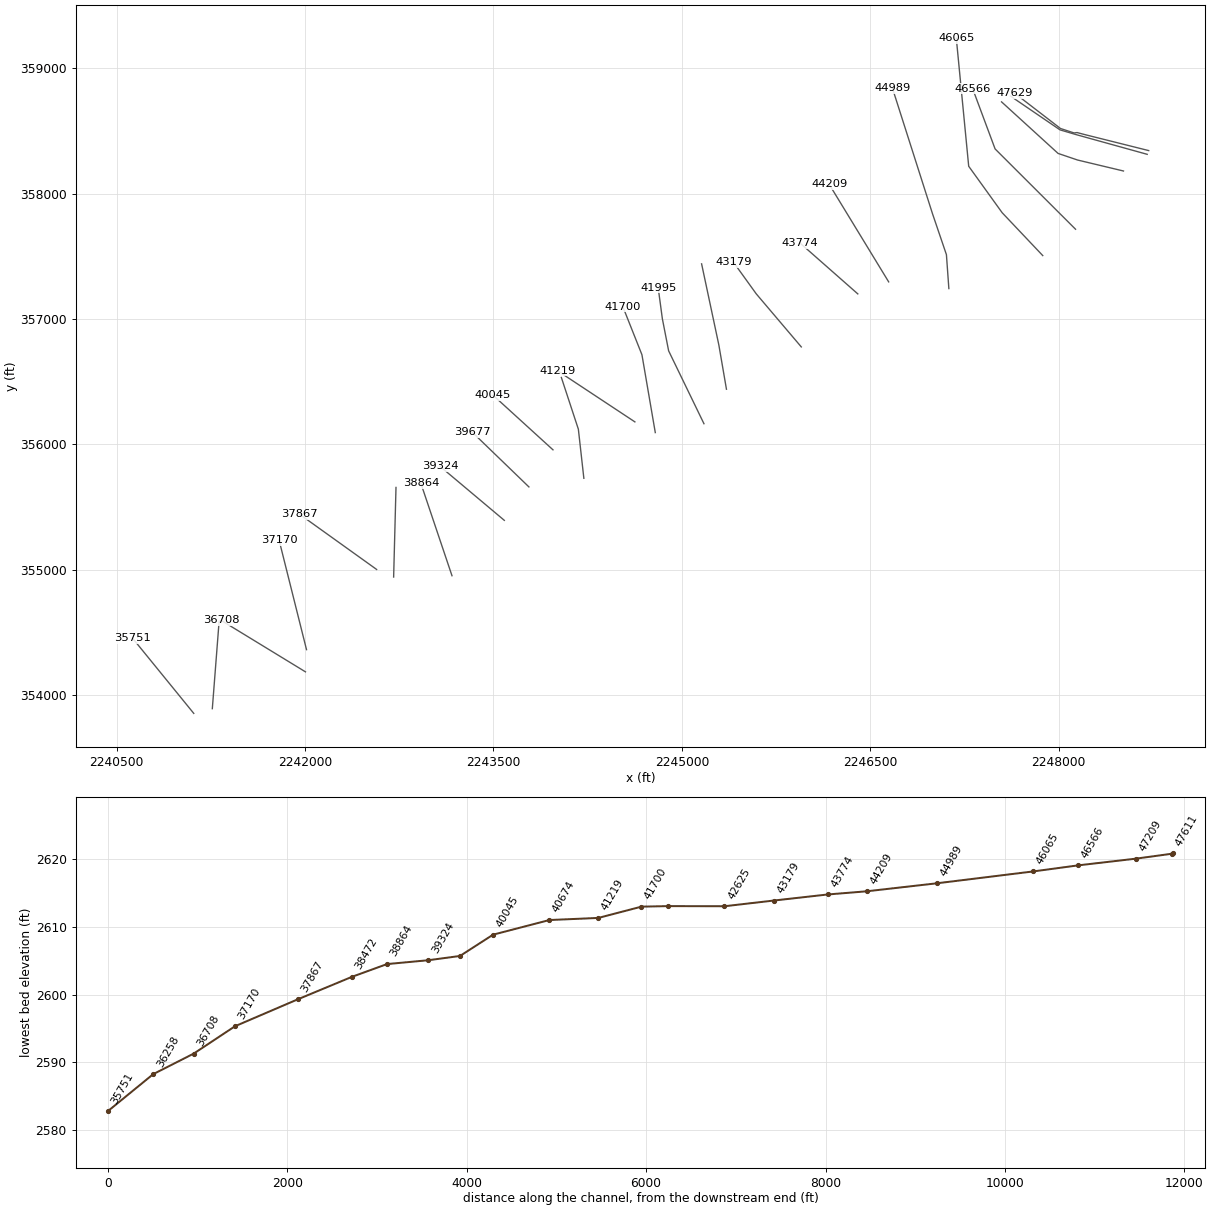
HEC-RAS study MEADOWCK1.prj: MEADOWCK1

--- MEADOWCK1.g01 (geometry) --- (continued)

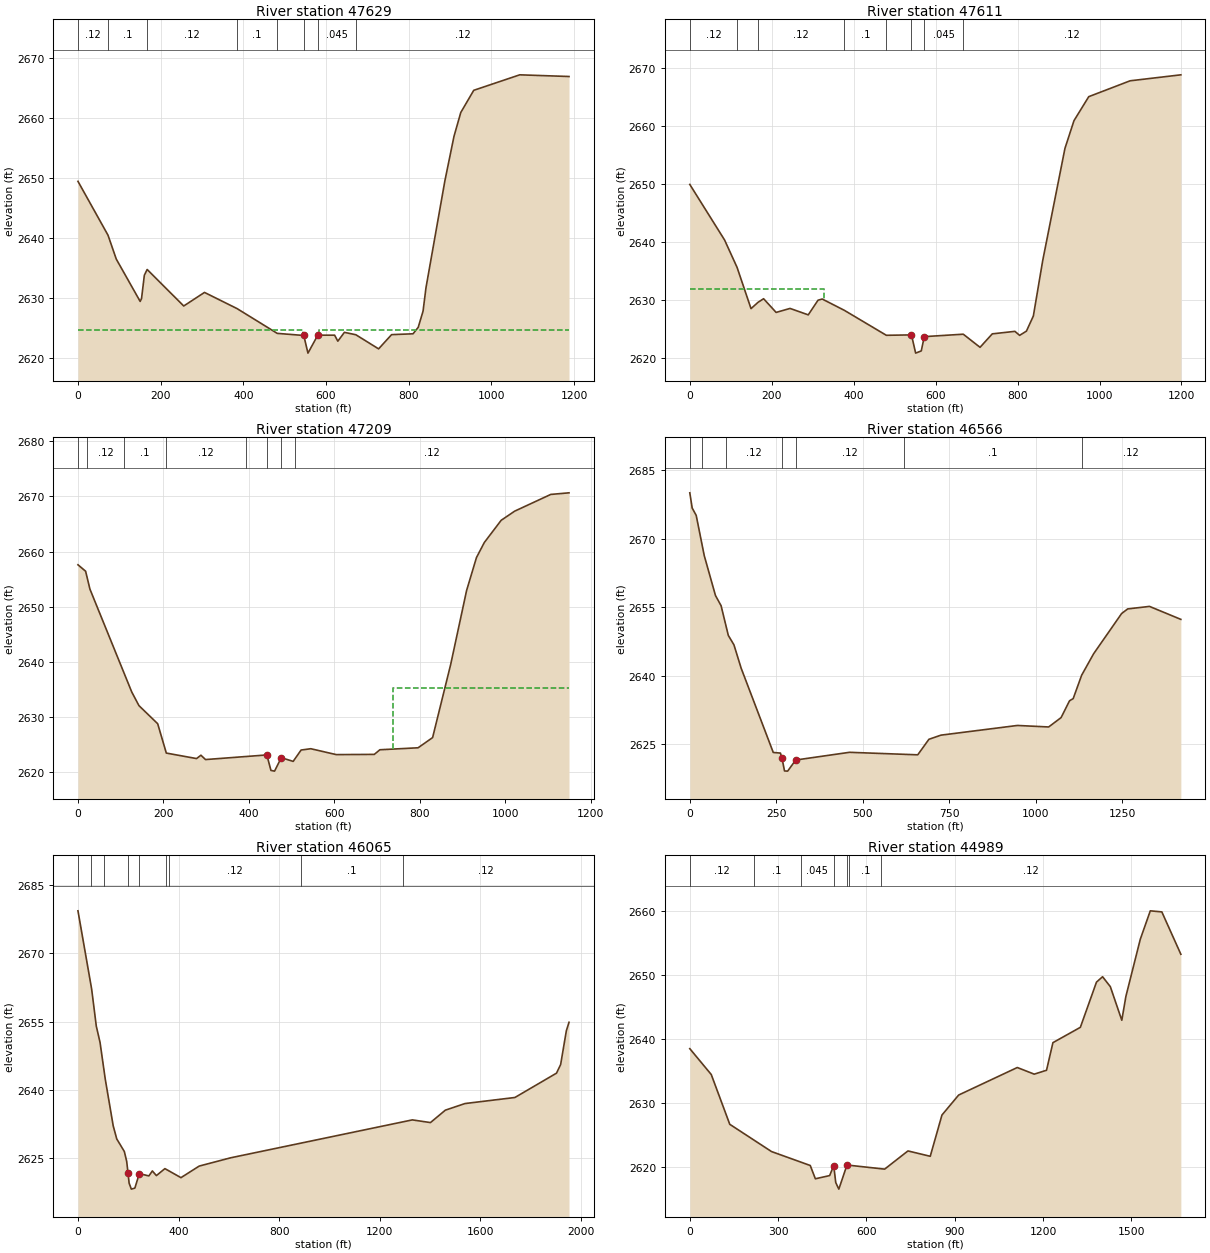
Type RM Length L Ch R = 1 ,47629   ,18.4,18.3,18.1
XS GIS Cut Line= 6
2248717.16586205358343.2115258132248207.44345631358470.989157394
2248147.02691047358486.9615663892248123.03483248358483.762753889
2248014.86018005358519.3781682252247649.11025539358801.544926733
#Sta/Elev= 30
       0  2649.5    72.7 2640.53    92.7 2636.55   150.5  2629.5   153.8 2629.98
   160.6 2633.86   167.4 2634.82   255.9 2628.74   306.1    2631   384.8 2628.31
   482.1 2624.18   546.3 2623.83   556.4 2620.89   580.2 2623.88   620.9 2623.88
   628.7 2622.88   644.6 2624.35   672.3 2623.95   727.3  2621.6   758.8 2623.97
   810.7 2624.11   823.2 2625.19   834.9 2627.89   841.9 2631.76   887.7 2649.59
   909.7 2656.99   926.1 2660.96   957.5 2664.66  1068.8 2667.24    1188 2666.96
#Mann= 8 ,-1 , 0
       0     .12       0    72.7      .1       0   167.4     .12       0
   384.8      .1       0   482.1    .045       0   546.3    .045       0
   580.2    .045       0   672.3     .12       0
#XS Ineff= 2 , 0
           543.3 2624.75   583.2         2624.75
Permanent Ineff=
       F       F
Bank Sta=546.3,580.2
XS Rating Curve= 0 ,0
Exp/Cntr=0.5,0.3

Type RM Length L Ch R = 1 ,47611   ,392.1,401.8,387.5
XS GIS Cut Line= 4
2248705.36011139358313.3503650582248137.99904139358470.989157394
2248011.38807413358508.2669699792247616.94365305358777.711312979
#Sta/Elev= 30
       0 2649.89    84.9 2640.32   115.4  2635.6   149.4  2628.5   166.5 2629.59
   180.1 2630.21   210.7 2627.85   244.6 2628.54   289.1 2627.43   312.9 2629.95
   323.1 2630.16   377.2 2628.21   479.7 2623.91     541 2623.98   551.2 2620.84
   564.9 2621.22   572.3 2623.68   667.4  2624.1   708.4 2621.84   738.2 2624.16
   793.4 2624.59     805  2623.9   821.6 2624.63   838.5 2627.24   861.3 2636.77
   915.6  2656.1   937.6 2660.87   973.7 2665.01  1074.6 2667.74  1198.5 2668.77
#Mann= 8 ,-1 , 0
       0     .12       0   115.4      .1       0   166.5     .12       0
   377.2      .1       0   479.7    .045       0     541    .045       0
   572.3    .045       0   667.4     .12       0
#XS Ineff= 2 , 0
          326.49 2631.92
Permanent Ineff=
       F       F
Bank Sta=541,572.3
XS Rating Curve= 0 ,0
Exp/Cntr=0.5,0.3

Type RM Length L Ch R = 1 ,47209   ,642.3,642.4,622.7
XS GIS Cut Line= 4
2248516.41462314358180.3450536432248151.13681039358267.845206723
2247995.58134723358320.6229883132247545.58126298358731.734042734
#Sta/Elev= 30
       0 2657.59    17.9 2656.42      28 2653.17   125.8  2634.5   142.7 2632.01
   186.6 2628.72   206.8 2623.39   277.6 2622.39   287.8    2623   298.6 2622.21
   442.1 2623.05   451.7 2620.24   460.2 2620.11   475.9 2622.55   503.7 2621.88
   522.3 2623.94     545 2624.18   604.5 2623.11   693.6 2623.15   706.7 2623.99
   796.1 2624.35   830.1  2626.2   872.5 2639.51   909.6  2652.9   932.8 2658.91
   951.1 2661.63   990.6 2665.67  1022.2 2667.33  1106.7 2670.37  1149.4 2670.66
#Mann= 8 ,-1 , 0
       0      .1       0   21.43     .12       0  107.44      .1       0
  207.04     .12       0  392.22      .1       0   442.1    .045       0
   475.9      .1       0   507.3     .12       0
#XS Ineff= 2 , 0
                          737.52         2635.23
Permanent Ineff=
       F       F
Bank Sta=442.1,475.9
XS Rating Curve= 0 ,0
Exp/Cntr=0.3,0.1

Type RM Length L Ch R = 1 ,46566   ,477.2,501.6,473.4
XS GIS Cut Line= 3
2248134.72148889357715.8850245622247494.09678589358356.510055646
2247315.23373507358837.659068983
#Sta/Elev= 30
       0 2680.06     6.8 2676.75    18.5 2675.11    41.7 2666.32    74.2 2657.57
    90.4 2655.34   111.3 2648.84   127.5 2646.78   148.4 2641.66   241.2 2623.21
     262 2623.07   266.7 2621.89   273.7 2619.16   282.8 2619.12     306 2621.55
   461.5 2623.24   658.8 2622.69   691.1 2626.09     726    2627     947 2629.12
  1037.2 2628.79  1073.1 2630.84  1097.6 2634.53  1108.1    2635  1132.6 2640.13
  1167.3 2644.84  1248.1 2653.63  1265.6 2654.64  1328.6 2655.19  1419.3 2652.35
#Mann= 7 ,-1 , 0
       0     .12       0   34.18      .1       0  104.85     .12       0
   266.7    .045       0     306     .12       0  618.93      .1       0
 1132.33     .12       0
Bank Sta=266.7,306
XS Rating Curve= 0 ,0
Exp/Cntr=0.3,0.1

Type RM Length L Ch R = 1 ,46065   ,1042.3,1076.1,1025.8
XS GIS Cut Line= 4
2247873.58060697357505.7565078142247550.49037389357847.597031474
2247283.99746856358218.256723225 2247185.3477361359238.503208455
#Sta/Elev= 30
       0 2679.32    54.3 2662.17    72.9 2653.99    87.7 2650.45   108.5 2642.36
   140.1 2632.11   154.1 2629.25   184.3 2626.48   193.6 2624.34   199.12621.736
   203.3 2619.54   212.1 2618.22   226.1 2618.44     244 2621.63   281.8 2621.12
   295.7 2622.21   311.7 2621.19   345.6 2622.72   409.4 2620.74   481.9 2623.28
   607.1  2625.1  1329.1 2633.42  1401.1 2632.83  1460.4 2635.56  1538.6 2637.01
  1736.9 2638.34  1902.1 2643.68  1918.6 2645.57  1941.3 2652.99  1951.9 2654.85
#Mann= 9 ,-1 , 0
       0      .1       0   50.99     .12       0  105.41      .1       0
   199.1    .045       0     244     .12       0  351.31      .1       0
   363.6     .12       0  886.43      .1       0 1293.31     .12       0
Bank Sta=199.1,244
XS Rating Curve= 0 ,0
Exp/Cntr=0.3,0.1

Type RM Length L Ch R = 1 ,44989   ,745.7,779.8,766.2
XS GIS Cut Line= 4
2247126.01123597357242.562152311 2247106.6247918357513.106230646
2246995.51379356357840.3631220612246676.45464501358841.886975708
#Sta/Elev= 30
       0 2638.45    72.9  2634.4   135.7 2626.61   277.6 2622.34   409.1 2620.16
   426.5 2618.08     475 2618.58   488.8 2620.14   495.8 2617.48   506.2 2616.46
   533.92620.236   661.8 2619.59     741 2622.44   816.7  2621.6   856.5 2628.06
   913.2 2631.19  1112.4  2635.5  1169.9 2634.46  1211.7 2635.07  1233.4 2639.39
  1326.6 2641.79  1381.4 2648.87  1402.1 2649.71  1428.4 2648.16  1467.4  2642.9
  1481.3 2646.64  1530.2 2655.58  1564.2 2660.03  1603.4 2659.86    1668 2653.23
#Mann= 7 ,-1 , 0
       0     .12       0  216.73      .1       0  376.49    .045       0
   488.8    .045       0   533.9    .045       0  541.41      .1       0
   650.9     .12       0
Bank Sta=488.8,533.9
XS Rating Curve= 0 ,0
Exp/Cntr=0.3,0.1

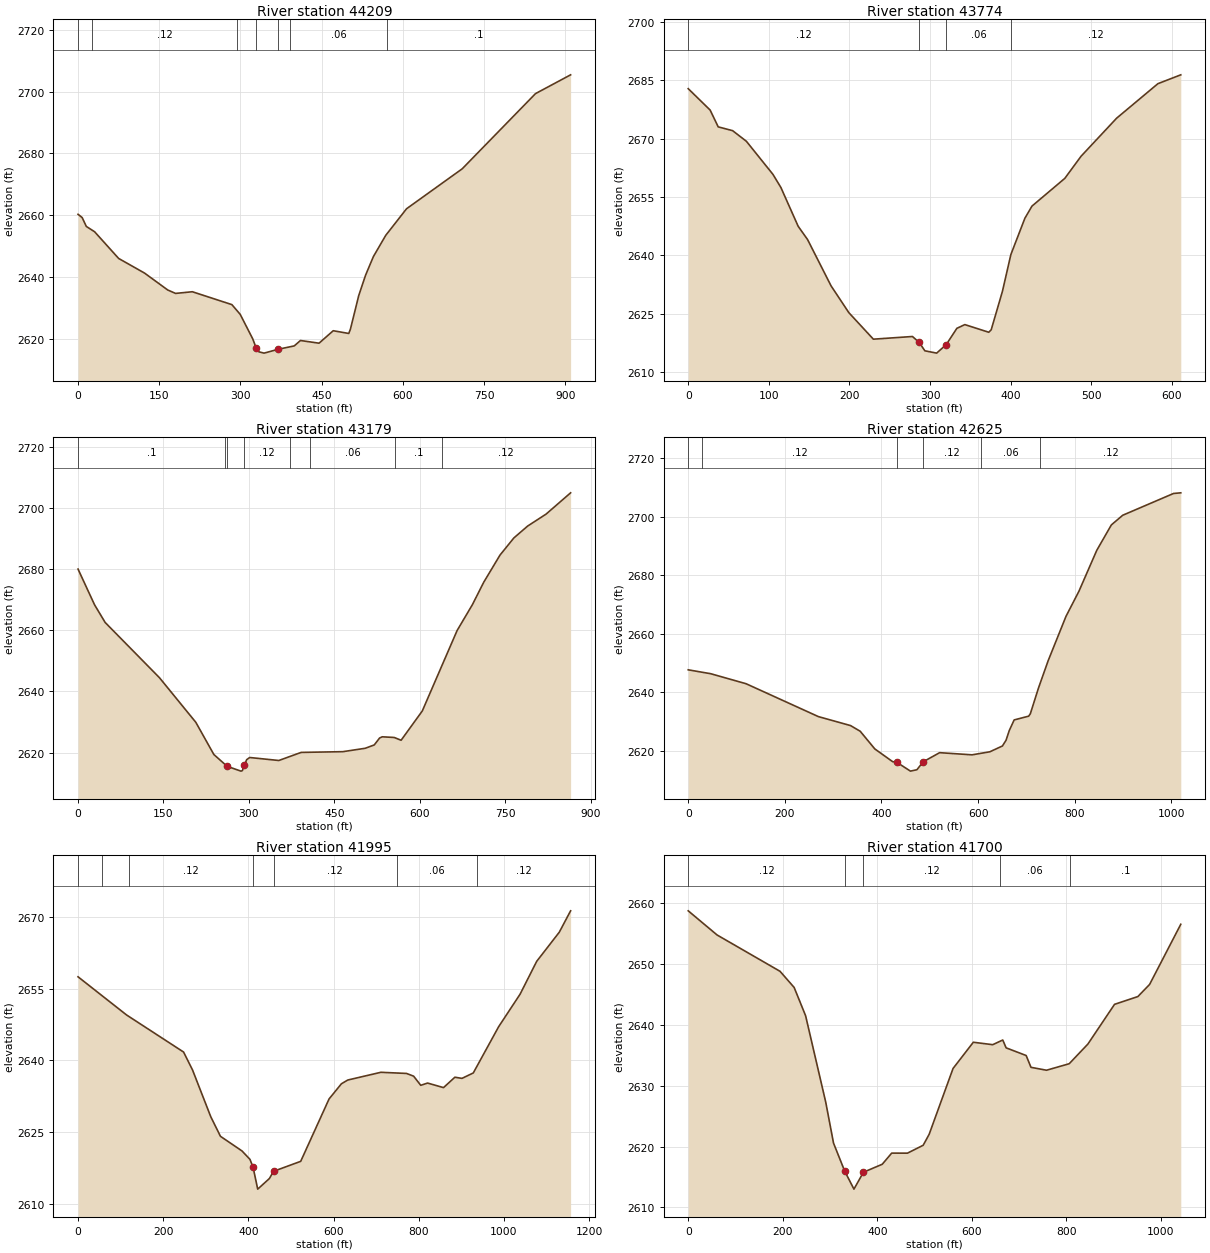
Type RM Length L Ch R = 1 ,44209   ,397,434.7,430
XS GIS Cut Line= 2
2246646.81567205357296.0052868872246173.89896697358073.088706478
#Sta/Elev= 30
       0 2660.27     7.6 2659.21    15.3 2656.33    30.6 2654.61      75 2645.96
   122.8 2641.22   165.7 2635.73   180.1 2634.63   211.1 2635.17   284.1    2631
   299.5 2627.84   322.5 2619.95     329 2616.95     334  2615.7   343.6 2615.28
  369.952616.541   399.3 2617.62   410.8 2619.37   445.1  2618.5   471.3 2622.54
     500 2621.65     503 2623.02   518.4 2633.93     531 2640.52   545.5 2646.58
   568.3 2653.45   606.7 2662.06   709.6 2675.02   844.8 2699.36   909.7 2705.46
#Mann= 7 ,-1 , 0
       0      .1       0   26.56     .12       0   294.1      .1       0
     329    .045       0  369.95      .1       0  390.94     .06       0
   571.1      .1       0
Bank Sta=329,369.95
XS Rating Curve= 0 ,0
Exp/Cntr=0.3,0.1

Type RM Length L Ch R = 1 ,43774   ,596.2,595.6,591.5
XS GIS Cut Line= 2
 2246400.9825023357200.1721452332245942.64910139357604.338659734
#Sta/Elev= 30
       0 2682.87    27.2 2677.36    37.2 2673.04    55.1 2672.06    72.2 2669.32
   105.1 2660.82     115 2657.43   136.4 2647.46   148.1 2644.03   177.2 2632.13
   199.3 2625.22   229.7  2618.4   278.2 2619.09   286.6 2617.56   293.6 2615.41
   308.2 2614.81   320.1    2617   333.3 2621.19   343.2 2622.15   372.9 2620.18
   375.9 2620.82   389.8 2630.69   400.3 2640.18   417.7 2649.53   426.5 2652.65
   467.2 2659.78   487.4 2665.48   531.5 2675.27   582.7 2684.15   611.1 2686.43
#Mann= 4 ,-1 , 0
       0     .12       0   286.6    .045       0   320.1     .06       0
  400.23     .12       0
Bank Sta=286.6,320.1
XS Rating Curve= 0 ,0
Exp/Cntr=0.3,0.1

Type RM Length L Ch R = 1 ,43179   ,554.2,553.6,540.5
XS GIS Cut Line= 3
2245950.98241806356777.2553401442245592.64914522357200.172145233
2245411.39917964357452.255302474
#Sta/Elev= 30
       0 2680.08      29 2668.38    47.6  2662.6     143  2644.5   206.8  2629.9
   238.5 2619.35  261.75  2615.5     286 2613.92   288.5 2614.07     292 2615.84
   296.1 2617.68   301.4 2618.38   352.5  2617.4   391.7 2620.05   464.8 2620.29
   504.2  2621.4   520.1  2622.5   529.4 2624.76   534.1 2625.16   555.1 2624.94
   567.2 2624.03   604.4 2633.62   665.5 2659.95   692.4 2668.44   712.4 2675.82
   740.9 2684.68   765.2 2690.28   789.4 2694.17   821.8 2698.09   864.8 2705.05
#Mann= 8 ,-1 , 0
       0      .1       0  258.36     .12       0  261.75    .045       0
     292     .12       0  371.77      .1       0  407.36     .06       0
  556.19      .1       0  639.08     .12       0
Bank Sta=261.75,292
XS Rating Curve= 0 ,0
Exp/Cntr=0.3,0.1

Type RM Length L Ch R = 1 ,42625   ,607.6,630.1,621.6
XS GIS Cut Line= 3
2245355.14896405356439.7553589792245294.73241822356791.838644311
2245157.23236513357439.755327478
#Sta/Elev= 30
       0 2647.71    46.5 2646.38   119.7 2642.96   269.5 2631.71   336.1 2628.64
     356 2626.71   386.2 2620.67   423.1 2616.31   431.8 2616.09     460 2613.07
   473.4 2613.55   486.3 2616.25   520.4 2619.38   587.5 2618.64   624.3 2619.68
   650.4 2621.67   657.9 2623.63   664.6 2626.96   674.7 2630.58   704.8 2631.87
   708.2  2632.7     725 2641.47   745.1 2650.84     782    2666   808.8 2674.59
   845.7 2688.57   875.9 2697.26   899.4 2700.56  1004.6 2708.01  1019.6 2708.23
#Mann= 6 ,-1 , 0
       0      .1       0   28.75     .12       0   431.8    .045       0
   486.3     .12       0  605.59     .06       0  729.02     .12       0
Bank Sta=431.8,486.3
XS Rating Curve= 0 ,0
Exp/Cntr=0.3,0.1

Type RM Length L Ch R = 1 ,41995   ,299.1,295.3,288.3
XS GIS Cut Line= 4
2245175.98232764356164.7555808872244894.73223397 356746.00540264
2244844.73233397357002.255546317 2244811.3990673357250.172045231
#Sta/Elev= 30
       0 2657.47     114 2649.49   247.9 2641.74   268.9    2638   311.7 2628.23
   334.5 2624.13   385.1 2621.07   403.8 2619.31   411.1 2617.66     422 2613.09
   449.5 2615.31   459.1 2616.81     523  2618.9   589.6 2631.94   618.6 2635.11
   633.4 2635.89   711.3 2637.51   771.5 2637.27   788.2  2636.7   804.9 2634.79
     821 2635.26   858.4 2634.31   885.1 2636.48   901.8 2636.24   928.3 2637.37
   987.9 2647.04  1038.2 2653.83  1077.3 2660.71  1130.3 2666.79  1156.9 2671.26
#Mann= 7 ,-1 , 0
       0     .12       0   56.16      .1       0  119.25     .12       0
   411.1    .045       0   459.1     .12       0  748.24     .06       0
  937.44     .12       0
Bank Sta=411.1,459.1
XS Rating Curve= 0 ,0
Exp/Cntr=0.3,0.1

Type RM Length L Ch R = 1 ,41700   ,456.5,481.1,494.7
XS GIS Cut Line= 3
2244788.48244648356093.9220611452244682.23233089 356714.75546515
2244530.14897364357098.088687971
#Sta/Elev= 30
       0 2658.75    61.1 2654.78   194.3 2648.81   224.2 2646.15   248.4 2641.51
     291  2627.3   307.5 2620.57   330.8 2616.03   330.8 2616.02   350.7 2613.01
   370.7 2615.78   410.6  2617.1   430.6 2618.93   463.9 2618.92   497.2 2620.22
   509.9 2622.03   560.4 2632.84   603.3 2637.15   644.4 2636.75   665.6 2637.52
   672.7 2636.23   715.1 2634.97   725.3 2633.03   758.2 2632.55   806.2 2633.62
   845.7 2636.85   902.1 2643.38   951.5 2644.66   976.3 2646.65  1042.3 2656.54
#Mann= 5 ,-1 , 0
       0     .12       0   330.8    .045       0   370.7     .12       0
  659.63     .06       0  808.46      .1       0
Bank Sta=330.8,370.7
XS Rating Curve= 0 ,0
Exp/Cntr=0.3,0.1

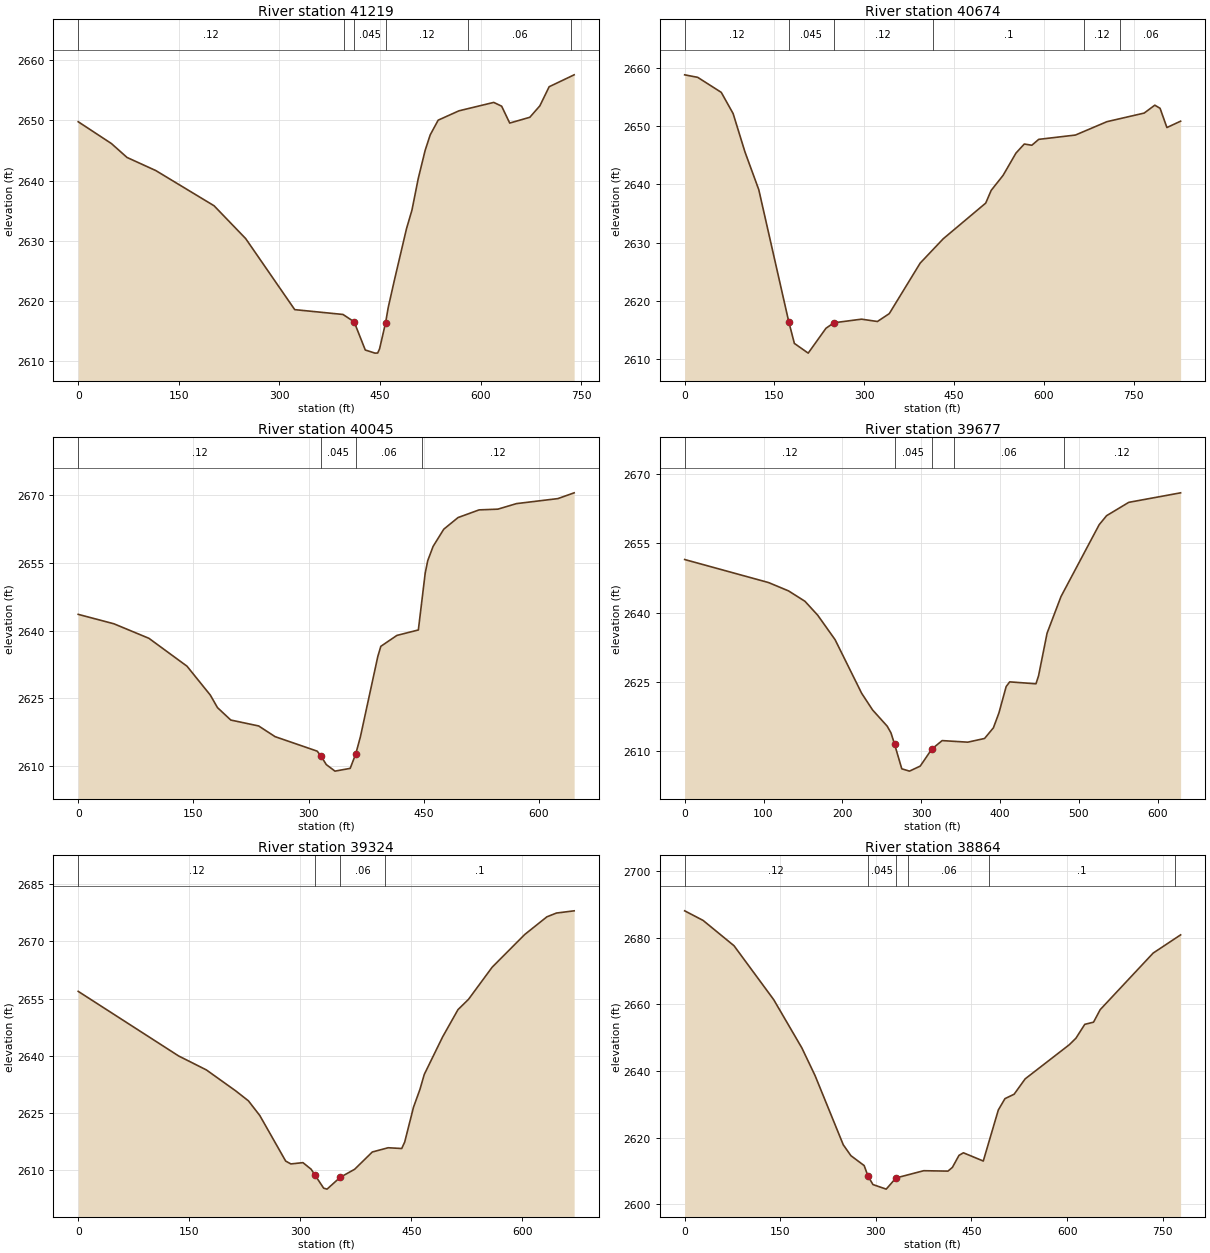
Type RM Length L Ch R = 1 ,41219   ,570.4,544.5,486.3
XS GIS Cut Line= 2
2244625.98244339356179.3388850542244009.31569771356587.672057897
#Sta/Elev= 30
       0 2649.76    49.5 2646.14    72.8 2643.83   115.6 2641.66   202.6 2635.81
   249.8 2630.35   322.9 2618.56   394.9 2617.76   411.5 2616.54   428.1 2611.86
   442.6 2611.34   446.6 2611.36   449.4 2612.04   458.4 2616.39   462.3  2618.9
   471.4 2623.39   489.6 2632.01   497.7 2635.08   507.1 2640.33   517.4 2645.01
   524.9 2647.57   536.8 2650.02   567.7 2651.57   619.7 2652.97   631.5 2652.34
   643.5 2649.54   673.5  2650.5   688.5 2652.41   702.3 2655.57   739.6 2657.55
#Mann= 6 ,-1 , 0
       0     .12       0  396.88      .1       0   411.5    .045       0
   458.4     .12       0  581.43     .06       0  734.57     .12       0
Bank Sta=411.5,458.4
XS Rating Curve= 0 ,0
Exp/Cntr=0.3,0.1

Type RM Length L Ch R = 1 ,40674   ,616.6,628.7,625.6
XS GIS Cut Line= 3
2244219.73227164355729.3388008182244175.98235914356121.005340308
2244040.56563522356533.505499557
#Sta/Elev= 30
       0 2658.81    21.7 2658.38    61.1  2655.8    80.9 2652.16   100.7 2645.57
   123.8 2639.08  173.782616.452   183.2  2612.7   206.3 2611.03     236  2615.3
   249.2 2616.24   295.4 2616.86   321.9 2616.46   341.7 2617.81   393.3 2626.48
   431.7 2630.65   502.8 2636.79   511.9 2638.97   531.8 2641.55   553.3 2645.37
   567.2 2646.93   579.8 2646.72   591.3 2647.73   652.6 2648.47   705.3 2650.77
   767.4 2652.24   785.2  2653.6     794 2653.06   805.4 2649.76   828.3 2650.85
#Mann= 6 ,-1 , 0
       0     .12       0  173.78    .045       0   249.2     .12       0
  414.11      .1       0  666.99     .12       0  727.09     .06       0
Bank Sta=173.78,249.2
XS Rating Curve= 0 ,0
Exp/Cntr=0.3,0.1

Type RM Length L Ch R = 1 ,40045   ,367.4,368.5,364.9
XS GIS Cut Line= 2
2243973.89910188355956.4220080672243496.81573847356391.838788137
#Sta/Elev= 30
       0  2643.6    46.5 2641.51    92.1 2638.29   141.7 2632.11   172.1  2625.7
   181.4 2622.93   198.7 2620.18     235 2618.87   256.4  2616.5   311.2 2613.29
   315.9 2612.27   323.1 2610.31   334.4 2608.86   354.2 2609.47   361.5 2612.69
   367.5 2616.46   390.2 2634.27   394.1 2636.51     415 2638.93     443 2640.14
   451.9 2652.72   455.2 2655.49   462.2 2658.66   476.1 2662.47   494.7 2665.05
   522.1 2666.75   546.5 2666.91   570.8 2668.14   624.7 2669.25   645.9 2670.53
#Mann= 4 ,-1 , 0
       0     .12       0   315.9    .045       0   361.5     .06       0
  448.13     .12       0
Bank Sta=315.9,361.5
XS Rating Curve= 0 ,0
Exp/Cntr=0.3,0.1

Type RM Length L Ch R = 1 ,39677   ,350.5,352.9,352.6
XS GIS Cut Line= 2
2243782.23249047355660.5889383112243330.14907706356098.088719472
#Sta/Elev= 30
       0 2651.46   106.4 2646.48   131.7 2644.68   152.6 2642.43   168.8 2639.41
   190.8 2634.13   224.5 2622.54   238.4 2618.93   256.9 2615.43   261.7 2613.98
   266.2 2611.56   275.4 2606.21   285.2 2605.71   298.8  2606.8   313.5 2610.48
   326.6 2612.31   359.1 2611.97   380.4 2612.77   391.6 2615.07   398.6 2618.28
   407.8 2623.99   412.3 2625.01   445.6 2624.59   448.9 2626.32   459.7 2635.53
   477.4 2643.47   525.8 2658.99   535.2 2660.94   563.3 2663.82   629.1 2665.88
#Mann= 5 ,-1 , 0
       0     .12       0   266.2    .045       0   313.5     .12       0
  341.21     .06       0  481.16     .12       0
Bank Sta=266.2,313.5
XS Rating Curve= 0 ,0
Exp/Cntr=0.3,0.1

Type RM Length L Ch R = 1 ,39324   ,472.6,460.3,448.1
XS GIS Cut Line= 2
2243586.39889264355393.9221488092243073.89893338355825.172270566
#Sta/Elev= 30
       0 2656.89   135.6 2639.97   173.1 2636.31   212.8 2630.81   229.9 2628.21
   245.3 2624.35   280.2 2612.43   287.2 2611.68   303.5 2612.02   314.6 2610.29
     320 2608.69   331.5 2605.33   336.1 2605.08  353.632608.141   373.4 2610.29
   397.2 2614.81   418.6 2615.92   436.9 2615.72   440.9 2617.39   452.9 2626.58
   461.5 2631.19   467.4 2635.14   492.1 2644.94   512.9  2652.1   527.1  2654.8
   559.1 2663.23     603 2671.78     633 2676.42   645.9 2677.41   669.8 2677.99
#Mann= 4 ,-1 , 0
       0     .12       0     320    .045       0  353.63     .06       0
  413.89      .1       0
Bank Sta=320,353.63
XS Rating Curve= 0 ,0
Exp/Cntr=0.3,0.1

Type RM Length L Ch R = 1 ,38864   ,400.3,391.3,380.6
XS GIS Cut Line= 2
2243169.73240314354952.2553812272242921.81557614355689.755546644
#Sta/Elev= 30
       0 2688.08    28.9  2685.2    77.4  2677.6   139.7  2661.4   183.9  2646.9
   204.6 2638.59   248.8 2617.83   260.8 2614.56   281.6 2611.58   287.5 2608.47
   295.4 2605.88   316.2 2604.51   331.5 2607.86     375 2610.04   413.1 2609.92
     420 2611.03   430.4 2614.65   437.3 2615.42   468.5 2612.95   492.1 2628.28
   502.5 2631.68   516.9 2633.01   534.2 2637.62   603.5 2647.88   613.9 2649.84
   627.7 2653.99   641.5 2654.65   651.9  2658.4     735 2675.39   778.1 2680.86
#Mann= 6 ,-1 , 0
       0     .12       0   287.5    .045       0   331.5     .12       0
  350.97     .06       0  477.26      .1       0  769.73     .12       0
Bank Sta=287.5,331.5
XS Rating Curve= 0 ,0
Exp/Cntr=0.3,0.1

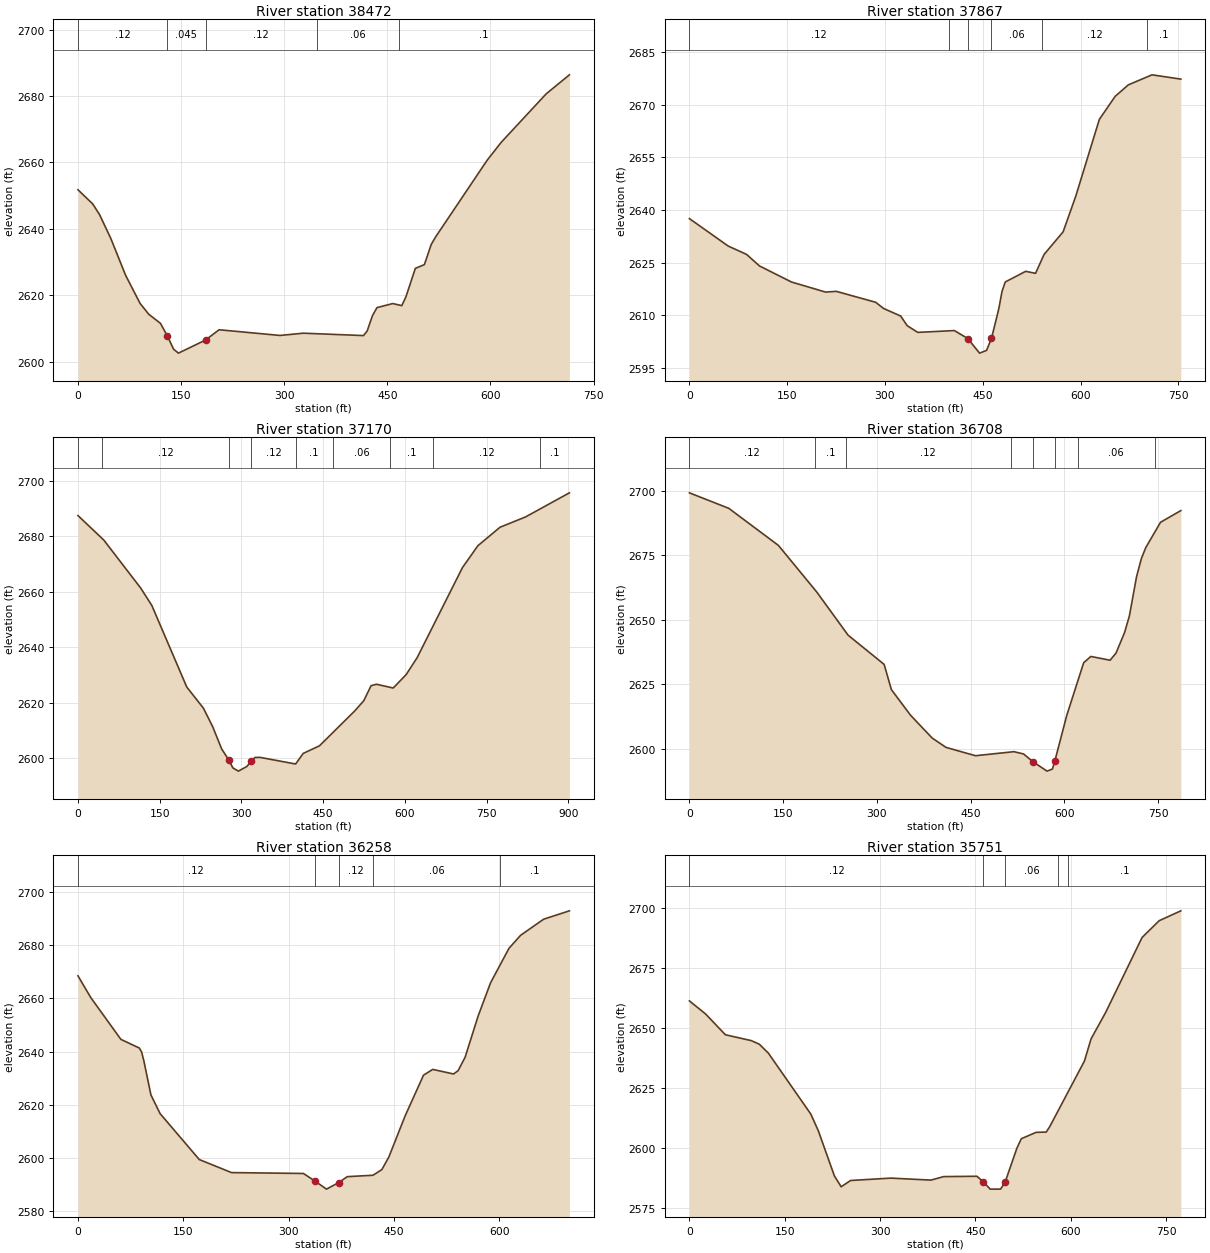
Type RM Length L Ch R = 1 ,38472   ,589.8,605.8,617
XS GIS Cut Line= 2
2242705.14901473354941.8387353872242723.89897722355656.422279984
#Sta/Elev= 30
       0 2651.77    21.4 2647.53    31.3 2644.34    47.7 2637.16    69.2 2626.08
    90.3 2617.59   102.9 2614.33   119.9  2611.6   129.9 2607.83   139.1  2603.8
   146.1 2602.62   185.5 2606.55   205.2 2609.65   293.8 2607.94   327.8 2608.62
   415.3  2607.9   420.6 2609.27   428.4 2613.92   434.9 2616.31   457.9 2617.54
     471 2616.91   477.1 2619.62   490.7 2628.13   503.9 2629.26   513.7 2635.28
   520.3 2637.62     595 2660.62   615.6 2666.06   681.1 2680.66   714.8 2686.37
#Mann= 5 ,-1 , 0
       0     .12       0   129.9    .045       0   185.5     .12       0
  347.55     .06       0  466.84      .1       0
Bank Sta=129.9,185.5
XS Rating Curve= 0 ,0
Exp/Cntr=0.3,0.1

Type RM Length L Ch R = 1 ,37867   ,710.8,696.9,681.2
XS GIS Cut Line= 2
 2242569.7322908355002.2556093042241957.23253155355441.838719651
#Sta/Elev= 30
       0 2637.55    59.5 2629.74    87.8 2627.35   107.5 2624.08   156.5 2619.52
   208.8 2616.65   225.4 2616.85   285.7 2613.75   297.8 2611.99   324.1 2609.83
   334.1 2607.09   350.3 2605.18   406.4  2605.7     427 2603.44   445.1 2599.28
   455.8 2600.05   463.4 2603.46   474.6 2611.87   479.5 2616.79   484.5 2619.52
   515.9 2622.55     531 2621.98   544.1 2627.35   573.3 2633.79   592.6 2643.87
   628.9 2665.78   653.2 2672.34   673.4  2675.6   709.7 2678.45   753.9 2677.23
#Mann= 6 ,-1 , 0
       0     .12       0  398.53     .06       0     427    .045       0
   463.4     .06       0  541.24     .12       0  702.12      .1       0
Bank Sta=427,463.4
XS Rating Curve= 0 ,0
Exp/Cntr=0.3,0.1

Type RM Length L Ch R = 1 ,37170   ,445.1,461.9,473.2
XS GIS Cut Line= 2
2242011.39908989354362.6722428052241792.64919931355237.672133222
#Sta/Elev= 30
       0 2687.43    47.5 2678.58   115.2 2661.27   135.5 2655.04   199.7 2625.61
   230.2    2618   247.1 2611.38   263.7 2603.32   277.3 2599.15   284.3 2596.46
   294.4 2595.31   310.1 2597.01   318.1 2598.93   324.8 2600.24   334.4 2600.26
   399.4 2597.88   413.4  2601.7   443.2 2604.44   507.6 2616.94   524.4 2620.65
   537.9 2626.11   547.8 2626.63   578.5 2625.27   602.2 2630.08   622.4 2636.19
   705.6 2668.67     734 2676.58   774.6 2683.23   821.4 2686.94   901.9 2695.63
#Mann= 9 ,-1 , 0
       0      .1       0   43.73     .12       0   277.3    .045       0
   318.1     .12       0  399.36      .1       0  467.12     .06       0
  572.96      .1       0  650.97     .12       0  848.66      .1       0
Bank Sta=277.3,318.1
XS Rating Curve= 0 ,0
Exp/Cntr=0.3,0.1

Type RM Length L Ch R = 1 ,36708   ,468.7,449.9,432.3
XS GIS Cut Line= 2
2242003.06577322354185.5889355542241332.23246922354596.005437568
#Sta/Elev= 30
       0  2699.1    63.1 2693.08   142.4 2678.73   203.9 2660.62   253.9 2643.94
   311.6 2632.61   323.2 2622.84   353.9  2612.9   388.6 2604.04   410.6 2600.45
   457.8 2597.22   519.3 2598.79   534.7 2597.91   550.1 2594.83   572.3 2591.25
   580.9 2592.06   584.8 2595.12   584.8  2595.2   603.8 2612.82   630.9 2633.26
   642.4 2635.69   673.2 2634.23   682.6 2636.97   696.2 2644.86   704.1 2651.42
   715.5 2666.58   723.2 2673.58   730.3 2677.89   753.9 2687.69   786.4 2692.22
#Mann= 8 ,-1 , 0
       0     .12       0  200.23      .1       0   250.5     .12       0
  514.01      .1       0   550.1    .045       0   584.8     .12       0
  621.32     .06       0  744.34      .1       0
Bank Sta=550.1,584.8
XS Rating Curve= 0 ,0
Exp/Cntr=0.3,0.1

Type RM Length L Ch R = 1 ,36258   ,492.8,506.7,518.8
XS GIS Cut Line= 2
2241261.39894947353891.8388668892241315.56583589354589.755450055
#Sta/Elev= 30
       0 2668.47    18.3 2660.27    61.1 2644.57    87.4 2641.31    90.7 2639.77
      94 2636.29   103.9 2623.67     117 2616.62   172.8 2599.35   218.7 2594.44
   321.1 2594.11   337.2 2591.33     354 2588.22   371.3 2590.66   383.6 2592.91
   420.2 2593.44   432.9 2595.58   442.8 2600.29     466 2615.77   492.2  2631.1
   505.3 2633.27     535 2631.55   541.5  2632.8   551.5 2637.89   569.8  2653.2
   587.6 2665.81   613.9 2678.82   630.4 2683.71   663.3 2689.79     700 2692.94
#Mann= 5 ,-1 , 0
       0     .12       0   337.2    .045       0   371.3     .12       0
  420.02     .06       0  601.78      .1       0
Bank Sta=337.2,371.3
XS Rating Curve= 0 ,0
Exp/Cntr=0.3,0.1

Type RM Length L Ch R = 1 ,35751   ,412.7,414.2,413.2
XS GIS Cut Line= 2
2241113.48225056353854.338941887 2240625.9822413354454.338726148
#Sta/Elev= 30
       0 2661.35    25.4  2655.9    56.6  2647.2    97.2 2644.77   109.9 2643.27
   124.2 2639.53     191 2614.07   202.9 2607.03   228.1 2588.23   238.7 2583.72
   253.6 2586.34   316.9 2587.33   379.9  2586.5     400 2587.96   452.3  2588.1
   462.4 2585.77   473.2 2582.73   489.5 2582.74   496.5 2585.53   515.1 2599.77
   522.1 2603.77   545.3 2606.44   561.3 2606.56   566.5 2608.66   621.4 2636.21
   631.8 2645.44   655.1 2656.67   712.1 2687.83     739 2694.84   773.1 2698.97
#Mann= 5 ,-1 , 0
       0     .12       0   462.4    .045       0   496.5     .06       0
  579.37     .12       0  596.34      .1       0
Bank Sta=462.4,496.5
XS Rating Curve= 0 ,0
Exp/Cntr=0.3,0.1