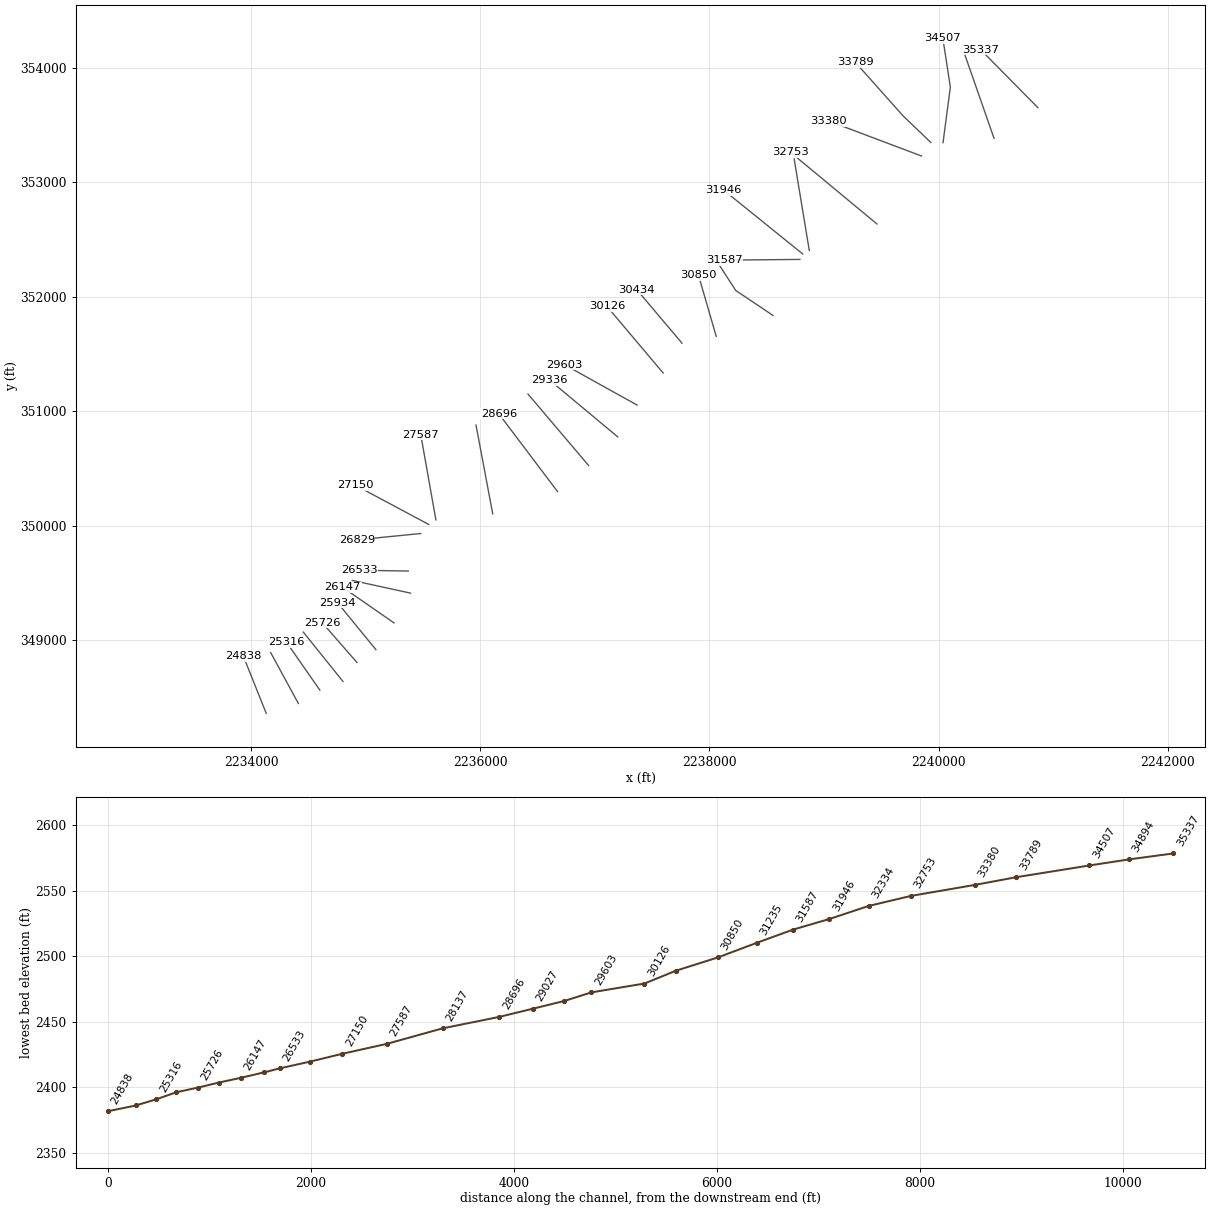
HEC-RAS study MEADOWCK1.prj: MEADOWCK1

--- MEADOWCK1.g01 (geometry) --- (continued)

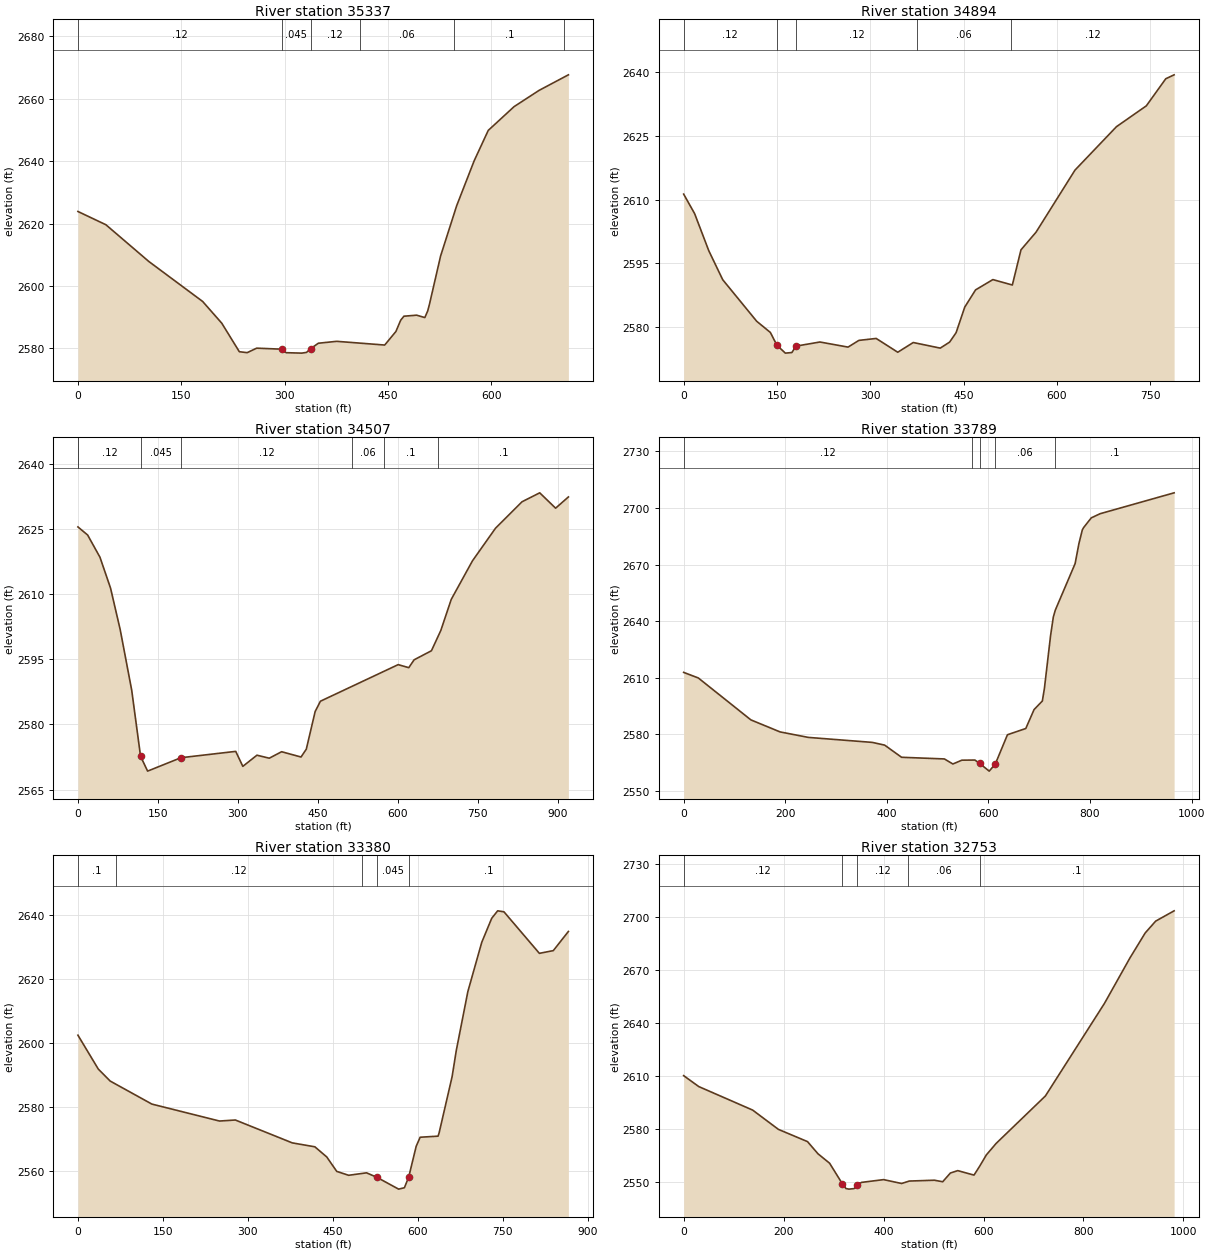
Type RM Length L Ch R = 1 ,35337   ,444.5,442.6,434.1
XS GIS Cut Line= 2
 2240866.7809723353649.7379731392240366.78098805354157.029609472
#Sta/Elev= 30
       0 2623.86    40.6 2619.61     103 2607.83   181.1 2595.03   208.9 2588.06
   234.4 2578.92   245.8 2578.62   259.6 2580.06   296.5 2579.73   302.3 2578.61
   324.9 2578.47   331.9  2578.7   337.9 2579.87   349.1 2581.64   375.9 2582.25
   445.5 2581.06   461.8  2585.4   468.7    2589   473.4  2590.3   491.9 2590.63
   503.8 2589.86     508 2592.01   510.5 2594.11   526.7  2609.6     550 2625.68
   575.4 2640.08   595.9 2649.84   633.4 2657.45   669.6 2662.65   712.3 2667.65
#Mann= 6 ,-1 , 0
       0     .12       0   296.5    .045       0   337.9     .12       0
  408.97     .06       0  546.72      .1       0  706.53     .12       0
Bank Sta=296.5,337.9
XS Rating Curve= 0 ,0
Exp/Cntr=0.3,0.1

Type RM Length L Ch R = 1 ,34894   ,393.3,387.2,367.7
XS GIS Cut Line= 2
2240484.14197381353381.6824068872240224.41972423354126.127112225
#Sta/Elev= 30
       0 2611.32    17.6 2606.73    40.4 2597.98    62.8 2591.15   117.4 2581.36
   139.4 2578.72   149.9 2575.71   163.5 2573.85     174 2573.99   180.6  2575.5
   219.1 2576.47   264.3 2575.27   281.7 2576.85   309.5 2577.31   344.2 2574.06
   369.1 2576.35   412.5 2575.03   427.6 2576.45     438 2578.67   451.9  2584.7
   469.3 2588.75   497.1 2591.18   528.4  2589.9   542.3 2598.19   566.6 2602.37
   629.1 2616.97   695.8 2627.21   743.8 2632.12   775.1 2638.51   788.5 2639.43
#Mann= 5 ,-1 , 0
       0     .12       0   149.9    .045       0   180.6     .12       0
  375.12     .06       0  526.31     .12       0
Bank Sta=149.9,180.6
XS Rating Curve= 0 ,0
Exp/Cntr=0.3,0.1

Type RM Length L Ch R = 1 ,34507   ,699.9,718.6,698.7
XS GIS Cut Line= 3
2240039.00310031  353344.18248192240102.89208014353828.904609561
2240037.61432356354255.293520555
#Sta/Elev= 30
       0 2625.52    18.2 2623.66    41.3 2618.55    61.2 2611.42    79.3 2601.86
   100.9  2587.9   117.5 2572.68   130.7 2569.25   193.3 2572.34   296.1  2573.8
   309.4 2570.35   335.9 2572.92     359 2572.23   382.2 2573.72   418.6  2572.5
   428.5 2574.31   445.1 2582.98     455 2585.36   600.9 2593.79   620.8 2593.09
   630.8  2594.9   663.3 2596.99   680.8 2601.63   700.5 2608.83   740.3 2617.71
   783.5 2625.22   833.3 2631.32   866.5 2633.38   896.3 2629.84   920.3 2632.43
#Mann= 7 ,-1 , 0
       0      .1       0     .86     .12       0   117.5    .045       0
   193.3     .12       0  514.38     .06       0  573.97      .1       0
  676.25      .1       0
Bank Sta=117.5,193.3
XS Rating Curve= 0 ,0
Exp/Cntr=0.3,0.1

Type RM Length L Ch R = 1 ,33789   ,398.1,408.3,415.4
XS GIS Cut Line= 3
2239932.75331281353345.5712586492239689.69769655353578.904781476
2239271.64210223354048.349052563
#Sta/Elev= 30
       0 2612.73    28.8 2609.78   132.4 2587.51   189.8 2581.14   245.5 2578.22
   371.5 2575.57   395.7 2574.12     429 2567.67   513.2 2566.79     530 2564.11
   547.6 2566.13   573.3  2566.2   582.7  2564.4   601.5 2560.32   613.5  2564.1
   637.4 2579.63   673.5 2582.95   689.8 2592.99   706.1 2597.55   710.1  2604.1
   722.3 2632.27   727.7 2642.12   731.6 2645.78   770.6 2670.47   778.1 2681.12
   784.8 2688.37   787.4 2689.62   802.4 2694.76   819.9 2696.97   965.5 2708.05
#Mann= 5 ,-1 , 0
       0     .12       0  567.21     .06       0   582.7    .045       0
   613.5     .06       0  730.08      .1       0
Bank Sta=582.7,613.5
XS Rating Curve= 0 ,0
Exp/Cntr=0.3,0.1

Type RM Length L Ch R = 1 ,33380   ,624,627.6,621.5
XS GIS Cut Line= 2
2239851.50314721353227.5157204722239041.78101338353533.071539804
#Sta/Elev= 30
       0 2602.41    35.9 2591.86    56.9 2588.12   130.5 2580.94   249.8 2575.66
   277.8 2575.98   378.3 2568.85   418.1 2567.63   439.1 2564.46   456.7 2559.97
   477.7 2558.75   509.3 2559.52   527.7 2558.11   565.9 2554.44   576.1 2554.87
   583.7  2558.2   596.9 2567.79   603.9 2570.61   635.5 2570.95   637.4 2571.99
   660.3  2589.5   667.7 2597.68   688.1 2616.02   712.6 2631.35   730.2 2638.85
   740.7 2641.17   751.8 2640.86   814.3 2627.92   838.9 2628.77   865.5 2634.74
#Mann= 5 ,-1 , 0
       0      .1       0   67.09     .12       0  501.91      .1       0
   527.7    .045       0   583.7      .1       0
Bank Sta=527.7,583.7
XS Rating Curve= 0 ,0
Exp/Cntr=0.3,0.1

Type RM Length L Ch R = 1 ,32753   ,430.5,418.2,407.7
XS GIS Cut Line= 2
2239461.93830955352634.254439816 2238706.7301743353260.990391061
#Sta/Elev= 30
       0 2610.18    30.2 2604.01   138.1 2590.72   189.6 2579.83   247.8 2572.92
   268.8 2566.04     292 2560.72   317.6 2549.08   324.7 2546.43   330.4 2546.08
     341 2546.37   347.4 2548.26   355.9 2549.89   400.1 2551.45   436.1 2549.26
   451.5 2550.64   501.8 2551.11   518.3 2550.24   533.7 2555.17   548.4 2556.53
     581 2554.01   592.6 2559.15   605.6 2565.38   625.3 2571.91   723.8 2598.69
     842 2650.99   893.1 2676.71   923.5 2690.77   944.5 2697.47   981.4 2703.28
#Mann= 5 ,-1 , 0
       0     .12       0   317.6    .045       0   347.4     .12       0
  449.43     .06       0   592.6      .1       0
Bank Sta=317.6,347.4
XS Rating Curve= 0 ,0
Exp/Cntr=0.3,0.1

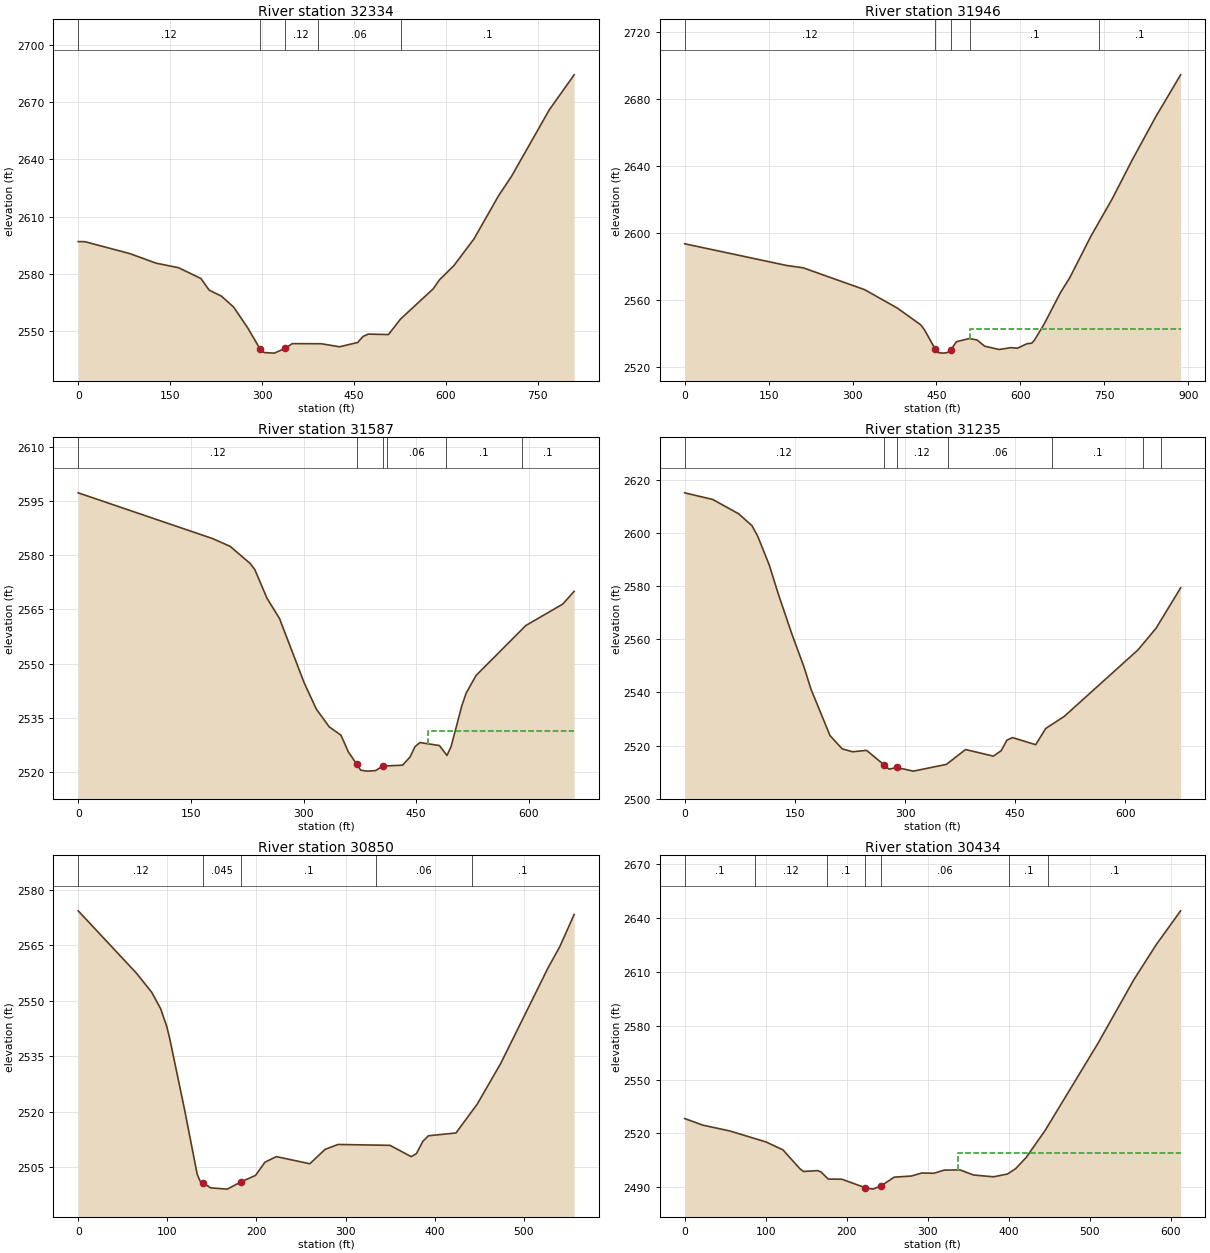
Type RM Length L Ch R = 1 ,32334   ,375.2,388.4,394.9
XS GIS Cut Line= 2
2238871.66061872352403.351358309 2238739.7163288353201.962621972
#Sta/Elev= 30
       0 2596.85    10.8 2596.82      84 2590.58   127.2 2585.54   163.8 2583.16
   200.4 2577.48   213.7  2571.4   233.8 2568.25   253.6 2562.54   276.9 2551.51
   296.3 2540.81   303.5 2538.69   320.1 2538.39   337.4 2540.82   349.3 2543.37
   396.6 2543.31   426.5 2541.72   456.1 2543.97   464.8 2547.12   473.2 2548.36
   506.3 2548.13   526.3 2556.34   579.5 2572.13   589.4 2576.75   613.1 2584.26
     646 2598.31   685.9 2620.82   707.3 2631.14     769 2666.01   809.4 2684.27
#Mann= 5 ,-1 , 0
       0     .12       0   296.3    .045       0   337.4     .12       0
  390.71     .06       0  526.46      .1       0
Bank Sta=296.3,337.4
XS Rating Curve= 0 ,0
Exp/Cntr=0.3,0.1

Type RM Length L Ch R = 1 ,31946   ,346.9,358.8,367.1
XS GIS Cut Line= 2
2238814.36906664352372.1014208052238125.13291231 352929.39328523
#Sta/Elev= 30
       0 2593.56   181.7 2580.66     212 2579.22   321.7  2566.2   380.2 2555.22
     422 2545.24     429 2542.11   447.6 2530.89   452.8 2528.76   460.3 2528.41
   468.6 2528.63   475.6  2530.3   485.7 2535.21   508.3 2537.07   522.3 2536.29
   536.3 2532.53     562 2530.57   583.3 2531.69   594.6 2531.34   612.2 2534.05
   620.3 2534.32   624.9 2536.06   641.8  2545.3   671.6 2564.43   688.2 2573.29
   726.1  2598.1   764.1 2620.28   799.9  2643.5   841.9 2669.18   886.4  2694.2
#Mann= 5 ,-1 , 0
       0     .12       0   447.6    .045       0   475.6     .06       0
  510.28      .1       0  739.82      .1       0
#XS Ineff= 2 , 0
                          510.47         2543.07
Permanent Ineff=
       F       F
Bank Sta=447.6,475.6
XS Rating Curve= 0 ,0
Exp/Cntr=0.3,0.1

Type RM Length L Ch R = 1 ,31587   ,357.6,352.1,341.5
XS GIS Cut Line= 2
2238789.88978489352324.5319621412238129.47312672352318.281974643
#Sta/Elev= 30
       0 2597.21   179.3 2584.54   202.3 2582.42   228.7 2577.74   235.1 2576.03
   251.4 2568.07   268.1 2562.45   300.7  2544.8   317.1 2537.43   334.3 2532.52
   349.9 2530.22   359.7 2525.63   370.7 2522.27   376.2 2520.56     384 2520.29
   395.8 2520.43   405.7 2521.68   431.9 2521.94   441.8 2524.18   448.3    2527
   454.9 2528.19   481.1 2527.36     491 2524.61   496.6 2527.13   510.7 2538.26
   516.5 2541.81   529.7 2546.71     596 2560.53   645.2 2566.46   660.4 2569.98
#Mann= 6 ,-1 , 0
       0     .12       0   370.7    .045       0   405.7     .12       0
  411.75     .06       0  489.61      .1       0   590.4      .1       0
#XS Ineff= 2 , 0
                          465.48         2531.36
Permanent Ineff=
       F       F
Bank Sta=370.7,405.7
XS Rating Curve= 0 ,0
Exp/Cntr=0.3,0.1

Type RM Length L Ch R = 1 ,31235   ,392,385.2,373.7
XS GIS Cut Line= 3
2238555.51492555351834.948623732 2238229.4732548352053.698842391
2238076.34823297352291.198695481
#Sta/Elev= 30
       0 2615.21    38.3  2612.7    73.7 2607.27    91.7 2602.81    99.6 2598.78
   115.2 2587.97   127.2 2577.33   145.9 2562.05   162.5 2549.57   171.9 2541.27
   197.9 2523.74   214.5 2518.74   228.7 2517.65   247.6 2518.19   271.2 2512.79
   278.3 2511.09  288.462511.728   311.4 2510.36   356.4 2512.91   382.4 2518.49
   420.3 2516.01     431 2518.07   438.8 2522.07   446.4 2522.99   477.9 2520.32
   491.5 2526.42   516.9 2531.01   617.3 2556.07   641.8 2564.21   675.2  2579.4
#Mann= 7 ,-1 , 0
       0     .12       0   271.2    .045       0  288.46     .12       0
  358.38     .06       0  500.23      .1       0  624.15      .1       0
   648.6      .1       0
Bank Sta=271.2,288.46
XS Rating Curve= 0 ,0
Exp/Cntr=0.3,0.1

Type RM Length L Ch R = 1 ,30850   ,413.2,416.3,415.4
XS GIS Cut Line= 2
2238059.68159963351652.6569935532237904.47324863352187.031909063
#Sta/Elev= 30
       0 2574.28    65.2 2557.49    82.5 2552.29    92.5 2547.85    99.3 2543.13
   102.7 2539.78   119.5 2520.43   133.5 2503.18   136.9 2501.25   140.3 2500.82
   148.6 2499.49   167.2 2499.15   183.1 2501.15     199 2502.86   209.5 2506.41
   222.3 2507.93   259.9    2506     277 2509.88   291.6 2511.21   349.9 2510.97
   373.7 2507.91   379.5 2508.74   386.9 2512.12   393.1 2513.56   423.9 2514.31
   447.8 2522.12   474.3 2533.17   527.2 2558.88   540.5 2564.66   556.5 2573.29
#Mann= 5 ,-1 , 0
       0     .12       0   140.3    .045       0   183.1      .1       0
  334.23     .06       0  441.87      .1       0
Bank Sta=140.3,183.1
XS Rating Curve= 0 ,0
Exp/Cntr=0.3,0.1

Type RM Length L Ch R = 1 ,30434   ,307.7,308.1,307.9
XS GIS Cut Line= 2
2237760.72320805351593.2821123152237365.93134671352060.990494475
#Sta/Elev= 30
       0 2528.27    22.2 2524.62    55.7 2521.35   100.4 2515.24   121.4 2510.79
   142.2 2500.31   146.7 2498.78   163.9 2499.27   168.2 2498.54   177.2 2494.54
   193.9 2494.48  222.352489.827   232.6 2488.95   242.8 2490.91   258.7 2495.63
   279.7 2496.24   292.7 2497.94   307.6 2497.79   320.2 2499.54   339.9 2499.65
   356.5 2496.81   381.2 2495.82   398.4 2497.36   408.6 2500.41   421.5 2506.59
     445 2521.73   510.2 2570.24   554.4 2605.64   582.3 2625.33   612.1 2643.98
#Mann= 7 ,-1 , 0
       0      .1       0   86.76     .12       0  175.21      .1       0
  222.35    .045       0   242.8     .06       0  399.93      .1       0
  448.88      .1       0
#XS Ineff= 2 , 0
                          337.52         2508.94
Permanent Ineff=
       F       F
Bank Sta=222.35,242.8
XS Rating Curve= 0 ,0
Exp/Cntr=0.3,0.1

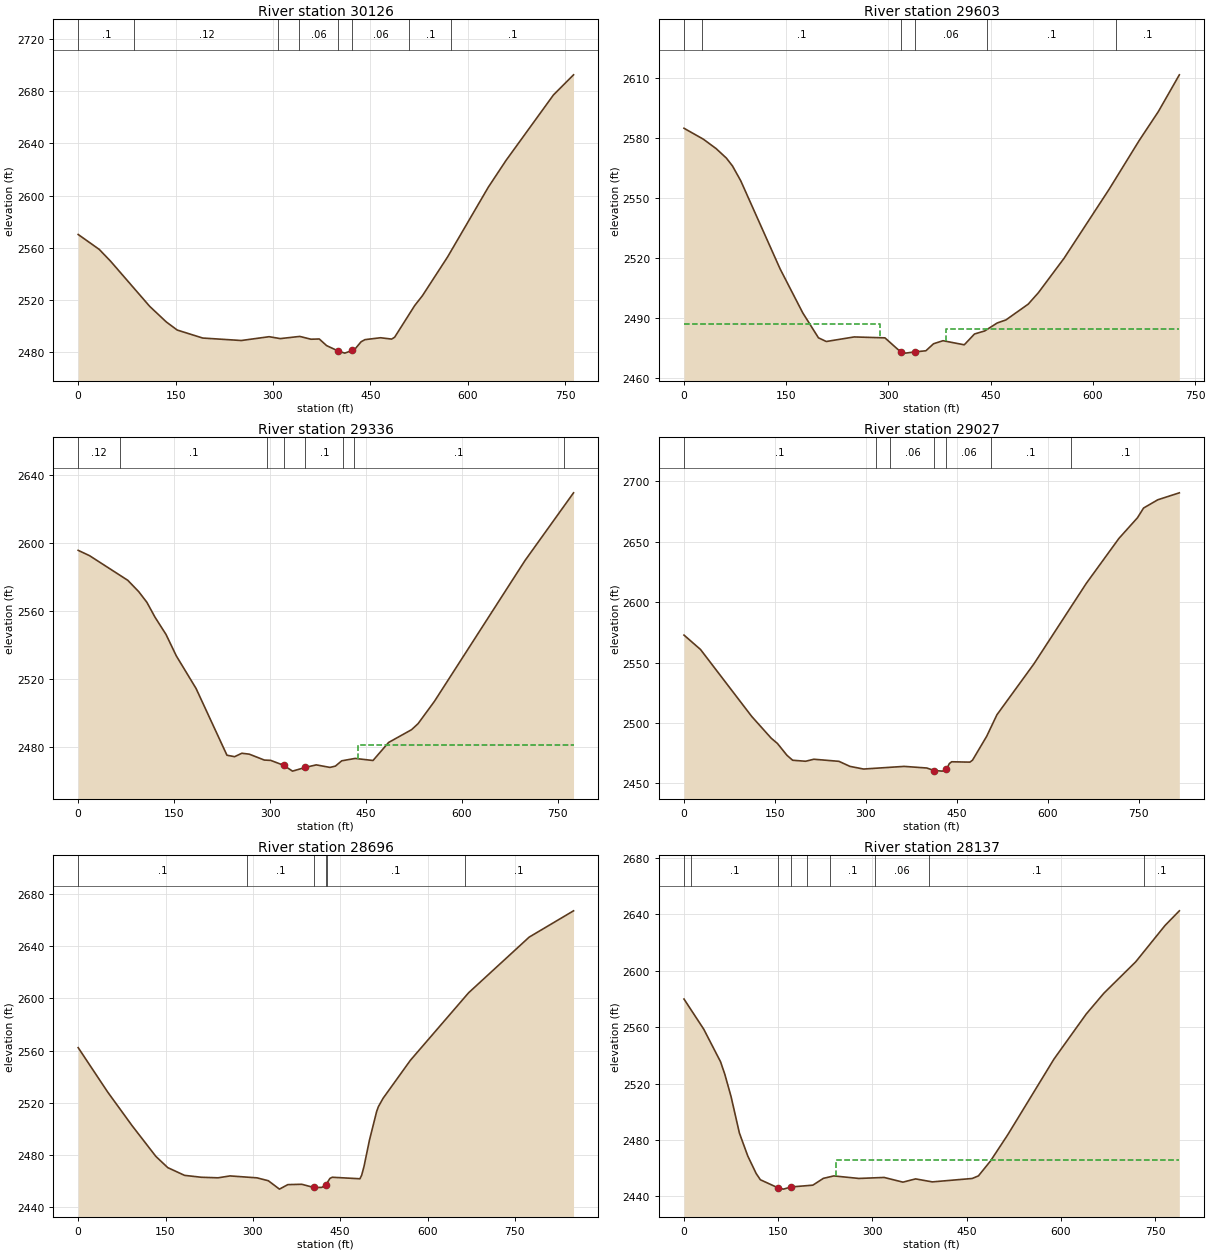
Type RM Length L Ch R = 1 ,30126   ,518.5,522.3,525.4
XS GIS Cut Line= 2
 2237596.1398758351332.8653103112237104.47320822351916.198789313
#Sta/Elev= 30
       0 2570.17    32.4 2558.75    49.8 2549.74   110.2 2515.05   135.8 2503.08
   152.5 2496.93   191.7 2490.79   251.2 2488.89   294.1 2491.81   311.3 2490.36
   341.3 2492.03   358.5 2489.88   371.3 2490.07   382.6 2484.99  400.792480.763
   410.6 2479.22  421.972481.278   426.9 2482.69   435.7 2487.93   441.8 2489.57
   465.7 2491.01   482.7 2489.98   487.4 2491.41   518.2 2515.63   530.1 2523.19
   568.9 2552.93   631.7 2606.47   658.8 2626.84     732 2677.15   762.9 2692.56
#Mann= 8 ,-1 , 0
       0      .1       0   86.63     .12       0  308.51      .1       0
  339.57     .06       0  400.79    .045       0  421.97     .06       0
  509.72      .1       0  574.81      .1       0
Bank Sta=400.79,421.97
XS Rating Curve= 0 ,0
Exp/Cntr=0.3,0.1

Type RM Length L Ch R = 1 ,29603   ,268.5,266.8,262.7
XS GIS Cut Line= 2
2237369.05634047351052.657209307 2236733.6396323351405.782159224
#Sta/Elev= 30
       0 2584.83    28.4 2579.37    47.1 2574.68    62.2 2569.92    71.2 2565.97
    83.3 2558.57     141 2514.59   174.2 2492.64   197.3 2480.13   208.8 2478.28
   249.8 2480.56   294.9  2480.1  317.912473.089     325 2472.47  338.552473.076
     355 2473.65   366.2 2477.16   380.1 2478.67   411.3 2476.63   426.3 2482.03
   441.3 2483.56   459.7 2487.55   472.4 2489.05   505.1 2496.94     520 2502.64
   557.7 2519.86   623.7 2554.27   668.3 2578.88   696.1 2593.17   726.9 2611.53
#Mann= 6 ,-1 , 0
       0     .12       0   26.25      .1       0  317.91    .045       0
  338.55     .06       0  444.46      .1       0  634.63      .1       0
#XS Ineff= 2 , 0
          287.49 2486.93  384.38         2484.52
Permanent Ineff=
       F       F
Bank Sta=317.91,338.55
XS Rating Curve= 0 ,0
Exp/Cntr=0.3,0.1

Type RM Length L Ch R = 1 ,29336   ,310.8,309.3,301.3
XS GIS Cut Line= 2
2237200.30634989350774.5321093952236605.51488855351270.365435317
#Sta/Elev= 30
       0 2595.83    17.7 2592.71    77.5 2578.21    94.6 2571.55   107.4 2565.27
   120.2 2556.44   137.3 2546.36   153.4 2533.74   184.3 2514.56   232.6 2475.28
   244.5 2474.43   255.9 2476.45   267.6  2475.9     291 2472.44   300.9 2472.26
  321.052469.393   335.1 2465.93   355.1 2468.11   372.2 2469.61   393.6 2468.12
   402.1 2468.88     412    2472     433  2473.4   460.9 2472.18   485.3 2482.79
   521.2 2490.31   531.5 2493.91   557.1 2507.08   698.5 2589.81   774.4 2629.67
#Mann= 8 ,-1 , 0
       0     .12       0   66.07      .1       0   295.4      .1       0
  321.05    .045       0   355.1      .1       0  414.75     .06       0
  430.65      .1       0  758.97      .1       0
#XS Ineff= 2 , 0
                          437.35         2481.03
Permanent Ineff=
       F       F
Bank Sta=321.05,355.1
XS Rating Curve= 0 ,0
Exp/Cntr=0.3,0.1

Type RM Length L Ch R = 1 ,29027   ,331.6,331,330.4
XS GIS Cut Line= 2
2236945.09819889350525.5736178162236416.97327089351148.490350977
#Sta/Elev= 30
       0 2572.72    27.2 2560.82   111.6 2505.38   143.8 2487.31     154 2482.99
   169.8 2473.12   179.1 2469.06   200.5 2468.22   214.1 2469.89   255.5 2468.15
   273.6 2463.98     296 2461.77     363 2463.97   400.3 2462.62  412.622460.523
   425.9 2460.04  432.712461.565   437.5 2466.29   441.3 2467.79   471.4 2467.49
   475.7 2469.11     499 2488.85   515.9 2506.69   577.2 2549.08   663.3 2615.58
   717.1  2652.8   747.6 2669.87   757.7 2677.95   781.1 2684.79   816.7 2690.56
#Mann= 7 ,-1 , 0
       0      .1       0  316.72      .1       0  340.38     .06       0
  412.62    .045       0  432.71     .06       0  506.04      .1       0
  638.49      .1       0
Bank Sta=412.62,432.71
XS Rating Curve= 0 ,0
Exp/Cntr=0.3,0.1

Type RM Length L Ch R = 1 ,28696   ,560.4,559.3,551.1
XS GIS Cut Line= 2
2236675.30641563350296.4070813952236162.80645639350975.573702067
#Sta/Elev= 30
       0 2562.29    50.5 2528.36    92.3 2502.63   133.4 2478.91   153.9 2470.27
   182.7 2464.35   211.5 2462.89   240.3 2462.47   260.8 2463.92   307.1 2462.44
   326.6 2460.23   345.7 2453.79   360.1 2457.25   384.1  2457.5  404.762455.042
   418.3 2455.11   425.12456.926   432.4    2462   436.4  2462.9   483.9 2461.73
   486.9 2464.45   490.9 2471.13   500.3 2491.38   512.6 2513.27   515.6 2517.01
   523.7 2523.46   570.6 2552.59   670.6 2604.38   774.6 2647.05   850.8 2667.22
#Mann= 6 ,-1 , 0
       0      .1       0  290.56      .1       0  404.76    .045       0
   425.1     .06       0  428.06      .1       0  663.98      .1       0
Bank Sta=404.76,425.1
XS Rating Curve= 0 ,0
Exp/Cntr=0.3,0.1

Type RM Length L Ch R = 1 ,28137   ,542.9,549.8,551.6
XS GIS Cut Line= 2
2236109.00439864350102.9176389722235963.17102888350877.917401314
#Sta/Elev= 30
       0 2579.97    31.5 2558.53    58.2 2535.43    64.9 2526.69    74.9 2510.79
    88.2 2484.85   101.6 2468.49   114.9 2456.11   121.6 2451.68   150.42445.813
   158.3 2445.03  170.532446.573   205.1 2447.84   221.9 2452.68   238.5 2454.41
   278.5 2452.61   318.6 2453.32   348.6 2449.99   368.7 2452.29   395.4 2450.17
   458.8 2452.59   468.8 2454.45   488.1  2465.1   515.6 2483.75     589 2537.35
   640.4 2569.36   668.5 2584.12   719.2 2606.43   765.9 2632.23   788.6 2642.59
#Mann= 9 ,-1 , 0
       0      .1       0   10.99      .1       0   150.4    .045       0
  170.53      .1       0   196.6      .1       0     233      .1       0
  303.84     .06       0  389.95      .1       0  732.93      .1       0
#XS Ineff= 2 , 0
                          241.77         2465.95
Permanent Ineff=
       F       F
Bank Sta=150.4,170.53
XS Rating Curve= 0 ,0
Exp/Cntr=0.3,0.1

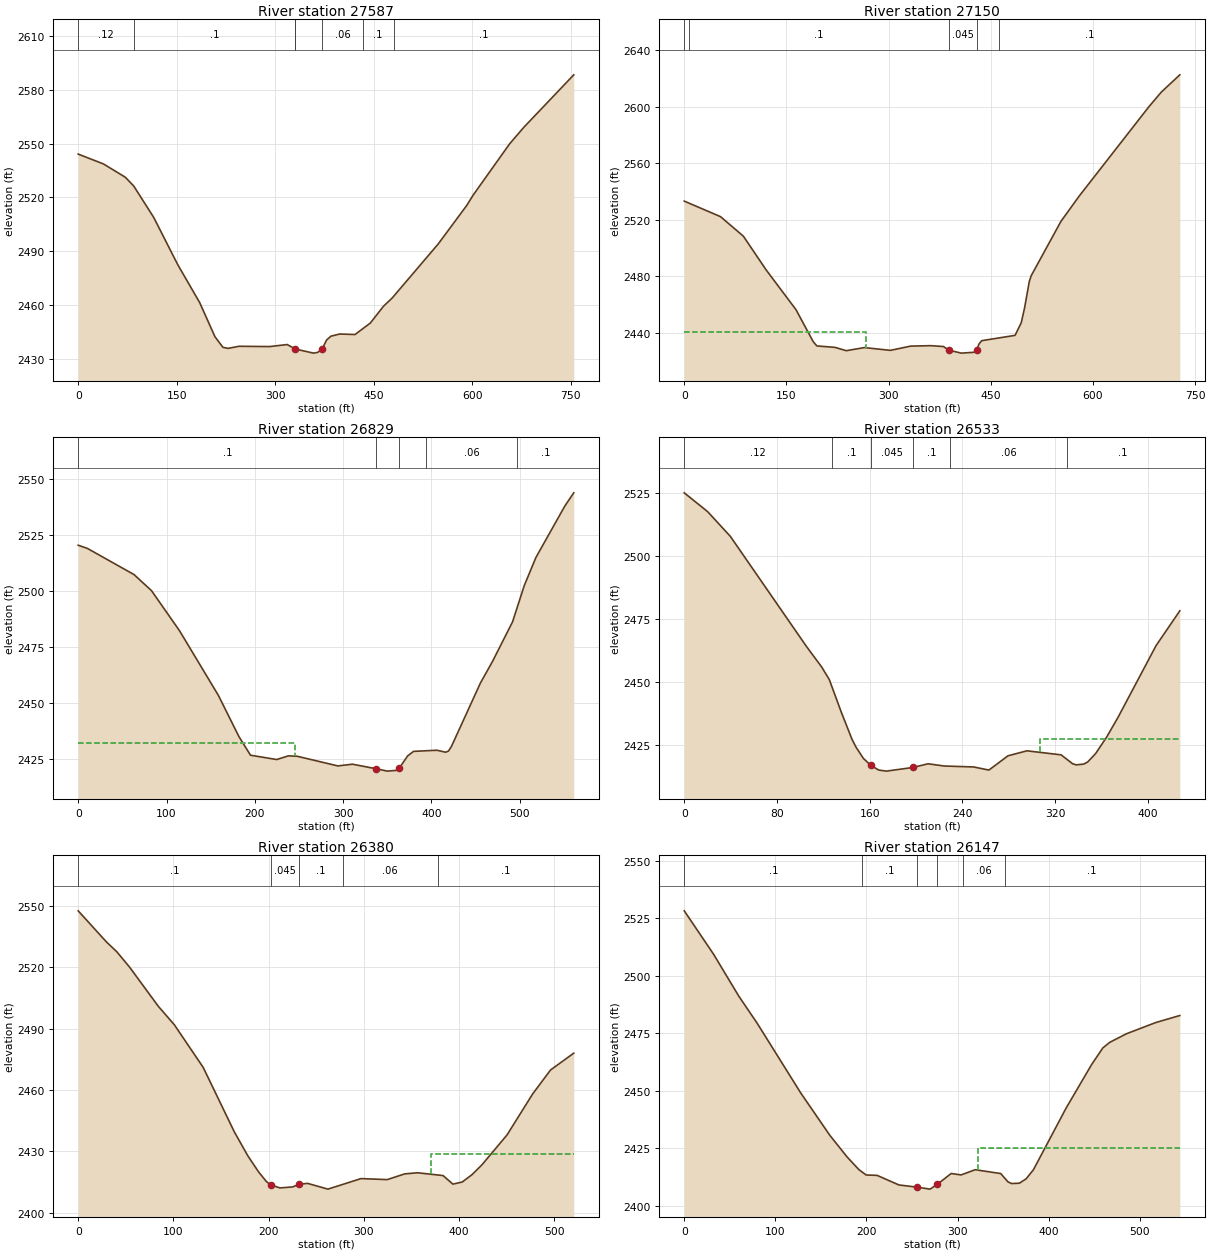
Type RM Length L Ch R = 1 ,27587   ,413.8,436.9,451.2
XS GIS Cut Line= 2
2235613.17107272350050.1398573962235481.22645472350793.195129812
#Sta/Elev= 30
       0  2544.2    38.4 2538.73    71.7 2531.32    84.6  2526.4     115 2508.91
   151.7 2482.49     185 2461.41   208.3 2442.35   220.4 2436.45   228.3 2435.86
     245 2437.03   291.6 2436.87   318.3 2437.99   330.8 2435.49   358.3 2433.21
   364.9 2433.64   371.6 2435.59   378.3 2440.51   384.9 2442.66   398.3 2443.87
   421.6 2443.59   444.9 2449.99   464.9 2459.34   478.2 2463.96   548.2 2494.06
   591.5 2515.45   601.5 2521.34   656.9 2549.87   678.8  2559.2   754.7 2588.41
#Mann= 7 ,-1 , 0
       0     .12       0   84.86      .1       0  330.04     .06       0
   330.8    .045       0   371.6     .06       0  433.12      .1       0
  480.74      .1       0
Bank Sta=330.8,371.6
XS Rating Curve= 0 ,0
Exp/Cntr=0.3,0.1

Type RM Length L Ch R = 1 ,27150   ,310.2,320.6,330.1
XS GIS Cut Line= 2
2235550.67119773350009.8620508162234909.00450206350352.917467058
#Sta/Elev= 30
       0  2533.3    53.3 2522.28    86.8 2508.47   120.3 2484.55   164.2 2456.32
   189.4 2433.73   194.7 2430.75   221.2 2429.75   237.9 2427.39   264.5 2429.59
   302.6 2427.62   332.4 2430.62   361.5 2430.94   380.7 2430.33   388.1  2427.8
   406.7 2425.66   425.3 2426.25   429.1 2427.87   432.8 2432.14   436.7 2434.47
   485.7 2438.24   494.8 2447.21   499.7 2457.76   506.6 2476.39   509.4 2480.49
     553 2518.91   579.7 2536.77     682 2600.02   700.6 2610.59   727.6 2622.72
#Mann= 5 ,-1 , 0
       0     .12       0    6.47      .1       0   388.1    .045       0
   429.1      .1       0  461.85      .1       0
#XS Ineff= 2 , 0
          266.67 2440.52
Permanent Ineff=
       F       F
Bank Sta=388.1,429.1
XS Rating Curve= 0 ,0
Exp/Cntr=0.3,0.1

Type RM Length L Ch R = 1 ,26829   ,299.8,296.5,294.3
XS GIS Cut Line= 2
2235481.22645472349930.695214391 2234922.8932538349875.139551222
#Sta/Elev= 30
       0  2520.3    10.4 2518.88    63.2 2507.22      83 2500.06   114.7 2482.21
   158.8 2453.35   181.9 2435.09   195.1 2426.73   224.7 2424.81   237.9 2426.44
   247.8 2426.28     294 2421.96   310.5 2422.73  337.632420.678     350 2419.64
   359.9 2419.96   363.6 2421.01   373.1 2426.46   379.7 2428.44   406.1 2428.95
     416 2428.07   419.3  2428.6   422.6 2430.64   455.5 2458.97     469 2468.44
   491.8 2486.15     505 2502.26   518.2  2514.8   551.1 2537.83   561.1 2543.64
#Mann= 5 ,-1 , 0
       0      .1       0  337.63    .045       0   363.6      .1       0
  394.29     .06       0  497.07      .1       0
#XS Ineff= 2 , 0
          245.16 2432.36
Permanent Ineff=
       F       F
Bank Sta=337.63,363.6
XS Rating Curve= 0 ,0
Exp/Cntr=0.3,0.1

Type RM Length L Ch R = 1 ,26533   ,154.8,152.4,148.4
XS GIS Cut Line= 2
2235372.89333805349602.9173266442234945.11565031349609.861866564
#Sta/Elev= 30
       0 2525.25    20.2 2517.76    39.8 2507.92   105.5 2464.13   118.6 2455.98
   125.2 2450.96   135.5 2438.06   144.8 2427.21   148.1  2424.2   154.7 2419.55
   161.1 2416.81   167.8 2414.97   174.4 2414.53   197.3 2415.98   210.5 2417.45
   224.5 2416.56   249.8 2416.19     263 2414.95   279.4 2420.61   295.8 2422.61
   325.3 2421.01   335.2 2417.49   338.4 2417.01     345 2417.35   348.3 2418.19
   355.1 2421.51   364.8  2428.2   374.5 2435.97   407.3 2464.47   427.8 2478.32
#Mann= 6 ,-1 , 0
       0     .12       0  127.34      .1       0   161.1    .045       0
   197.3      .1       0  229.66     .06       0  330.04      .1       0
#XS Ineff= 2 , 0
                          307.02         2427.26
Permanent Ineff=
       F       F
Bank Sta=161.1,197.3
XS Rating Curve= 0 ,0
Exp/Cntr=0.3,0.1

Type RM Length L Ch R = 1 ,26380   ,234.8,233.6,220.8
XS GIS Cut Line= 2
2235392.33785297349409.8619384772234884.00422397 349520.97293672
#Sta/Elev= 30
       0 2547.64    29.6 2532.45    40.5 2527.65      54 2520.07    84.2  2500.9
     101 2491.88   131.2 2471.09     164 2439.45   178.2 2427.74   189.5 2419.86
   197.7 2415.18  201.952413.642   211.8  2412.1   225.2 2412.59     232 2413.89
   240.8 2414.33   262.2 2411.51   296.9 2416.66   324.5 2416.17   342.8 2418.96
   356.2 2419.52   383.1 2418.14   393.4 2413.95   403.2 2414.99   413.3 2418.52
   423.7  2423.3   450.2 2437.99   477.1 2458.04   495.9 2469.78   520.3 2478.02
#Mann= 5 ,-1 , 0
       0      .1       0  201.95    .045       0     232      .1       0
  277.79     .06       0  377.26      .1       0
#XS Ineff= 2 , 0
                          370.12         2428.54
Permanent Ineff=
       F       F
Bank Sta=201.95,232
XS Rating Curve= 0 ,0
Exp/Cntr=0.3,0.1

Type RM Length L Ch R = 1 ,26147   ,216.8,213.3,209.4
XS GIS Cut Line= 2
2235247.89325997349150.139688894 2234800.6710573349459.861838475
#Sta/Elev= 30
       0 2528.25    32.1 2509.44      60 2491.08    79.9 2479.47   127.9 2449.05
   159.8 2430.66   178.9 2421.19   191.7 2415.74   199.7  2413.4   211.7 2413.24
   235.6 2409.08   255.6 2408.11   269.9 2407.26   277.9 2409.36     293 2414.06
   303.9 2413.43   319.4  2415.7   347.4 2414.03   355.4 2410.41   359.3 2409.69
   367.9 2409.84   375.3 2411.74   383.3 2415.69   419.4 2442.66   447.1 2461.37
   459.5 2468.65   467.1 2471.08   485.4  2474.8   517.7  2479.7     544 2482.74
#Mann= 6 ,-1 , 0
       0      .1       0   195.4      .1       0   255.6    .045       0
   277.9      .1       0  305.44     .06       0  351.68      .1       0
#XS Ineff= 2 , 0
                           321.9         2425.33
Permanent Ineff=
       F       F
Bank Sta=255.6,277.9
XS Rating Curve= 0 ,0
Exp/Cntr=0.3,0.1

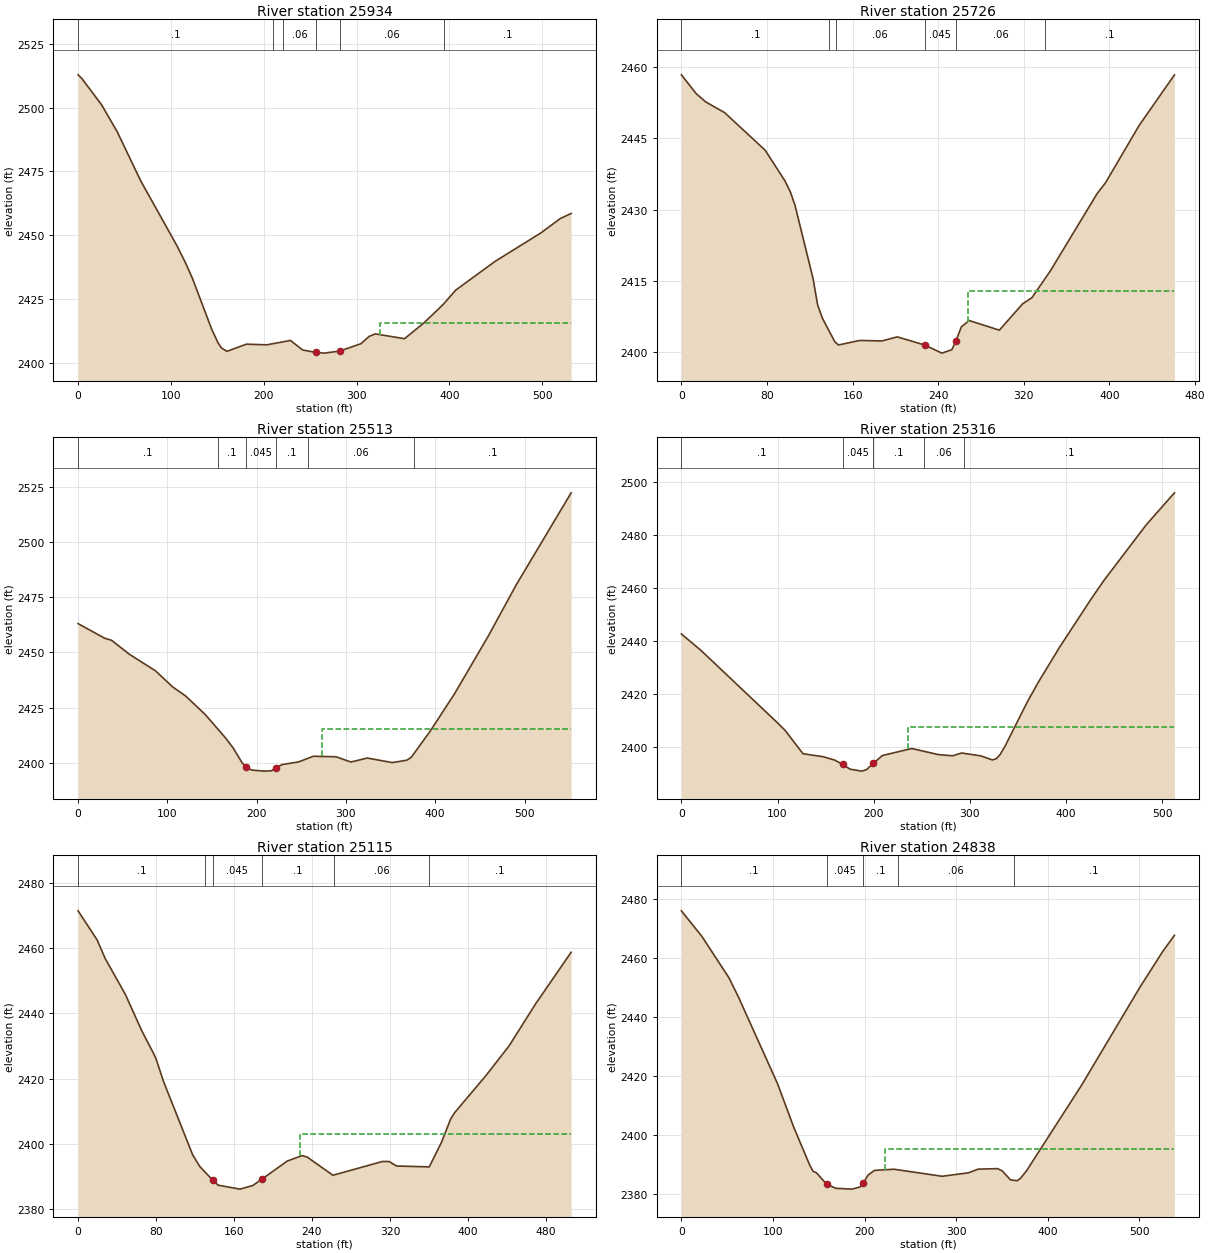
Type RM Length L Ch R = 1 ,25934   ,207,207.6,207.8
XS GIS Cut Line= 2
2235089.55991521348916.806494147 2234753.4487108349327.917548567
#Sta/Elev= 30
       0 2512.86     4.1 2511.41    25.3 2501.13    42.2 2490.51    67.6 2471.19
   106.7  2445.7     116 2438.89     123 2433.17     144 2413.02   150.9 2407.65
   154.4 2405.76   160.3 2404.41   181.3 2407.23   203.2 2406.96   228.7 2408.68
   241.9 2404.93   255.9 2404.01   265.2 2403.71   281.92404.528   304.7 2407.42
   313.4 2410.26   320.2 2411.25   351.6 2409.37   372.1 2415.45   392.8 2422.64
   406.7 2428.42     449 2439.67   498.4 2450.85   519.3 2456.48     531 2458.49
#Mann= 6 ,-1 , 0
       0      .1       0  209.39      .1       0  220.73     .06       0
   255.9    .045       0   281.9     .06       0  393.74      .1       0
#XS Ineff= 2 , 0
                          324.96         2415.38
Permanent Ineff=
       F       F
Bank Sta=255.9,281.9
XS Rating Curve= 0 ,0
Exp/Cntr=0.3,0.1

Type RM Length L Ch R = 1 ,25726   ,216.7,212.6,213.6
XS GIS Cut Line= 2
2234924.28203055 348804.306391062234621.50442089349151.528465644
#Sta/Elev= 30
       0 2458.28    14.1 2454.27    22.8 2452.58    40.3 2450.36    78.3 2442.45
    96.9 2435.97   101.9 2433.65   106.2 2430.86     123 2415.53   127.3 2409.97
   131.7 2407.21   143.4 2402.21   146.8 2401.55   166.5  2402.5   187.5  2402.4
   201.7 2403.25   227.4 2401.54   243.4 2399.84   252.7 2400.55   256.6 2402.43
   261.6 2405.35   268.9 2406.69   297.1 2404.66   318.9  2410.2   327.6  2411.5
     345 2417.19   388.5 2433.35   396.4 2435.65   427.7 2447.65   460.7 2458.27
#Mann= 6 ,-1 , 0
       0      .1       0  138.14      .1       0  144.24     .06       0
   227.4    .045       0   256.6     .06       0   339.7      .1       0
#XS Ineff= 2 , 0
                           267.4         2412.86
Permanent Ineff=
       F       F
Bank Sta=227.4,256.6
XS Rating Curve= 0 ,0
Exp/Cntr=0.3,0.1

Type RM Length L Ch R = 1 ,25513   ,200.3,197.2,197.8
XS GIS Cut Line= 2
2234802.05983405348639.0285063982234456.22653621349069.584075734
#Sta/Elev= 30
       0 2463.04    29.8 2456.41    37.5 2455.49    57.3 2449.21    86.8 2441.65
   105.6  2434.5   120.5 2430.27   142.3 2421.95   165.2 2411.29   173.7 2406.76
   183.8 2400.03   188.5 2397.97   194.6 2396.76   208.8 2396.29   216.5 2396.43
  221.832397.752   228.2 2399.22   246.9 2400.45   263.5 2403.01   288.9 2402.78
   305.6 2400.41   323.9 2402.21   351.9 2400.15   368.2 2401.23     373 2402.48
     394 2414.16   421.9 2431.47   459.2 2457.25   490.8 2480.62   552.2  2522.2
#Mann= 6 ,-1 , 0
       0      .1       0   156.3      .1       0   188.5    .045       0
  221.83      .1       0  257.41     .06       0  375.87      .1       0
#XS Ineff= 2 , 0
                          273.68         2415.18
Permanent Ineff=
       F       F
Bank Sta=188.5,221.83
XS Rating Curve= 0 ,0
Exp/Cntr=0.3,0.1

Type RM Length L Ch R = 1 ,25316   ,206.5,201.4,199.8
XS GIS Cut Line= 2
2234600.67112923348562.6395515652234307.61561297348983.473027483
#Sta/Elev= 30
       0 2442.62    20.5 2436.37    99.6 2409.27   107.7 2406.37   126.5  2397.5
   147.6 2396.36   159.6 2395.09   167.6 2393.51   175.5 2391.69   187.5 2390.95
   192.5  2391.5   199.6 2393.85   199.6 2393.86     209 2396.82   239.6 2399.47
   267.5 2397.16   282.1 2396.72   291.5 2397.78   311.5 2396.68   323.5 2395.16
   327.5 2395.62   331.5  2397.2   336.3 2400.13   359.8 2417.01   371.4 2424.53
   392.8  2437.3   425.8 2455.57   439.4 2462.73   483.4 2483.68   512.8 2495.75
#Mann= 5 ,-1 , 0
       0      .1       0   167.6    .045       0   199.6      .1       0
  252.36     .06       0  294.15      .1       0
#XS Ineff= 2 , 0
                          235.99         2407.74
Permanent Ineff=
       F       F
Bank Sta=167.6,199.6
XS Rating Curve= 0 ,0
Exp/Cntr=0.3,0.1

Type RM Length L Ch R = 1 ,25115   ,284,277.1,276.4
XS GIS Cut Line= 2
2234413.17117614348445.9731182312234171.50433664348890.417439312
#Sta/Elev= 30
       0 2471.43    19.6  2462.5    27.9 2456.79    48.6 2445.79    65.5 2434.61
    77.6 2427.68    80.2 2425.94    87.6 2419.24   117.5 2396.75     125 2393.09
   138.1 2388.97   143.7 2387.41   166.1  2386.2   179.2  2387.3   188.9 2389.31
   214.6 2394.79   229.6 2396.45   234.9 2396.06   261.5 2390.45   312.3 2394.66
   319.2 2394.65   326.7 2393.28   360.3 2393.01   372.8  2400.5   382.4 2407.75
   386.4 2409.62   418.7 2421.05   442.4 2430.14   469.5 2442.97   505.9 2458.74
#Mann= 6 ,-1 , 0
       0      .1       0  130.64      .1       0   138.1    .045       0
   188.9      .1       0  262.13     .06       0  360.15      .1       0
#XS Ineff= 2 , 0
                           227.5         2403.12
Permanent Ineff=
       F       F
Bank Sta=138.1,188.9
XS Rating Curve= 0 ,0
Exp/Cntr=0.3,0.1

Type RM Length L Ch R = 1 ,24838   ,185.7,178.9,173.3
XS GIS Cut Line= 2
2234132.61563489348359.8620699792233932.61537872348859.862054229
#Sta/Elev= 30
       0 2476.04    22.3 2467.44      52 2453.35    62.5 2446.75     105 2417.53
   122.7 2402.78   140.3 2389.86   143.9 2387.82   147.4 2387.37   158.6 2383.49
   168.7 2382.09   186.3 2381.81   195.3 2382.56   198.9 2383.94   203.9 2386.59
     211 2388.16   232.2 2388.55   284.8 2386.16   313.5 2387.33   324.1 2388.58
   345.3 2388.75   350.4    2388   359.4 2384.96   366.5 2384.66     370 2385.32
   377.1 2388.08   437.2 2417.06   500.8 2450.16   525.5 2462.19   538.5 2467.75
#Mann= 5 ,-1 , 0
       0      .1       0   158.6    .045       0   198.9      .1       0
  236.23     .06       0  362.92      .1       0
#XS Ineff= 2 , 0
                          222.75         2395.45
Permanent Ineff=
       F       F
Bank Sta=158.6,198.9
XS Rating Curve= 0 ,0
Exp/Cntr=0.3,0.1