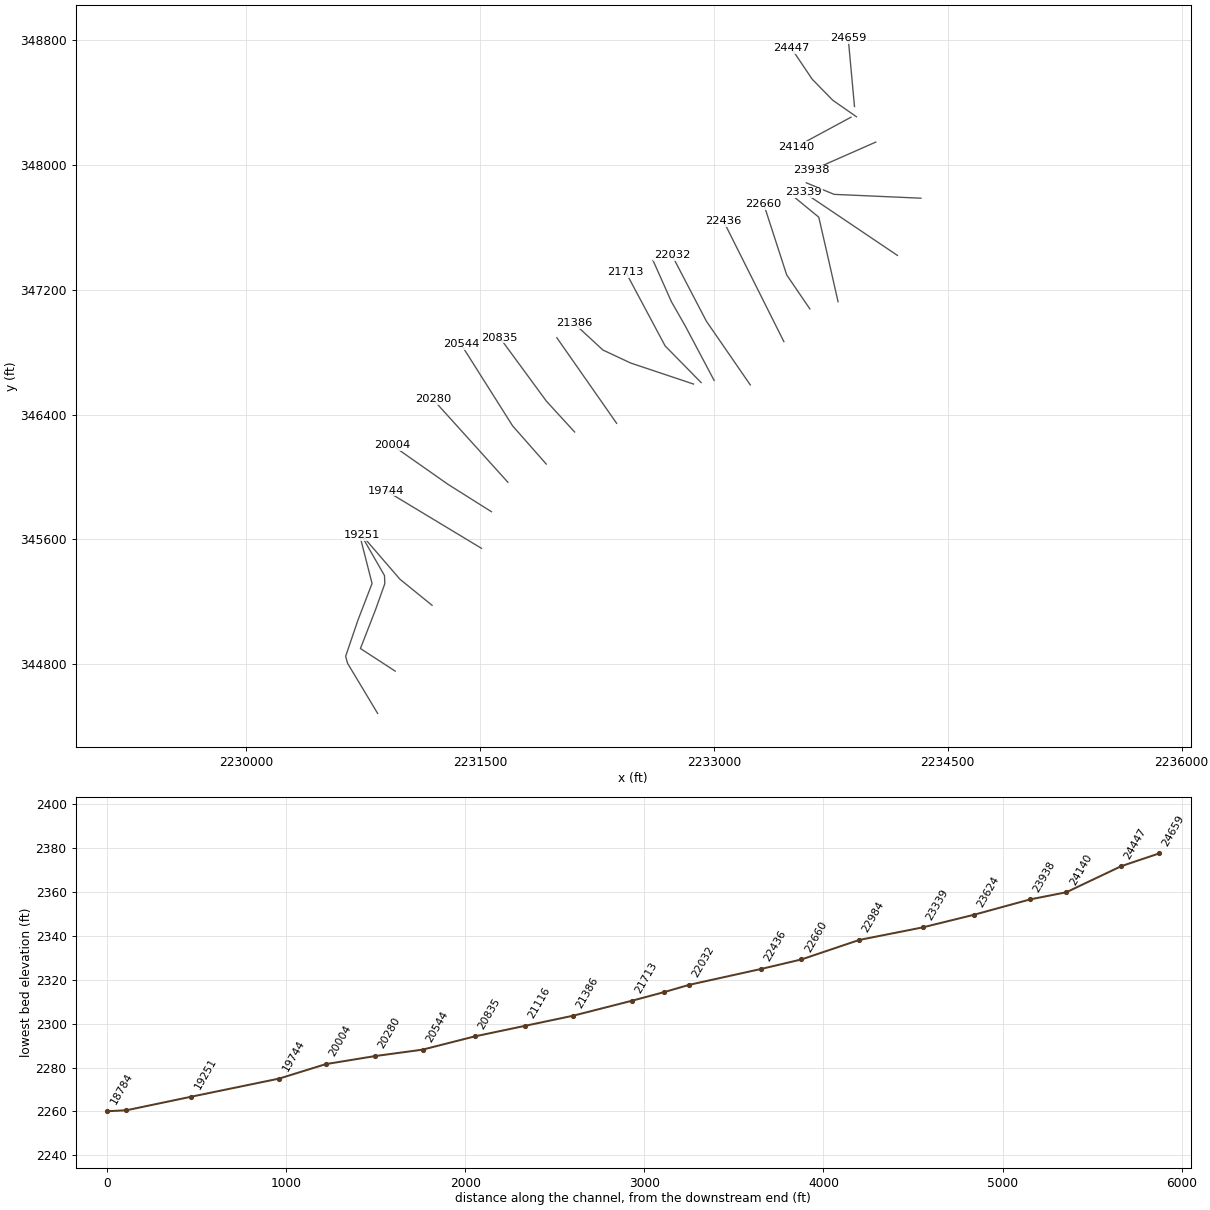
HEC-RAS study MEADOWCK1.prj: MEADOWCK1

--- MEADOWCK1.g01 (geometry) --- (continued)

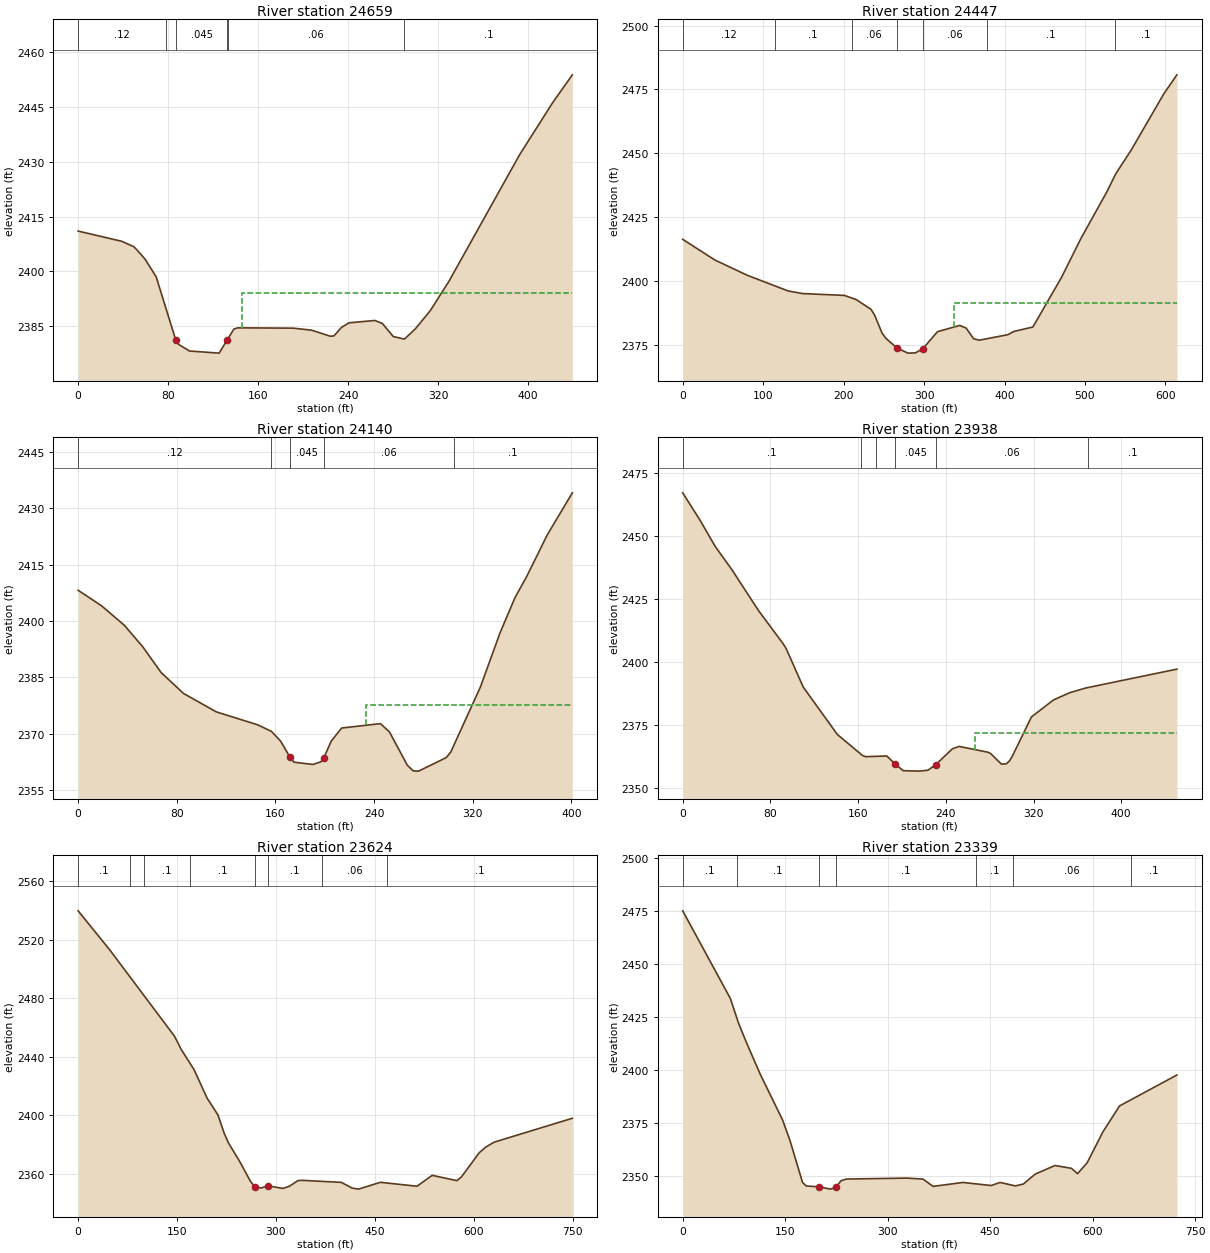
Type RM Length L Ch R = 1 ,24659   ,201.2,211.7,221.7
XS GIS Cut Line= 2
2233902.05999364348375.1395984742233861.78218706348812.639707729
#Sta/Elev= 30
       0 2411.05    38.9 2408.24    49.6 2406.76    52.9 2405.69    59.5 2403.39
    69.4 2398.54    85.9 2382.16    87.2 2381.33    89.2  2380.1      99 2378.26
   125.4 2377.68   132.4 2381.22   138.5 2384.26   141.9 2384.59   191.3 2384.51
   207.8 2383.94   224.2  2382.3   227.5 2382.39   234.1  2384.7   240.7 2385.96
   263.8 2386.61   270.4 2385.81   280.2 2382.22   290.1 2381.51     300 2384.38
   313.2 2389.33   329.7 2397.32   392.7 2432.01     422 2446.19   439.4 2453.76
#Mann= 6 ,-1 , 0
       0     .12       0   78.55      .1       0    87.2    .045       0
   132.4      .1       0  133.54     .06       0  289.95      .1       0
#XS Ineff= 2 , 0
                          145.44         2394.05
Permanent Ineff=
       F       F
Bank Sta=87.2,132.4
XS Rating Curve= 0 ,0
Exp/Cntr=0.3,0.1

Type RM Length L Ch R = 1 ,24447   ,286.7,306.9,325.9
XS GIS Cut Line= 4
2233914.55996864348309.861841887 2233763.1711638348415.417405054
2233631.22654581348550.1395765542233496.50437431 348750.13983272
#Sta/Elev= 30
       0 2416.38    39.9 2408.31    80.1 2402.34     131 2396.19   148.9 2395.17
     201 2394.44   215.4 2392.86   234.1 2388.98   238.5 2386.77   247.8 2379.72
   252.5 2377.67   266.4 2373.86     280 2371.87   289.2 2371.97   298.4 2373.56
   316.7 2380.26   344.3  2382.7   352.3 2381.67   361.5 2377.53   368.5 2376.92
   404.1 2379.08   411.6 2380.34   435.3 2382.09   470.9 2401.52   494.6 2416.48
   527.5 2435.12   538.2 2441.97   557.5 2451.28   597.9 2473.23   614.3 2480.71
#Mann= 7 ,-1 , 0
       0     .12       0  114.27      .1       0  209.89     .06       0
   266.4    .045       0   298.4     .06       0  377.92      .1       0
   537.2      .1       0
#XS Ineff= 2 , 0
                          337.13         2391.48
Permanent Ineff=
       F       F
Bank Sta=266.4,298.4
XS Rating Curve= 0 ,0
Exp/Cntr=0.3,0.1

Type RM Length L Ch R = 1 ,24140   ,204.9,202.6,200.2
XS GIS Cut Line= 2
2233879.83759713348307.0842883882233527.06008747 348116.80645372
#Sta/Elev= 30
       0 2408.18    18.9 2404.07    37.5 2398.85    52.4 2393.12    67.3 2386.25
    85.4  2380.7     112 2375.77   145.6 2372.32   156.8 2370.56   164.2 2367.98
   171.7 2363.75     175 2362.36   190.3 2361.75   196.8 2362.44   199.2 2363.46
   205.2 2367.94   213.7 2371.46   245.2 2372.63   252.5 2370.41     267 2361.53
   271.8 2360.03   276.1 2359.97   298.5 2363.57   302.2 2365.06   326.2 2382.36
   342.1 2396.78   354.3 2406.23   363.9 2411.93   380.4  2422.9   400.8 2434.16
#Mann= 5 ,-1 , 0
       0     .12       0   156.8     .06       0   171.7    .045       0
   199.2     .06       0  304.57      .1       0
#XS Ineff= 2 , 0
                          233.73         2377.59
Permanent Ineff=
       F       F
Bank Sta=171.7,199.2
XS Rating Curve= 0 ,0
Exp/Cntr=0.3,0.1

Type RM Length L Ch R = 1 ,23938   ,335.5,313.7,332.1
XS GIS Cut Line= 2
2234038.17094189348147.3618388182233625.67111072347965.417648897
#Sta/Elev= 30
       0 2467.23    15.5 2456.58    29.8 2445.83    44.4 2437.01    69.3 2420.38
    91.7 2407.25    94.4 2405.34   109.9 2390.12     141 2371.28   163.8 2362.99
   166.8 2362.44   186.2 2362.71   193.7 2359.57   201.1 2356.88   216.3  2356.7
   223.7 2357.07     231 2359.33   245.9 2365.53   252.1 2366.52   278.3 2364.22
   280.8 2363.72   290.7 2359.49   295.2 2359.59   298.2 2360.83   300.7 2362.66
   318.1 2378.22   338.2 2384.96   352.9 2387.83   367.8 2389.73   450.8 2397.21
#Mann= 6 ,-1 , 0
       0      .1       0  162.33     .12       0   176.2     .06       0
   193.7    .045       0     231     .06       0  369.84      .1       0
#XS Ineff= 2 , 0
                          266.84         2372.01
Permanent Ineff=
       F       F
Bank Sta=193.7,231
XS Rating Curve= 0 ,0
Exp/Cntr=0.3,0.1

Type RM Length L Ch R = 1 ,23624   ,287.9,284.9,277
XS GIS Cut Line= 3
2234327.64384489347787.7450021442233771.46246283347812.341526595
2233593.26879745347886.336807927
#Sta/Elev= 30
       0 2539.65    47.8 2513.09   146.3 2454.01   156.1 2445.23   175.9 2431.23
   195.6 2411.85     212 2400.42   221.8 2387.57   228.3 2381.06   244.8 2368.79
   261.2 2355.18   267.8  2351.4   277.7 2350.43   287.5    2352   310.5 2350.16
   320.4 2351.65   333.5 2355.51   340.1 2355.69   399.2  2354.3   415.6 2350.42
   425.4 2349.69   458.5 2354.34   514.1 2351.67   537.1  2359.1   574.6 2355.48
   581.7 2358.16   608.5 2374.56   618.5 2378.45   631.1 2381.75   749.7 2398.06
#Mann= 8 ,-1 , 0
       0      .1       0    78.3     .12       0  100.04      .1       0
  170.07      .1       0   267.8    .045       0   287.5      .1       0
  370.68     .06       0  469.09      .1       0
Bank Sta=267.8,287.5
XS Rating Curve= 0 ,0
Exp/Cntr=0.3,0.1

Type RM Length L Ch R = 1 ,23339   ,364,355.5,343.4
XS GIS Cut Line= 2
2234177.05977172347420.9731997252233577.05998747347825.139714226
#Sta/Elev= 30
       0 2474.92    69.8 2433.66    81.6 2422.19    93.3 2412.95   113.3 2398.18
   146.2  2376.5   156.9 2366.98   175.5 2347.05   180.9 2345.45  199.57 2345.06
   216.4 2343.97   224.1  2344.9     232 2347.98   239.9 2348.72   328.2 2349.16
   351.7 2348.69   366.5 2345.26   410.2 2347.11   451.5 2345.66   464.5 2347.12
   486.8 2345.48   498.5 2346.35   516.1 2351.06   544.9 2355.08     569 2353.77
     578 2351.23   592.2 2356.47   615.2 2370.99   639.5 2383.13   723.4 2397.68
#Mann= 7 ,-1 , 0
       0      .1       0   79.78      .1       0  199.57    .045       0
   224.1      .1       0  428.94      .1       0   484.1     .06       0
  655.61      .1       0
Bank Sta=199.57,224.1
XS Rating Curve= 0 ,0
Exp/Cntr=0.3,0.1

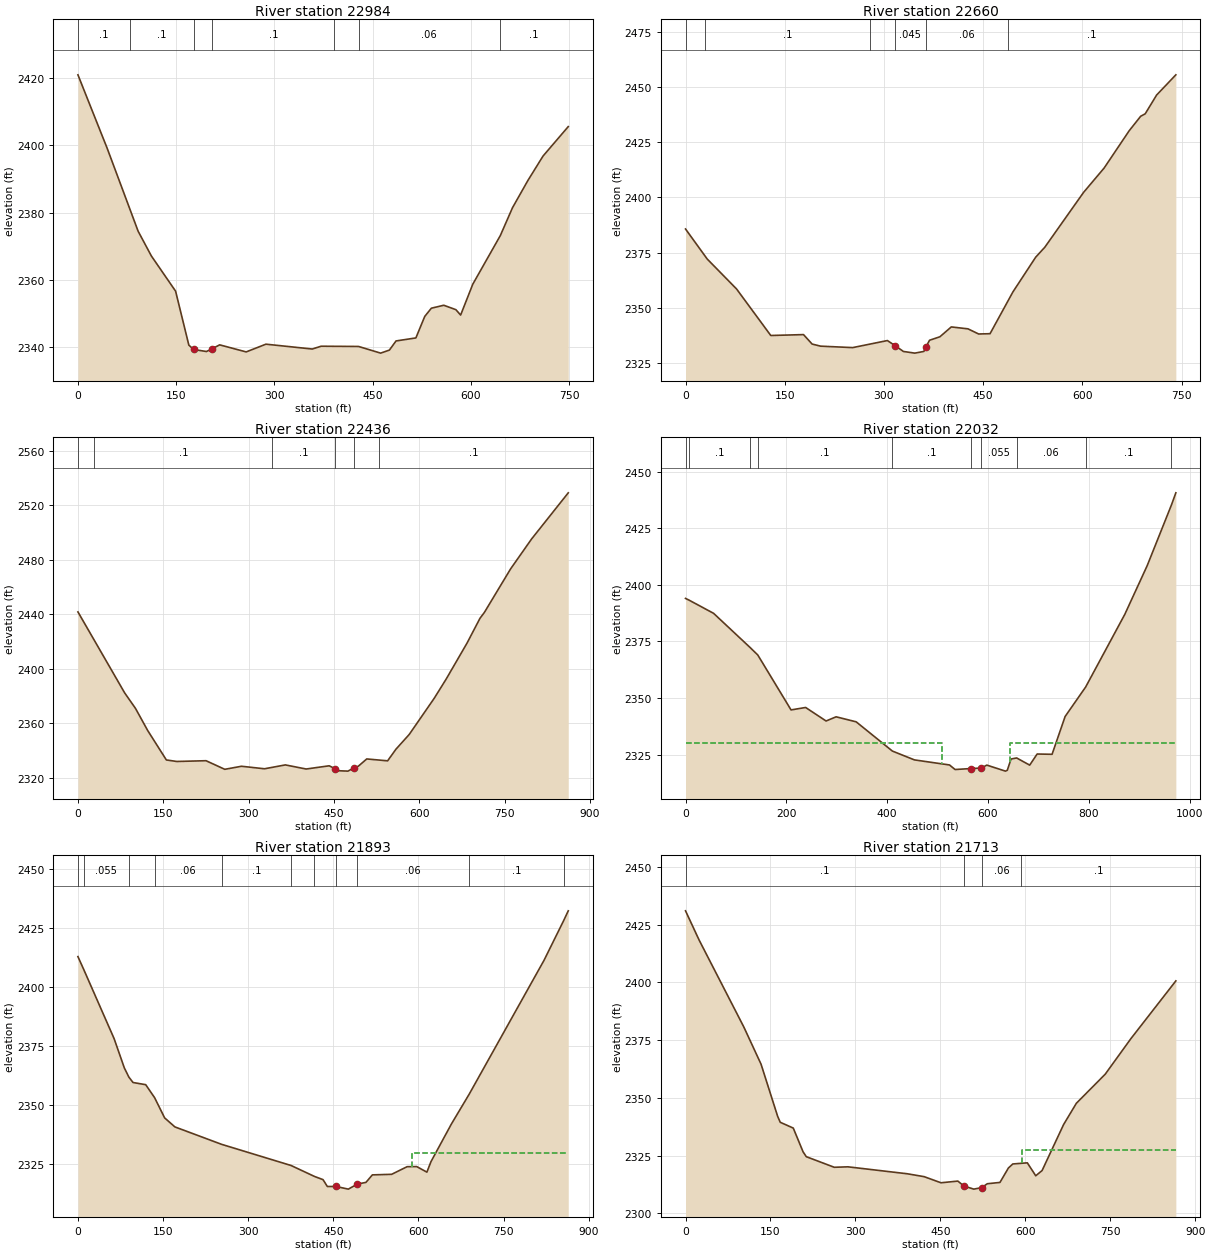
Type RM Length L Ch R = 1 ,22984   ,312.1,323.3,324.3
XS GIS Cut Line= 4
2233796.54328122347124.2552951352233725.50802675347437.849376817
2233673.02725995347666.0400454042233523.95578179347788.314752225
#Sta/Elev= 30
       0 2420.93    44.8 2399.02    91.9 2374.45   112.1  2367.1   149.1 2356.63
   169.3 2340.61   176.62339.303   196.2  2338.7   205.22339.563   216.4 2340.68
   256.8 2338.58     287 2340.88   357.7 2339.44   371.2 2340.27   428.4  2340.2
   462.1 2338.22   475.5 2339.13   485.6 2341.84   515.9 2342.74   529.4 2349.12
   539.5 2351.57   558.5 2352.45     577 2351.13   584.2 2349.53   602.8 2358.72
   644.8 2373.16   663.4 2381.44   686.7 2389.47     710 2396.79   748.5 2405.54
#Mann= 7 ,-1 , 0
       0      .1       0   79.22      .1       0   176.6    .045       0
   205.2      .1       0  391.54      .1       0  428.55     .06       0
  644.08      .1       0
Bank Sta=176.6,205.2
XS Rating Curve= 0 ,0
Exp/Cntr=0.3,0.1

Type RM Length L Ch R = 1 ,22660   ,219.3,224.6,226.3
XS GIS Cut Line= 3
2233615.94868922 347077.917455392233467.33776598347295.973121643
2233320.11561947347750.139864221
#Sta/Elev= 30
       0  2385.7    32.8 2372.06    77.2 2358.45   128.9 2337.33   178.4 2337.73
   191.4 2333.44   204.3 2332.48   252.8 2331.83   305.2 2335.03   316.8 2332.73
   329.4 2330.08   346.6 2329.32   360.4 2330.09   363.1 2331.92   368.9 2335.16
   384.6 2336.75   401.8 2341.22     427 2340.35   443.2 2338.01   460.4 2338.14
   494.9 2357.08   529.4 2372.89   543.2 2377.41   601.8 2402.32   632.9 2413.39
   670.8 2430.33   688.1 2436.88     695 2438.02   712.2 2446.52   741.3 2455.71
#Mann= 6 ,-1 , 0
       0      .1       0    29.7      .1       0  279.14      .1       0
   316.8    .045       0   363.1     .06       0  487.44      .1       0
Bank Sta=316.8,363.1
XS Rating Curve= 0 ,0
Exp/Cntr=0.3,0.1

Type RM Length L Ch R = 1 ,22436   ,400.1,403.2,403.1
XS GIS Cut Line= 2
2233449.28202781346868.1951058062233063.17092338347639.028537899
#Sta/Elev= 30
       0 2441.82    82.1 2382.45   101.3 2370.96   122.7 2354.77   155.5 2333.19
   173.8 2332.08   225.2 2332.64   258.2 2326.33   287.6 2328.57     328 2326.73
   364.7 2329.56   401.3 2326.55   441.7 2328.91   452.7  2326.7   460.1 2325.25
   474.7    2325   484.6 2327.25   493.1 2328.65   507.8 2333.94   544.5 2332.55
   559.1 2341.06   582.4 2351.86   626.4 2378.42   647.2 2392.36   683.9 2418.77
     707  2437.2   714.4 2441.29   760.8 2473.43   797.6 2495.31   862.1 2529.19
#Mann= 6 ,-1 , 0
       0      .1       0   28.74      .1       0  341.92      .1       0
   452.7    .045       0   484.6     .06       0  530.06      .1       0
Bank Sta=452.7,484.6
XS Rating Curve= 0 ,0
Exp/Cntr=0.5,0.3

Type RM Length L Ch R = 1 ,22032   ,138.7,139.1,144.4
XS GIS Cut Line= 3
2233234.00424314346590.5910022262232952.48282455346999.130539477
2232731.99671698347421.873460397
#Sta/Elev= 30
       0    2394       7 2393.25    55.7 2387.42   127.8  2372.4   143.4 2369.02
   209.4 2344.76   238.3 2345.84   278.9 2339.87   298.8 2341.72   338.6  2339.5
   410.4  2326.6   454.2 2322.69   523.8 2320.45   534.9 2318.44  566.572318.877
  586.792319.083   597.8 2320.39   634.8 2317.73   638.5 2318.12   645.9 2323.07
     657 2323.55   682.9 2320.38   697.7 2325.29   727.3 2325.16   753.2 2341.86
   793.9 2354.86   871.6 2386.96     916 2408.45   964.1 2435.25   972.9 2440.64
#Mann= 10 ,-1 , 0
       0      .1       0       7      .1       0   127.8     .06       0
   143.4      .1       0   410.4      .1       0  566.57    .045       0
  586.79    .055       0     657     .06       0   793.9      .1       0
   964.1      .1       0
#XS Ineff= 2 , 0
             508    2330     644            2330
Permanent Ineff=
       F       F
Bank Sta=566.57,586.79
XS Rating Curve= 0 ,0
Exp/Cntr=0.5,0.3

Type RM Length L Ch R = 1 ,21893   ,180.1,179.9,177.2
XS GIS Cut Line= 4
2233002.05982514 346619.584054472232817.33775364346968.195233896
2232728.44882381347123.7506970612232610.39328563347389.028709814
#Sta/Elev= 30
       0 2413.02    10.6 2407.35    63.7 2378.27    81.7 2365.86    89.7 2361.95
    97.1 2359.63   119.4 2358.71   135.1 2353.21   152.8 2344.62   170.9  2340.8
   253.1 2333.42   375.6 2324.44   416.8  2319.8   431.9 2318.44   439.5 2315.53
  454.492315.557   476.5 2314.42   492.4 2316.58   507.5 2317.27   518.8 2320.46
   552.8  2320.7   580.1 2323.94     597 2323.98   614.9 2321.62   622.1 2326.07
     658    2342   689.5 2354.71   821.2  2411.4     856 2428.33     864 2432.43
#Mann= 11 ,-1 , 0
       0      .1       0    10.6    .055       0    89.7      .1       0
   135.1     .06       0   253.1      .1       0   375.6    .055       0
   416.8      .1       0  454.49    .045       0   492.4     .06       0
   689.5      .1       0     856      .1       0
#XS Ineff= 2 , 0
                           589.5          2329.9
Permanent Ineff=
       F       F
Bank Sta=454.49,492.4
XS Rating Curve= 0 ,0
Exp/Cntr=0.5,0.3

Type RM Length L Ch R = 1 ,21713   ,315.5,327.1,339.2
XS GIS Cut Line= 3
2232918.72665846346605.6953027252232688.17101721346840.417602316
2232435.39330755 347314.02853173
#Sta/Elev= 30
       0 2431.03    23.9 2418.43     103  2380.7   133.4  2364.6   162.7 2342.02
   167.3 2339.44   190.3 2336.93   207.6 2326.65   213.3 2324.54   262.7 2319.95
   286.9 2320.15   391.7 2317.14   421.4 2315.89   451.2 2313.24   480.9 2313.97
  491.572311.864     509 2310.49     523 2311.15     533 2312.83   555.3 2313.39
   570.2 2319.64     578 2321.39   603.6 2321.88   618.5 2316.27   629.7 2318.54
   667.7 2338.47   690.2 2347.67   741.2 2360.28   786.5 2375.66   865.9 2400.68
#Mann= 4 ,-1 , 0
       0      .1       0  491.57    .045       0     523     .06       0
  593.18      .1       0
#XS Ineff= 2 , 0
                          594.23         2327.26
Permanent Ineff=
       F       F
Bank Sta=491.57,523
XS Rating Curve= 0 ,0
Exp/Cntr=0.3,0.1

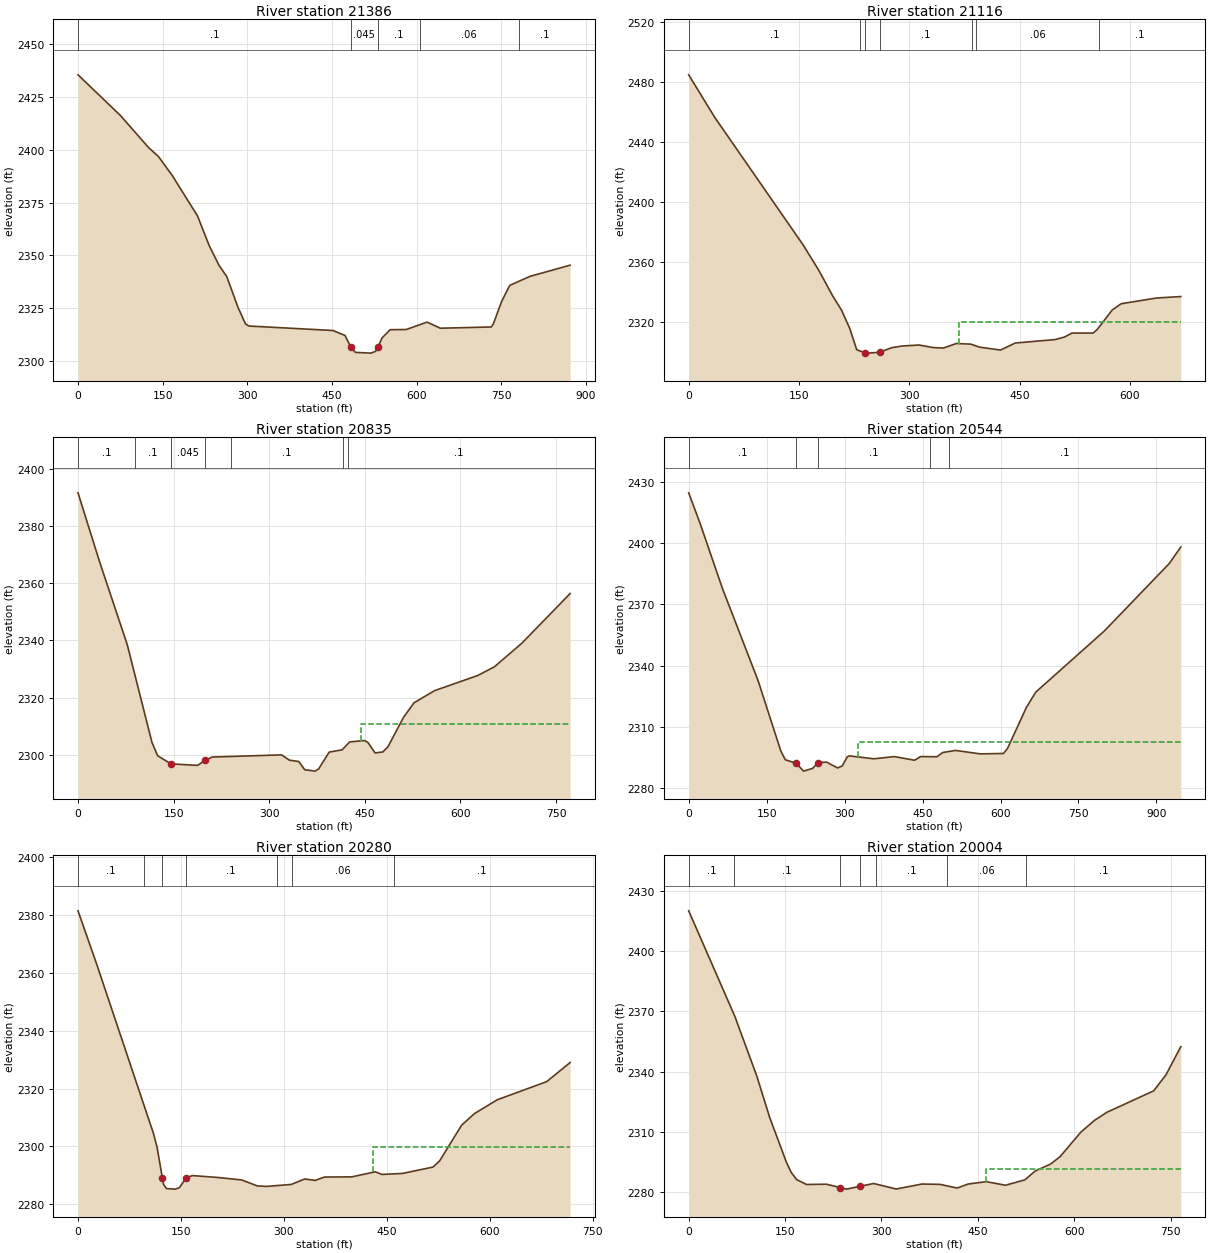
Type RM Length L Ch R = 1 ,21386   ,278.3,269.8,262.8
XS GIS Cut Line= 4
2232869.88686113346596.2832480672232467.10912339346731.005419567
2232289.33126372346814.3389143052232104.74797148 346984.61646089
#Sta/Elev= 30
       0 2435.57      75 2416.35   125.3 2401.04   142.6 2396.85   166.8 2387.95
   211.8 2368.72   232.6 2354.58   250.1 2345.22   263.7 2339.92   283.8 2325.21
   296.8 2317.57   302.6 2316.54   451.7 2314.41   473.2 2312.08   483.1 2306.77
   491.6 2304.05     519 2303.69   527.5 2304.53   531.5 2306.47   538.7 2310.84
   553.2 2314.79   581.7 2314.88   618.7 2318.39   642.1  2315.5   732.6 2316.08
   736.2 2317.61   750.7 2328.11   765.2 2335.79   800.8 2340.04   872.2 2345.37
#Mann= 5 ,-1 , 0
       0      .1       0   483.1    .045       0   531.5      .1       0
  605.28     .06       0   781.7      .1       0
Bank Sta=483.1,531.5
XS Rating Curve= 0 ,0
Exp/Cntr=0.3,0.1

Type RM Length L Ch R = 1 ,21116   ,277.1,281.9,288.3
XS GIS Cut Line= 2
2232377.06009088346344.5842763932231993.72653997346893.195383891
#Sta/Elev= 30
       0 2484.59    35.3 2456.32   155.5 2371.29   176.7 2354.48   195.5  2337.5
     208 2327.61   219.1 2315.44   228.5 2301.33  239.622299.251     244 2299.05
  259.832299.656   276.1 2302.66   289.8 2303.76   313.3 2304.47   332.1 2302.78
   346.3 2302.42   364.1 2305.47   383.8 2305.04   395.3 2303.06   424.1  2301.1
   444.2 2305.79   498.4  2308.1   511.2 2309.79   521.3 2312.44     550  2312.4
   555.7 2314.85   576.2  2327.9   588.2 2331.98   636.1 2335.79   669.3 2336.77
#Mann= 7 ,-1 , 0
       0      .1       0  233.44      .1       0  239.62    .045       0
  259.83      .1       0   385.4      .1       0  390.64     .06       0
   558.3      .1       0
#XS Ineff= 2 , 0
                          367.63         2319.72
Permanent Ineff=
       F       F
Bank Sta=239.62,259.83
XS Rating Curve= 0 ,0
Exp/Cntr=0.3,0.1

Type RM Length L Ch R = 1 ,20835   ,289.8,290.2,286.5
XS GIS Cut Line= 3
2232107.61541981346289.0286132252231927.06000663346486.250659734
2231628.44872722346893.195383891
#Sta/Elev= 30
       0  2391.7    33.4 2367.86    77.2 2338.56     116  2304.3   124.9 2299.61
   145.8 2296.76   187.6 2296.23   199.2 2297.98   210.8 2299.16   319.5 2299.91
   331.7 2298.06   346.4 2297.58   355.7 2294.71   371.9 2294.22   377.5 2294.98
   394.1 2300.89   414.4 2301.68   426.2 2304.45   449.6 2304.94   455.1 2304.19
   466.1  2300.6   478.2 2300.93   486.3 2302.76   510.7 2313.06   527.2 2318.16
   559.5 2322.42     627  2327.7   653.1 2330.73   696.1 2338.97   772.1 2356.41
#Mann= 7 ,-1 , 0
       0      .1       0   89.17      .1       0   145.8    .045       0
   199.2      .1       0  240.29      .1       0  416.23     .06       0
  423.17      .1       0
#XS Ineff= 2 , 0
                          443.69          2310.9
Permanent Ineff=
       F       F
Bank Sta=145.8,199.2
XS Rating Curve= 0 ,0
Exp/Cntr=0.3,0.1

Type RM Length L Ch R = 1 ,20544   ,264.1,264.7,264.8
XS GIS Cut Line= 3
2231925.67090181346083.4729219822231710.39311713346327.917643055
2231378.44889914346852.917577311
#Sta/Elev= 30
       0 2424.77      22 2409.71    65.1 2377.72   133.6 2332.55   177.3 2298.05
   185.9 2293.78   206.9 2292.06     221  2288.2   238.5 2289.55   248.7 2292.28
     265 2292.65   286.6 2289.76   295.4 2290.73   304.9 2295.19   309.1 2295.69
   356.3 2294.24   395.8 2295.34   434.6 2293.54   446.3 2295.35   477.6 2295.25
     489 2297.35   513.3 2298.37   560.8 2296.67   605.4 2296.85   613.2  2299.2
   649.9 2319.52   667.8 2326.97   799.5 2356.91   924.7 2390.08   946.9 2398.19
#Mann= 5 ,-1 , 0
       0      .1       0   206.9    .045       0   248.7      .1       0
  464.73     .06       0  501.13      .1       0
#XS Ineff= 2 , 0
                          325.41         2302.31
Permanent Ineff=
       F       F
Bank Sta=206.9,248.7
XS Rating Curve= 0 ,0
Exp/Cntr=0.3,0.1

Type RM Length L Ch R = 1 ,20280   ,271.7,275.8,279.5
XS GIS Cut Line= 2
2231679.83773205345966.8064886482231199.28226273346498.750962809
#Sta/Elev= 30
       0 2381.34      27 2363.07   110.1 2304.35   115.3 2299.58  122.912289.043
   124.5 2286.98   128.8 2285.47     142 2285.28   147.8  2285.8   157.1 2289.03
   166.4 2289.96   203.1 2289.32   238.4 2288.45   261.4 2286.38   274.7 2286.22
   310.8  2286.9   330.3 2288.79   345.2 2288.28   359.2 2289.45   398.9 2289.51
   433.1 2291.27   442.7 2290.35   472.3 2290.69   517.1 2292.89   526.7 2294.99
   558.9 2307.37   577.7 2311.38   610.7 2316.12   682.7 2322.37   716.9 2328.98
#Mann= 7 ,-1 , 0
       0      .1       0   96.55      .1       0  122.91    .045       0
   157.1      .1       0  289.16      .1       0  311.66     .06       0
  460.28      .1       0
#XS Ineff= 2 , 0
                           429.2         2299.75
Permanent Ineff=
       F       F
Bank Sta=122.91,157.1
XS Rating Curve= 0 ,0
Exp/Cntr=0.3,0.1

Type RM Length L Ch R = 1 ,20004   ,259.2,260.2,253.6
XS GIS Cut Line= 3
2231574.28216888345777.9174307292231296.50450923345952.917408809
 2230938.1709083346204.306341723
#Sta/Elev= 30
       0 2420.06      72 2367.41     106 2337.86   126.1 2317.23     152 2295.04
   159.4    2290     168 2286.35   183.5 2283.91   214.5 2284.04   235.6 2282.39
   245.5  2281.6   266.5 2282.99   287.9  2284.4   323.1 2281.65     363 2284.13
   391.1 2283.97   417.8 2282.14   435.1 2284.14   463.2 2285.31   493.2 2283.53
   523.3 2286.22   539.3 2290.59   563.4  2294.1     578 2297.72   610.2 2309.88
   631.5 2315.77     651 2319.84   723.7 2330.48   742.9 2338.45     766 2352.47
#Mann= 7 ,-1 , 0
       0      .1       0   70.25      .1       0   235.6    .045       0
   266.5      .1       0  291.84      .1       0  401.36     .06       0
  525.72      .1       0
#XS Ineff= 2 , 0
                          462.71         2291.66
Permanent Ineff=
       F       F
Bank Sta=235.6,266.5
XS Rating Curve= 0 ,0
Exp/Cntr=0.3,0.1

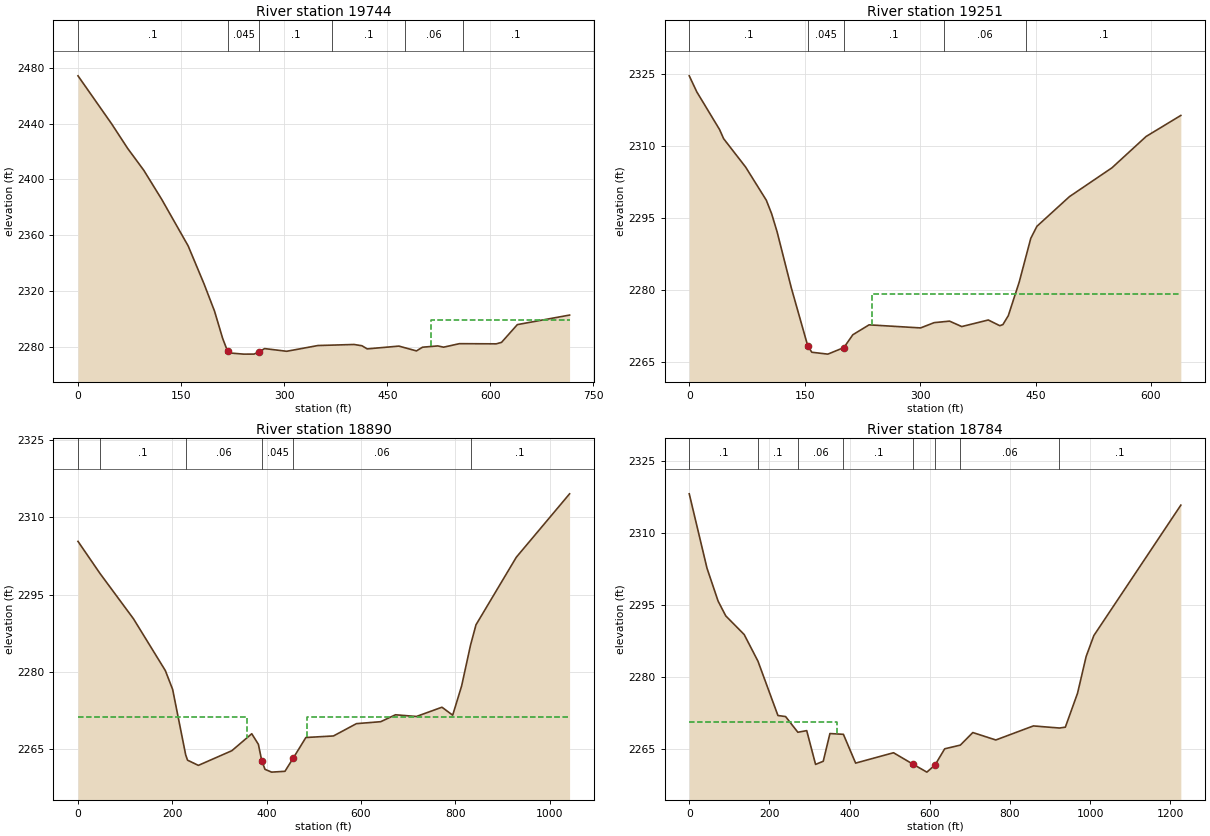
Type RM Length L Ch R = 1 ,19744   ,489.3,492.1,480.7
XS GIS Cut Line= 2
2231510.39318906345543.1951311382230897.89310172345912.639602229
#Sta/Elev= 30
       0 2474.11    49.2 2439.58    72.2 2422.24    95.8 2406.49   121.8 2385.77
   160.3 2352.43   183.3  2325.4   198.7 2305.72   210.5 2286.26   217.7 2277.03
   222.5 2275.78   240.8 2275.01   256.1 2275.03   263.8 2276.69   271.5 2278.97
   303.7 2277.05   349.1 2281.16   401.7 2281.91   413.2    2281   420.8 2278.75
   466.9 2280.76   492.5 2277.31   501.3 2279.96   523.6 2280.88     532 2279.98
     555 2282.49   608.6 2282.37   616.3 2283.43   639.3 2296.13   715.3 2302.95
#Mann= 6 ,-1 , 0
       0      .1       0   217.7    .045       0   263.8      .1       0
  369.08      .1       0  476.12     .06       0  559.95      .1       0
#XS Ineff= 2 , 0
                          514.32         2299.31
Permanent Ineff=
       F       F
Bank Sta=217.7,263.8
XS Rating Curve= 0 ,0
Exp/Cntr=0.3,0.1

Type RM Length L Ch R = 1 ,19251   ,399.5,361.2,329.5
XS GIS Cut Line= 3
2231193.72649956345177.9176464832230988.17113639345344.584307894
2230743.72674339 345627.91740264
#Sta/Elev= 30
       0  2324.7     9.8 2321.36    39.4 2313.51    44.7  2311.6    73.2 2305.71
   100.1  2298.8     107    2296   114.1 2292.24   132.7 2280.49   154.1 2268.39
   159.3 2267.12   180.1 2266.73   200.9 2268.09   212.6 2270.77   233.7 2272.83
   300.6 2272.19   318.3 2273.29   338.3  2273.6   354.1 2272.47   388.6 2273.84
   403.6 2272.65   407.6 2272.89   414.6 2274.74   428.8 2281.75   443.8 2290.85
   451.8 2293.36     494 2299.53   549.3 2305.54   593.7 2312.07   638.8 2316.45
#Mann= 5 ,-1 , 0
       0      .1       0   154.1    .045       0   200.9      .1       0
   331.3     .06       0  438.08      .1       0
#XS Ineff= 2 , 0
                          237.29         2279.17
Permanent Ineff=
       F       F
Bank Sta=154.1,200.9
XS Rating Curve= 0 ,0
Exp/Cntr=0.5,0.3

Type RM Length L Ch R = 1 ,18890   ,98.4,106.6,110.2
XS GIS Cut Line= 6
2230957.61542322344755.6953938162230734.46724747344900.693135306
2230831.68949397345150.3133709732230890.71726306345316.111923888
2230888.98137414345368.1951530582230749.22443581345611.250769317
#Sta/Elev= 30
       0 2305.35    46.6 2299.13   117.7 2290.32   185.3 2280.26   200.7 2276.62
   228.4 2263.91   232.3 2262.88   255.3 2261.87   326.3 2264.72   368.5 2268.01
   382.6 2265.95   389.6  2262.8   389.6 2262.79   396.6  2261.1   410.7 2260.56
   438.9 2260.72   456.5 2263.29   483.3 2267.28   541.7 2267.58   590.5 2269.97
     642 2270.35   673.3 2271.69   717.7 2271.36   771.9 2273.16   794.6 2271.61
   813.5 2277.27   832.4 2285.19     844 2289.15   929.6 2302.28  1042.5 2314.58
#Mann= 6 ,-1 , 0
       0      .1       0    46.6      .1       0   228.4     .06       0
   389.6    .045       0   456.5     .06       0   832.4      .1       0
#XS Ineff= 2 , 0
             359 2271.25   486.6         2271.25
Permanent Ineff=
       F       F
Bank Sta=389.6,456.5
XS Rating Curve= 0 ,0
Exp/Cntr=0.5,0.3

Type RM Length L Ch R = 1 ,18784   ,244.4,270.4,292.1
XS GIS Cut Line= 6
 2230844.7104653344484.8944262272230652.00218931344806.074886233
2230639.84932648344851.2139035612230717.97417022345080.868956059
 2230809.1199853345317.8481408952230732.73135856 345616.45909223
#Sta/Elev= 30
       0 2318.12    44.3 2302.61      72 2295.76    91.1 2292.68     137  2288.8
   171.4 2283.24   221.2 2271.92   240.3  2271.7   270.9 2268.43     293 2268.77
   315.1 2261.73   334.2 2262.38   350.9 2268.16   384.5    2268     415    2262
   509.5 2264.16   558.4 2261.76   592.7 2260.12   613.2 2261.62   637.2 2264.98
   676.2 2265.75   707.3 2268.37   764.7 2266.82   858.4 2269.75   923.5 2269.31
   938.1 2269.49   968.5 2276.55     990 2284.22  1009.2 2288.58  1226.2 2315.76
#Mann= 8 ,-1 , 0
       0      .1       0   171.4      .1       0   270.9     .06       0
   384.5      .1       0   558.4    .045       0   613.2      .1       0
   676.2     .06       0   923.5      .1       0
#XS Ineff= 2 , 0
          369.21 2270.53
Permanent Ineff=
       F       F
Bank Sta=558.4,613.2
XS Rating Curve= 0 ,0
Exp/Cntr=0.5,0.3