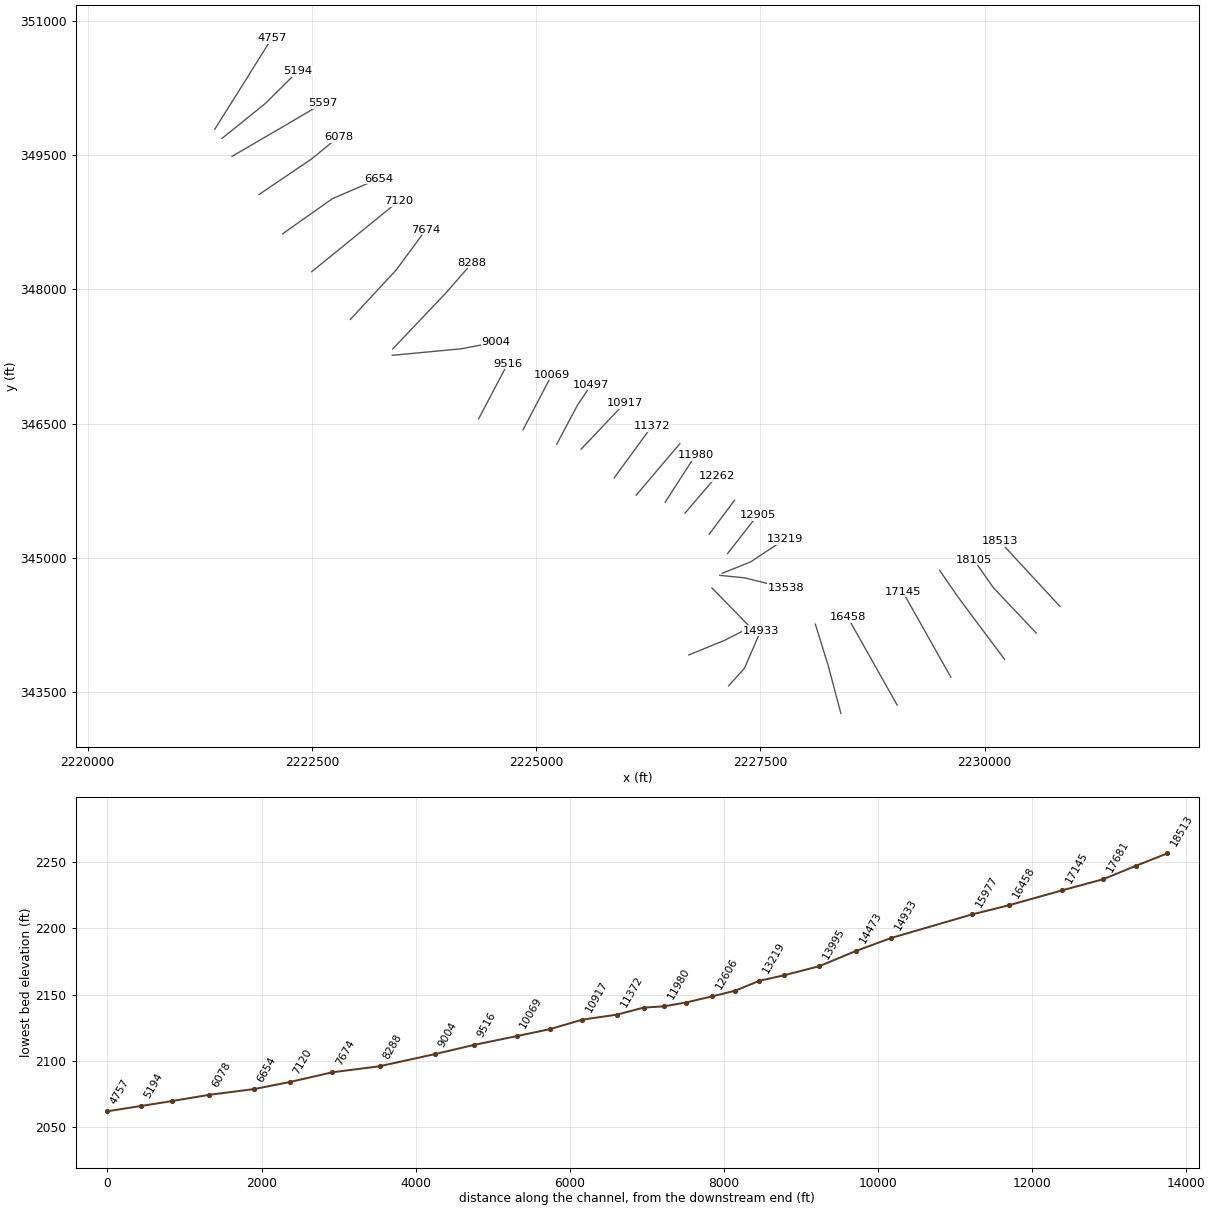
HEC-RAS study MEADOWCK1.prj: MEADOWCK1

--- MEADOWCK1.g01 (geometry) --- (continued)

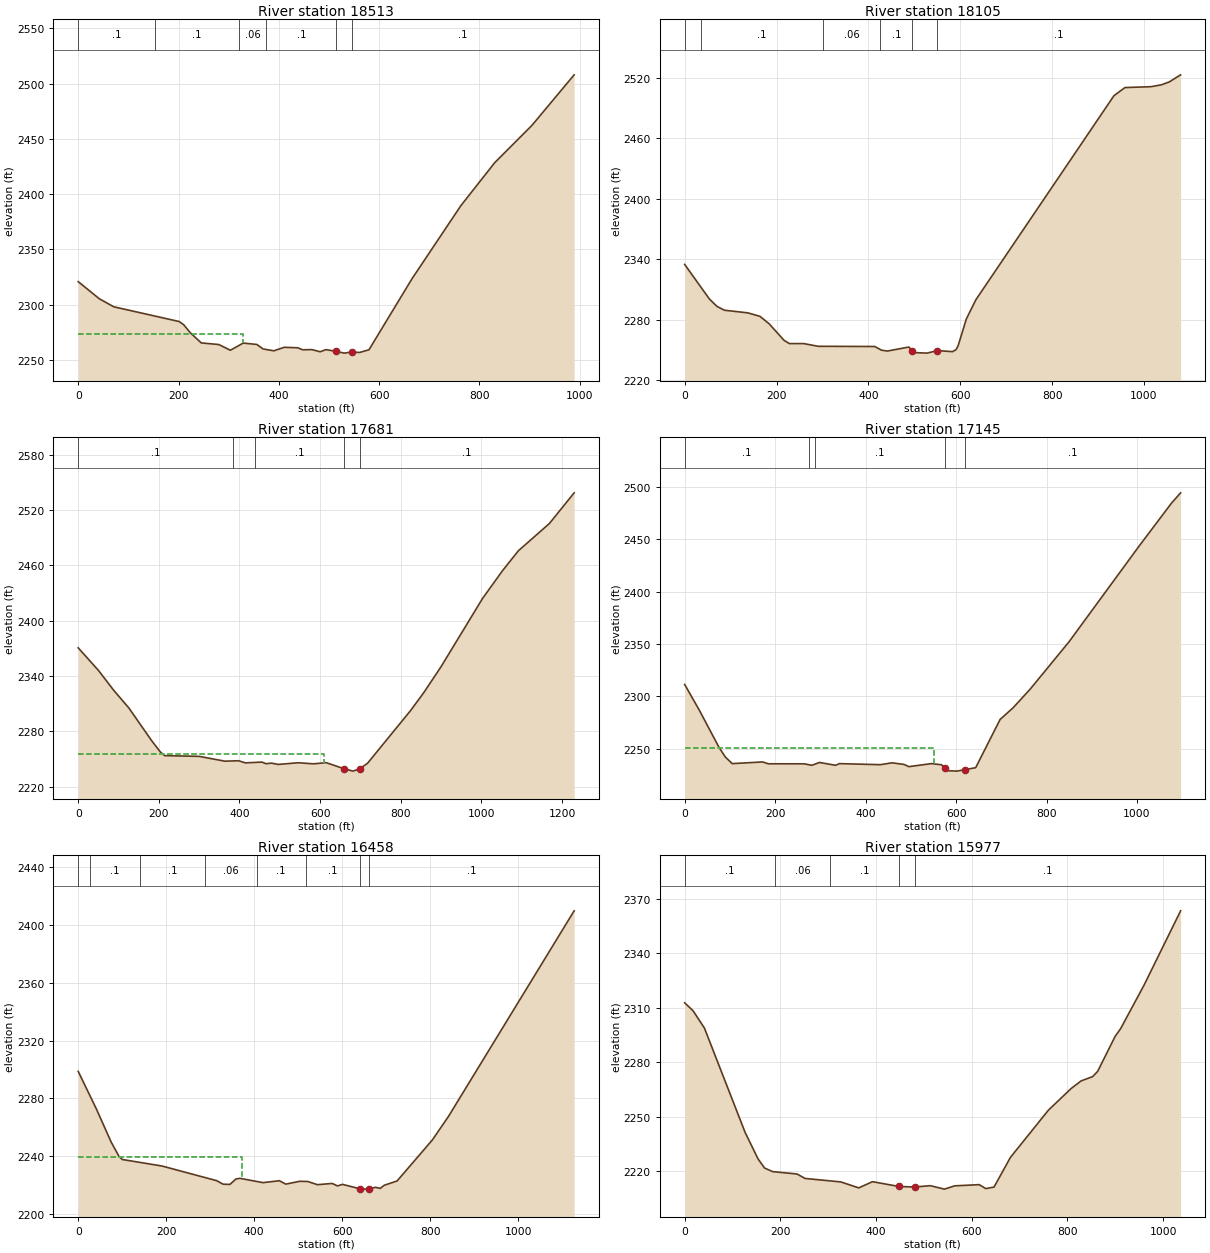
Type RM Length L Ch R = 1 ,18513   ,409.2,408.3,406.2
XS GIS Cut Line= 2
2230840.54380697344457.9847031382230169.71050297 345184.37367031
#Sta/Elev= 30
       0 2320.91      42  2305.4      71 2298.12   201.3  2284.8   210.6 2281.79
   223.3 2274.71   245.4 2265.44   280.2 2264.01   303.4 2258.83     329  2265.3
   356.3 2264.06   368.4 2260.04   375.4 2259.44   390.1 2258.33   410.9  2261.5
   438.1 2261.04   447.4 2259.23     466 2259.41   482.4 2257.45   493.8 2259.36
   514.7 2257.83   530.4 2256.22   544.9 2257.19   561.1 2256.83   579.7 2259.24
   665.6 2323.55   763.1 2389.72   830.7 2428.63   904.8 2462.31   988.8 2507.95
#Mann= 6 ,-1 , 0
       0      .1       0  152.94      .1       0  320.54     .06       0
   375.4      .1       0   514.7    .045       0   544.9      .1       0
#XS Ineff= 2 , 0
          329.36 2273.84
Permanent Ineff=
       F       F
Bank Sta=514.7,544.9
XS Rating Curve= 0 ,0
Exp/Cntr=0.3,0.1

Type RM Length L Ch R = 1 ,18105   ,427.3,423.5,416.7
XS GIS Cut Line= 3
2230576.65489906344159.3737518042230096.09942973344669.095829472
2229879.43254022344980.207083896
#Sta/Elev= 30
       0 2334.92      54 2300.49    70.3 2293.28    86.5 2289.46   137.6 2286.82
   163.8  2283.4     184 2275.95   216.4 2259.53   228.1 2256.32   259.4 2256.31
   290.7 2253.63   413.8 2253.44   428.5 2249.77   441.2 2248.91     488 2252.89
  495.782249.423   500.6 2247.39   527.5 2246.85   550.2 2249.36   583.2 2248.32
   590.8 2250.34   595.3 2254.15   613.3 2280.93   634.2 2300.04   934.6 2502.49
   958.5 2510.55    1015 2511.42  1037.9 2513.26  1055.2 2516.21  1079.7  2523.2
#Mann= 6 ,-1 , 0
       0      .1       0   35.59      .1       0  300.34     .06       0
  425.49      .1       0  495.78    .045       0   550.2      .1       0
Bank Sta=495.78,550.2
XS Rating Curve= 0 ,0
Exp/Cntr=0.3,0.1

Type RM Length L Ch R = 1 ,17681   ,538.7,536.4,534.3
XS GIS Cut Line= 3
2230222.48828456343866.3182355612229707.21044372344557.984831229
2229498.87719896 344860.76244089
#Sta/Elev= 30
       0 2370.55    50.5 2345.89    88.3 2324.33   125.8  2305.2     182 2269.91
   203.1 2257.92   214.2 2253.58   300.1 2252.79   364.1 2247.56   397.7 2248.05
   414.6 2245.73   455.6 2246.58   465.7 2244.85   479.4 2245.44   496.2 2244.03
   545.5 2245.87   583.7  2244.7   615.1 2245.95   658.6  2239.5   681.4 2236.78
   697.8 2239.26   717.4 2245.21   824.5 2302.58   857.3 2322.09   899.7 2349.93
  1002.8 2424.07  1051.8  2453.9  1091.6  2475.8  1168.7 2505.43    1230 2538.68
#Mann= 5 ,-1 , 0
       0      .1       0  383.47     .06       0  438.83      .1       0
   658.6    .045       0   697.8      .1       0
#XS Ineff= 2 , 0
          610.07 2255.84
Permanent Ineff=
       F       F
Bank Sta=658.6,697.8
XS Rating Curve= 0 ,0
Exp/Cntr=0.3,0.1

Type RM Length L Ch R = 1 ,17145   ,688.1,686.8,685.5
XS GIS Cut Line= 2
2229623.87694897343667.7070842242229086.37703972344623.262587816
#Sta/Elev= 30
       0  2311.3    33.1 2286.11    76.4 2250.73    89.9  2241.9     105 2235.56
   172.7 2237.15   184.8 2235.39   264.3 2235.36   281.2 2233.96   298.1 2236.65
   333.5 2233.96   342.1 2235.55   432.5 2234.54   458.8 2236.33   485.2 2234.74
   495.6 2232.66   545.4 2235.56     568 2234.44   575.5 2231.08   581.1 2228.78
   601.6 2228.37   620.7  2229.9   643.3 2231.64   697.3 2277.79   726.1    2289
   763.7 2306.76   849.8 2352.16  1003.9 2443.24  1076.3 2484.79  1096.4 2494.63
#Mann= 5 ,-1 , 0
       0      .1       0  274.62     .06       0  287.83      .1       0
   575.5    .045       0   620.7      .1       0
#XS Ineff= 2 , 0
          552.12 2250.13
Permanent Ineff=
       F       F
Bank Sta=575.5,620.7
XS Rating Curve= 0 ,0
Exp/Cntr=0.3,0.1

Type RM Length L Ch R = 1 ,16458   ,485.9,481.4,478.9
XS GIS Cut Line= 2
2229024.57138905343356.9429419792228472.48817563344339.582052812
#Sta/Elev= 30
       0 2298.65    41.3 2272.66    74.8  2249.8    92.6 2239.91   100.1  2237.7
   190.5 2233.18   314.6 2223.06   329.3 2220.62   344.7 2220.46   358.5 2224.19
   367.3 2224.68     420 2221.69   457.3 2223.01   471.7 2220.66     503  2222.6
   521.6  2222.5   543.7 2220.27   577.2 2221.14   589.3 2219.42   600.6 2220.49
  639.89 2217.47   653.3  2217.2   659.92217.349   675.9 2218.46   686.2  2217.7
   695.8  2219.9   724.7 2222.84   804.9 2251.24   841.5 2267.49  1127.1  2409.7
#Mann= 8 ,-1 , 0
       0      .1       0   27.29      .1       0  140.61      .1       0
  288.81     .06       0  406.15      .1       0  516.57      .1       0
  639.89    .045       0   659.9      .1       0
#XS Ineff= 2 , 0
          371.48 2239.57
Permanent Ineff=
       F       F
Bank Sta=639.89,659.9
XS Rating Curve= 0 ,0
Exp/Cntr=0.3,0.1

Type RM Length L Ch R = 1 ,15977   ,1053.4,1043.4,1034.1
XS GIS Cut Line= 3
 2228397.8354378 343263.193129482228257.21039097343794.443051234
2228113.11323822344259.720992059
#Sta/Elev= 30
       0  2312.7    17.6 2308.31    41.3  2298.8   126.2 2241.53   153.3 2226.91
   166.9 2221.87   183.9 2219.88   234.8 2218.58   251.8 2216.13   326.4 2214.22
   363.8 2210.94   392.5 2214.35  447.962211.718   481.2 2211.42   513.1 2212.16
   542.9 2210.26   564.2 2212.06   615.7 2212.72   629.4 2210.55   646.6 2211.39
   680.9 2227.71   759.9 2253.57   807.7 2265.57   828.6 2269.76   852.5  2272.1
   863.2 2274.99   899.7 2294.24   911.1 2298.44   960.1 2322.38  1036.6 2363.27
#Mann= 5 ,-1 , 0
       0      .1       0  189.44     .06       0  303.25      .1       0
  447.96    .045       0   481.2      .1       0
Bank Sta=447.96,481.2
XS Rating Curve= 0 ,0
Exp/Cntr=0.3,0.1

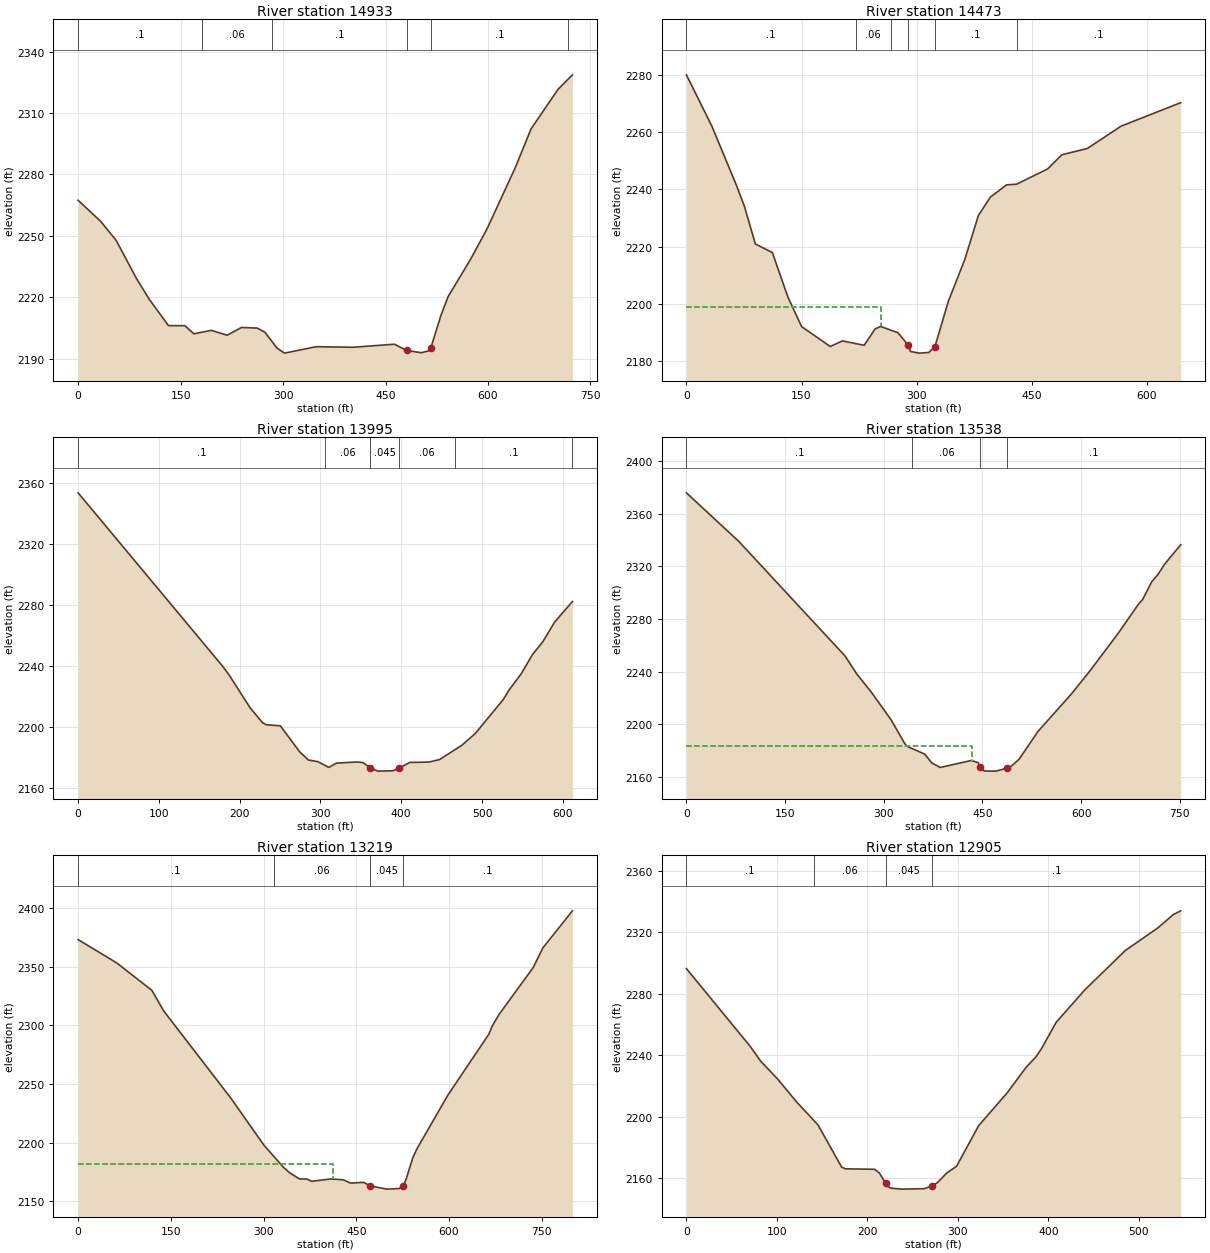
Type RM Length L Ch R = 1 ,14933   ,470.9,460.1,444.1
XS GIS Cut Line= 3
2227146.09942421343570.4848377262227323.18273146343768.401436642
2227505.47436164344188.540360138
#Sta/Elev= 30
       0 2267.38    33.1 2257.05    55.6 2247.83    85.8  2228.9   104.3 2218.91
   132.2 2206.12   156.4 2206.07   169.4 2202.11     195 2203.79   218.2 2201.41
   239.1 2205.21   262.3 2204.89   273.4  2202.9   291.3 2195.09     302 2192.66
   348.5  2195.8   402.2 2195.52     463 2197.02   480.9 2193.99   502.3 2192.85
     513 2193.75   516.3 2195.17   530.9  2210.9   541.7 2220.35     574 2238.22
   598.7 2253.46   639.9  2283.3   663.2 2302.37   702.6 2321.62   723.6 2328.71
#Mann= 6 ,-1 , 0
       0      .1       0   181.1     .06       0  284.28      .1       0
   480.9    .045       0   516.3      .1       0  717.15      .1       0
Bank Sta=480.9,516.3
XS Rating Curve= 0 ,0
Exp/Cntr=0.3,0.1

Type RM Length L Ch R = 1 ,14473   ,496.8,478,455.2
XS GIS Cut Line= 3
2226703.39099206343915.9710233962227097.48830096344077.429361895
2227291.93246588344176.387497306
#Sta/Elev= 30
       0 2279.91    33.1 2262.04      65  2241.5    75.6 2234.05    89.8 2220.92
     112 2217.91   132.3 2202.36   150.1 2192.09   187.5 2185.15   203.3 2187.11
   231.6 2185.57   245.8 2191.24   252.9 2192.16   275.5 2189.98     289 2185.68
   291.9 2183.42   303.2 2182.84   315.8 2183.07   323.8 2185.08   341.5 2201.04
   362.8 2215.53   380.5 2230.88   396.2 2237.28   417.3 2241.55   430.3 2241.77
   470.8 2247.11   489.2 2252.04   522.4 2254.21   566.5 2262.02   644.1 2270.19
#Mann= 6 ,-1 , 0
       0      .1       0  220.51     .06       0  266.06    .055       0
     289    .045       0   323.8      .1       0  431.24      .1       0
#XS Ineff= 2 , 0
          253.14 2198.84
Permanent Ineff=
       F       F
Bank Sta=289,323.8
XS Rating Curve= 0 ,0
Exp/Cntr=0.3,0.1

Type RM Length L Ch R = 1 ,13995   ,446.9,457.6,469.3
XS GIS Cut Line= 2
2226960.68247221344664.5820589812227387.07138322344225.693172976
#Sta/Elev= 30
       0 2353.79   178.5 2240.36   187.4 2233.98   213.1 2212.72   228.5 2203.02
   233.1 2201.74   250.3 2201.05   274.3 2183.95   285.1 2178.63   296.7 2177.57
   310.3  2173.8     320 2176.61   345.4 2177.34   352.7 2176.95   361.6 2173.45
   370.9 2171.34   389.5 2171.58   397.8 2173.29   410.3 2177.02   434.4 2177.28
   447.5 2178.95   475.1 2188.32   491.6 2195.98   526.4 2218.34   533.3 2224.38
   548.7  2235.3   562.4  2247.7   575.1 2256.05   589.9 2269.06   611.9 2282.54
#Mann= 6 ,-1 , 0
       0      .1       0  305.07     .06       0   361.6    .045       0
   397.8     .06       0  466.16      .1       0  611.53      .1       0
Bank Sta=361.6,397.8
XS Rating Curve= 0 ,0
Exp/Cntr=0.3,0.1

Type RM Length L Ch R = 1 ,13538   ,296.6,319.1,337
XS GIS Cut Line= 3
2227048.18262531344804.8596655582227324.57150821344777.081833974
2227784.29368588344663.192954138
#Sta/Elev= 30
       0  2375.9    79.9 2338.88   241.5 2251.77   258.5 2238.64   281.1 2224.49
   311.5 2203.21   331.8 2185.52   335.3 2183.35   362.2 2177.44   373.2 2170.67
   385.9 2167.29   433.2 2172.59   443.4 2170.95   446.7  2167.7   450.1 2165.28
   453.5 2164.59   470.4  2164.5   487.8  2166.8   494.1 2168.29   505.8 2173.59
   534.6 2194.72   585.3 2223.17   612.4 2239.99   656.3 2269.11   686.7 2290.99
   693.5 2294.81     707 2308.07   717.3 2314.22   727.3 2321.96   751.4 2336.44
#Mann= 4 ,-1 , 0
       0      .1       0  343.61     .06       0   446.7    .045       0
   487.8      .1       0
#XS Ineff= 2 , 0
          434.18 2183.92
Permanent Ineff=
       F       F
Bank Sta=446.7,487.8
XS Rating Curve= 0 ,0
Exp/Cntr=0.3,0.1

Type RM Length L Ch R = 1 ,13219   ,302.5,313.2,319.3
XS GIS Cut Line= 3
2227075.96045689344828.4708388152227391.23804155344954.859693646
2227774.57159247345209.026508138
#Sta/Elev= 30
       0 2373.02    62.5 2353.14   119.4 2329.71   138.4 2312.25   246.6 2238.24
   300.5 2197.91   331.4  2179.4   342.3 2174.26   358.1 2169.08   369.9 2168.97
   378.1 2167.06   408.9 2169.05   428.9 2168.32   440.7 2165.51   461.7 2166.16
   472.8 2163.07   499.8 2160.38   519.4 2160.86   524.8 2163.19   527.3  2164.6
   531.3 2169.95   541.4 2187.15   548.5 2195.11   598.2 2240.51   664.5 2292.47
   669.5 2298.97   680.8 2309.14     736 2349.05   751.7 2365.84   799.6 2397.53
#Mann= 4 ,-1 , 0
       0      .1       0  317.11     .06       0   472.8    .045       0
   524.8      .1       0
#XS Ineff= 2 , 0
          412.45 2182.04
Permanent Ineff=
       F       F
Bank Sta=472.8,524.8
XS Rating Curve= 0 ,0
Exp/Cntr=0.3,0.1

Type RM Length L Ch R = 1 ,12905   ,299.5,299.8,300.6
XS GIS Cut Line= 2
2227134.29367356345047.9152818172227470.40487798345478.470851138
#Sta/Elev= 30
       0 2296.25    70.6 2245.63    82.2    2236   100.7 2224.58   121.5 2209.77
   145.4 2194.67   171.5 2167.25   175.6 2166.12   207.9 2165.81   213.2 2163.43
   220.2 2156.73   222.5 2154.64   225.6  2153.6   238.1 2152.92     263 2153.21
   271.8 2155.08   277.2 2157.04   287.9  2163.5   298.5 2167.76     323 2194.24
   354.6  2215.6   375.4 2232.11   386.1 2238.77   392.1 2243.99   408.7 2261.43
   440.4 2282.51   485.1 2308.08   521.1 2322.77     538 2331.36   546.2  2333.8
#Mann= 4 ,-1 , 0
       0      .1       0  140.79     .06       0   220.2    .045       0
   271.8      .1       0
Bank Sta=220.2,271.8
XS Rating Curve= 0 ,0
Exp/Cntr=0.3,0.1

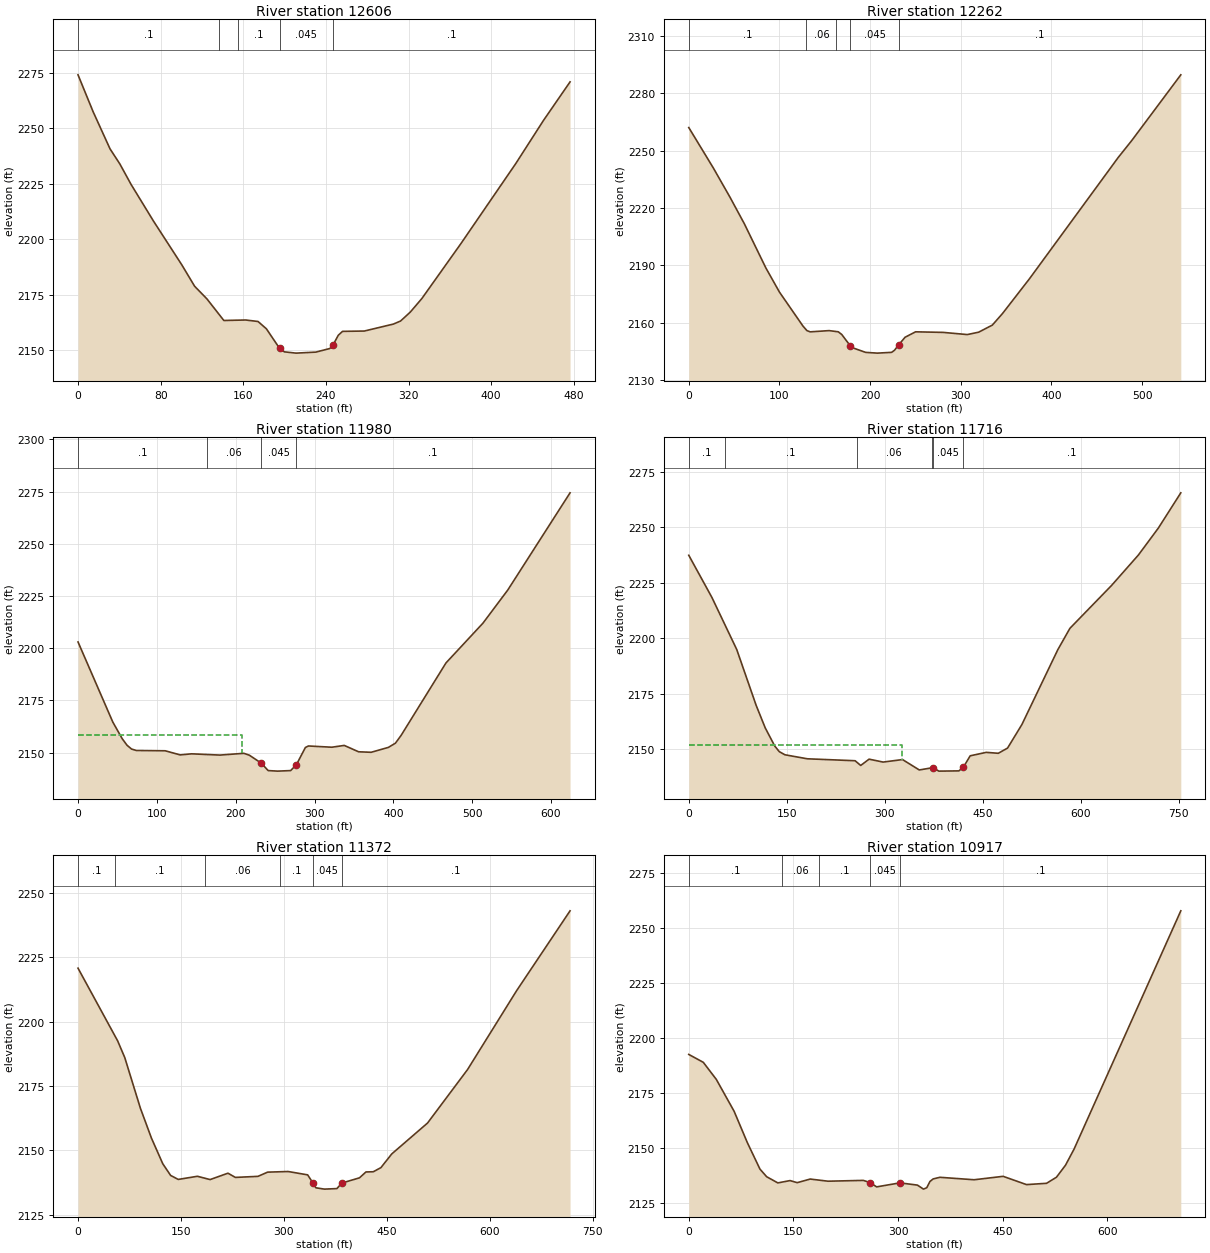
Type RM Length L Ch R = 1 ,12606   ,345.2,343.5,341.7
XS GIS Cut Line= 2
2226928.73831038345263.1930664782227213.46050997345645.137512565
#Sta/Elev= 30
       0 2273.99    14.7 2257.29      31 2240.64    40.4 2233.93    51.5 2224.53
    73.2 2208.02   100.6 2188.32   112.9 2178.76   124.8 2173.08   141.2 2163.34
   162.3 2163.56   174.3 2162.89   182.4 2159.59   195.1 2150.82   199.8 2149.22
   211.1 2148.64   230.3  2149.1   243.8 2150.72   246.7 2152.13     252 2156.69
   256.1 2158.44   277.2 2158.59   305.4 2161.73   312.3  2163.1   321.7 2167.12
   332.9 2173.22   370.7 2197.95   423.9 2234.06   450.7 2253.47   476.4 2270.81
#Mann= 5 ,-1 , 0
       0      .1       0  136.04     .06       0  154.86      .1       0
   195.1    .045       0   246.7      .1       0
Bank Sta=195.1,246.7
XS Rating Curve= 0 ,0
Exp/Cntr=0.3,0.1

Type RM Length L Ch R = 1 ,12262   ,278.8,281.7,285
XS GIS Cut Line= 2
2226660.68274413345500.693247646 2227013.4602538345913.193078816
#Sta/Elev= 30
       0 2262.13      27 2241.03    45.5 2225.63    61.3 2211.75      85 2188.65
   100.1 2175.91     126 2158.15   130.3 2155.81   133.9 2155.13   154.8 2155.78
   164.9 2155.16   168.8 2153.73   178.1 2147.86   182.1 2146.57   195.1 2144.38
     208 2143.99   223.8  2144.4     227 2145.52   231.6 2148.34   238.6  2152.3
   250.2 2155.15   280.5 2154.85   307.3 2153.71   319.8 2154.96   334.9 2158.68
   346.2 2164.78   375.9 2182.97   473.6 2246.36   488.7 2255.34   542.8 2289.74
#Mann= 5 ,-1 , 0
       0      .1       0  129.73     .06       0  162.77      .1       0
   178.1    .045       0   231.6      .1       0
Bank Sta=178.1,231.6
XS Rating Curve= 0 ,0
Exp/Cntr=0.3,0.1

Type RM Length L Ch R = 1 ,11980   ,267.2,264.4,261.3
XS GIS Cut Line= 2
 2226439.8491963345622.9154441512226777.34917746346147.915378392
#Sta/Elev= 30
       0 2203.02    44.1 2164.68      56 2156.72    62.2 2153.54    67.9 2151.74
    73.9 2151.05   110.6  2150.9   129.6 2148.93   144.1 2149.44   179.9 2148.84
   210.4 2149.69   217.4 2148.77   232.4    2145   241.2 2141.42   253.1 2141.16
   269.7 2141.42     277 2144.24   288.4 2152.48   292.3  2153.2   321.9 2152.61
   337.7 2153.47   355.9 2150.42   371.8 2150.18   393.7 2152.53   402.6 2154.55
   409.8 2158.27   466.7 2192.96   513.6 2212.01   545.1 2227.88   624.1 2274.43
#Mann= 4 ,-1 , 0
       0      .1       0   163.2     .06       0   232.4    .045       0
     277      .1       0
#XS Ineff= 2 , 0
          208.38 2158.64
Permanent Ineff=
       F       F
Bank Sta=232.4,277
XS Rating Curve= 0 ,0
Exp/Cntr=0.3,0.1

Type RM Length L Ch R = 1 ,11716   ,341.4,343.6,345
XS GIS Cut Line= 2
2226116.23829497345700.6931757332226602.34919938346275.693009973
#Sta/Elev= 30
       0 2237.48    35.4 2218.48    73.4 2195.01   103.1 2169.85     117 2159.69
   131.6 2151.48   138.5 2148.98   147.1 2147.57   181.4 2145.76   254.5 2144.88
   263.1 2142.76   275.9 2145.59   297.4 2144.28   327.1 2145.41   352.7 2140.73
   373.7 2141.77   382.6  2140.2   413.3 2140.31   420.3 2142.01   430.6  2147.1
   455.2 2148.66   473.6 2148.24   487.8 2150.59   509.7 2161.18   564.6 2194.87
   583.2 2204.55   646.9 2223.87     688 2237.59   718.5 2249.72   752.9 2265.62
#Mann= 6 ,-1 , 0
       0      .1       0   55.52      .1       0  257.25     .06       0
  371.46      .1       0   373.7    .045       0   420.3      .1       0
#XS Ineff= 2 , 0
          326.43 2151.96
Permanent Ineff=
       F       F
Bank Sta=373.7,420.3
XS Rating Curve= 0 ,0
Exp/Cntr=0.3,0.1

Type RM Length L Ch R = 1 ,11372   ,456.9,454.9,451.5
XS GIS Cut Line= 2
2225870.40479714345893.748563901 2226292.6270498346472.915384561
#Sta/Elev= 30
       0 2220.75    57.8 2192.48    68.1 2186.02    90.9 2166.32     107 2154.71
   123.5 2144.76   134.9 2140.24     146 2138.69   173.9 2139.91   192.4 2138.63
   218.4 2141.11   229.2 2139.47   262.1 2139.88   276.2 2141.52   306.1 2141.76
   334.5 2140.46   341.9 2137.41   346.5 2135.44   358.9 2134.92   377.1 2135.13
   384.2 2137.26     410 2139.31   419.4 2141.59   430.1 2141.67   441.2 2143.27
     457  2148.6   509.1 2160.59   567.4 2181.37     639 2212.07   716.7 2243.03
#Mann= 6 ,-1 , 0
       0      .1       0   53.48      .1       0  184.73     .06       0
  294.42      .1       0   341.9    .045       0   384.2      .1       0
Bank Sta=341.9,384.2
XS Rating Curve= 0 ,0
Exp/Cntr=0.3,0.1

Type RM Length L Ch R = 1 ,10917   ,415.4,420.1,418.2
XS GIS Cut Line= 2
2225502.34943089346214.5819117282225987.07155855346727.081870973
#Sta/Elev= 30
       0 2192.48    20.8 2188.89    39.5  2181.1      65 2166.59      84 2152.27
   102.1  2140.2   111.7 2136.74   127.7 2133.94   145.2 2134.99   155.5 2134.05
   174.1 2135.69   199.6 2134.71   250.2 2135.08   260.1 2134.07   269.3 2132.12
   302.7 2133.96   327.8 2132.93   336.5  2131.1   341.2 2131.75   345.8  2134.6
   350.4 2135.75     360 2136.49   409.1 2135.37   450.7 2136.93   484.2 2133.16
   512.9 2133.75   527.1 2136.52   540.1    2142   552.4 2149.37   705.4 2257.92
#Mann= 5 ,-1 , 0
       0      .1       0  133.99     .06       0  186.72      .1       0
   260.1    .045       0   302.7      .1       0
Bank Sta=260.1,302.7
XS Rating Curve= 0 ,0
Exp/Cntr=0.3,0.1

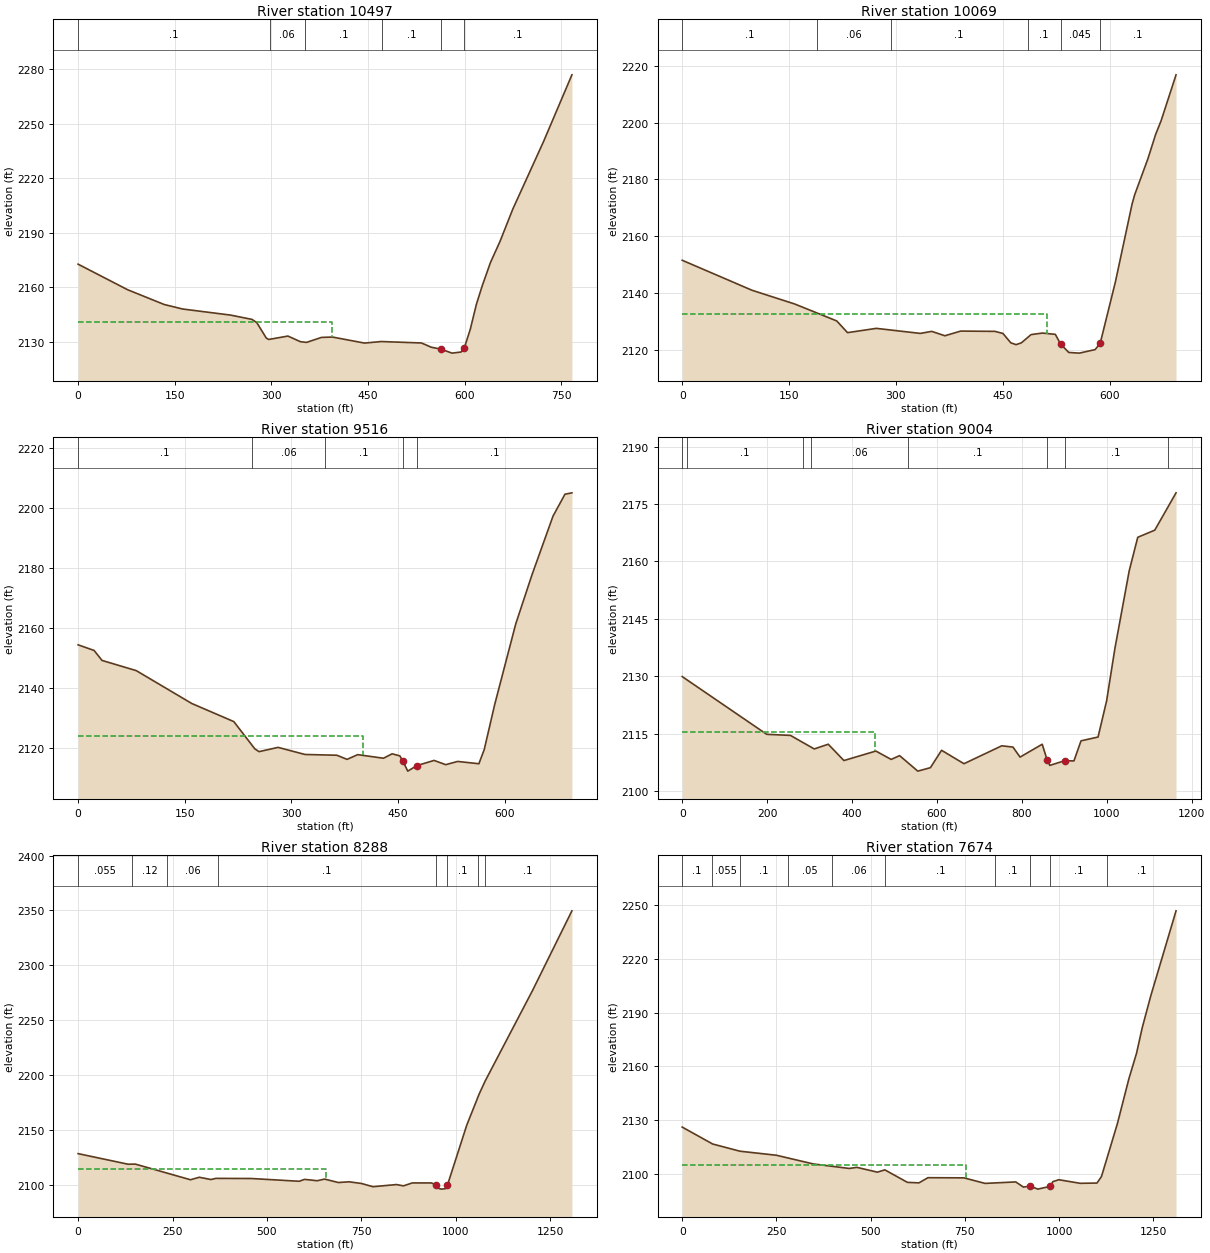
Type RM Length L Ch R = 1 ,10497   ,427.2,428,427.5
XS GIS Cut Line= 3
2225230.12720631346270.1375748962225460.68251947346704.859802559
2225613.46042913 346932.63756223
#Sta/Elev= 30
       0  2172.8    76.7 2158.78   133.6 2150.65   162.2 2148.17   236.4 2144.84
   269.9 2142.46   277.3 2140.69   292.1 2132.18   295.9 2131.44   325.6 2133.32
   344.7 2130.25   354.4 2129.82   377.6 2132.57   394.8 2132.77   444.4 2129.46
   470.4 2130.31   532.9 2129.51     548 2127.19   563.4  2126.1   580.2 2123.94
   594.4 2124.55   599.4 2126.89   608.6 2137.06     618 2150.67     627 2160.78
   639.9 2173.72   654.7 2185.27   674.4 2202.91   722.4 2240.25   766.3 2276.79
#Mann= 6 ,-1 , 0
       0      .1       0  297.23     .06       0  351.52      .1       0
  471.68      .1       0   563.4    .045       0   599.4      .1       0
#XS Ineff= 2 , 0
          394.34  2140.9
Permanent Ineff=
       F       F
Bank Sta=563.4,599.4
XS Rating Curve= 0 ,0
Exp/Cntr=0.3,0.1

Type RM Length L Ch R = 1 ,10069   ,540.9,553.1,558.4
XS GIS Cut Line= 2
2224854.54823305346431.0171743932225175.72902113  347045.6005909
#Sta/Elev= 30
       0 2151.48    98.1  2140.9   157.8 2136.08     217 2130.09   232.1 2125.97
   272.6 2127.48   334.3  2125.7   350.3 2126.42   368.8 2124.87     391 2126.52
   439.1 2126.42   450.3 2125.69   461.4 2122.38   468.8 2121.74   476.2 2122.38
   489.9 2125.29   505.8 2125.82   523.9 2125.37   531.2 2121.98   542.8 2118.98
   557.6 2118.75   579.8    2120   586.9 2122.22   608.2  2143.8   631.6 2171.23
   635.3 2174.56   653.9 2187.27   664.8  2195.9   672.4 2200.65   693.4 2216.85
#Mann= 6 ,-1 , 0
       0      .1       0  189.75     .06       0  292.73      .1       0
  485.06      .1       0   531.2    .045       0   586.9      .1       0
#XS Ineff= 2 , 0
          512.22 2132.56
Permanent Ineff=
       F       F
Bank Sta=531.2,586.9
XS Rating Curve= 0 ,0
Exp/Cntr=0.3,0.1

Type RM Length L Ch R = 1 ,9516    ,526.1,512.3,497.3
XS GIS Cut Line= 2
2224359.75657173346554.2810354832224682.67324872347168.864451975
#Sta/Elev= 30
       0 2154.35    22.5 2152.47    33.6 2149.14    81.8 2145.72   159.9 2134.73
   218.9 2128.69   248.5 2119.57   254.4 2118.64   281.2 2120.07   318.9  2117.7
   363.8 2117.44   378.2 2116.06   393.1 2117.64   429.4 2116.44   441.5 2117.92
   452.4 2117.22  456.272115.613   463.5 2112.13  476.272113.974   500.5 2115.71
   516.8 2114.29   533.7 2115.37   563.5  2114.6     571 2119.32   585.8 2134.47
   615.4 2161.41   638.3 2177.85   667.7 2197.36   684.5 2204.69   694.3 2205.16
#Mann= 5 ,-1 , 0
       0      .1       0  244.67     .06       0  347.72      .1       0
  456.27    .045       0  476.27      .1       0
#XS Ineff= 2 , 0
          400.11 2123.82
Permanent Ineff=
       F       F
Bank Sta=456.27,476.27
XS Rating Curve= 0 ,0
Exp/Cntr=0.3,0.1

Type RM Length L Ch R = 1 ,9004    ,704.8,716.1,726.1
XS GIS Cut Line= 3
2223396.21486364347262.6142644732224165.31240681347335.531113401
2224548.99274181 347408.44763422
#Sta/Elev= 30
       0 2129.88   198.9 2114.79   254.9  2114.5     311 2110.96   343.9  2112.2
   380.8 2107.93   456.1 2110.41   492.1 2108.22     512 2109.21   554.8 2105.16
   584.5 2106.06   610.8 2110.61   663.6  2107.1   752.6 2111.78     779 2111.45
   795.7 2108.83   847.9 2112.19   859.2 2108.19   859.2 2108.16   865.8 2106.66
   900.4 2107.87   922.6 2107.83   939.3 2113.08   979.4 2114.08   999.5  2123.5
  1019.1 2137.25  1052.8 2157.55  1072.9 2166.31    1113 2168.18  1163.1 2177.94
#Mann= 8 ,-1 , 0
       0    .055       0   12.36      .1       0  283.68     .12       0
  303.99     .06       0  531.58      .1       0   859.2    .045       0
   900.4      .1       0 1143.06      .1       0
#XS Ineff= 2 , 0
          454.33 2115.38
Permanent Ineff=
       F       F
Bank Sta=859.2,900.4
XS Rating Curve= 0 ,0
Exp/Cntr=0.3,0.1

Type RM Length L Ch R = 1 ,8288    ,612.2,614,613.7
XS GIS Cut Line= 3
2223401.42351463347333.7948963942224003.85406831347969.211604565
2224286.84005089348295.600387484
#Sta/Elev= 30
       0 2128.41   132.4 2118.75   151.5 2118.87   297.6  2104.6   320.8 2106.87
   351.8 2104.81   364.9 2105.86   458.7 2105.74   585.3 2103.22   599.7 2104.95
   633.1 2103.71   652.7 2105.21   689.3 2102.08   717.6 2102.74   750.1 2101.21
   780.9 2098.27   842.9 2100.22   861.5 2099.04   884.7 2101.69   935.9 2101.69
   946.5 2100.01   952.8 2096.96   961.5 2096.06   973.1 2096.47   977.8 2099.49
  1028.9 2154.12  1061.6  2182.4  1077.8 2194.51  1203.4  2277.1  1307.6 2349.64
#Mann= 8 ,-1 , 0
       0    .055       0  143.23     .12       0  235.51     .06       0
  370.53      .1       0   946.5    .045       0   977.8      .1       0
 1059.57      .1       0 1076.25      .1       0
#XS Ineff= 2 , 0
          657.61 2114.45
Permanent Ineff=
       F       F
Bank Sta=946.5,977.8
XS Rating Curve= 0 ,0
Exp/Cntr=0.3,0.1

Type RM Length L Ch R = 1 ,7674    ,557.9,554.2,550.2
XS GIS Cut Line= 3
2222929.20103389347663.6561133122223441.35388097348217.475543723
2223771.21509789348665.392298818
#Sta/Elev= 30
       0 2126.12    80.7 2116.69   153.2 2112.67   249.9 2110.41   348.2 2105.55
   443.1 2103.05   463.5 2103.66     518 2100.98   537.7 2102.26   597.8 2095.28
   628.3    2095   652.1 2097.89   747.6  2097.8   803.7 2094.71   885.2 2095.53
   905.6 2092.65   923.6 2093.26   943.7 2091.51   976.6 2093.06   983.6 2095.67
   999.3 2096.76  1056.4 2094.75  1100.7  2094.9  1112.7 2098.55  1154.9 2128.01
  1185.4 2153.05  1205.8 2167.37  1220.6 2181.37  1243.7 2199.48  1310.6 2246.79
#Mann= 10 ,-1 , 0
       0      .1       0   78.96    .055       0  153.79      .1       0
  280.82     .05       0  398.33     .06       0  539.24      .1       0
  831.21      .1       0   923.6    .045       0   976.6      .1       0
 1126.34      .1       0
#XS Ineff= 2 , 0
          753.48  2105.1
Permanent Ineff=
       F       F
Bank Sta=923.6,976.6
XS Rating Curve= 0 ,0
Exp/Cntr=0.3,0.1

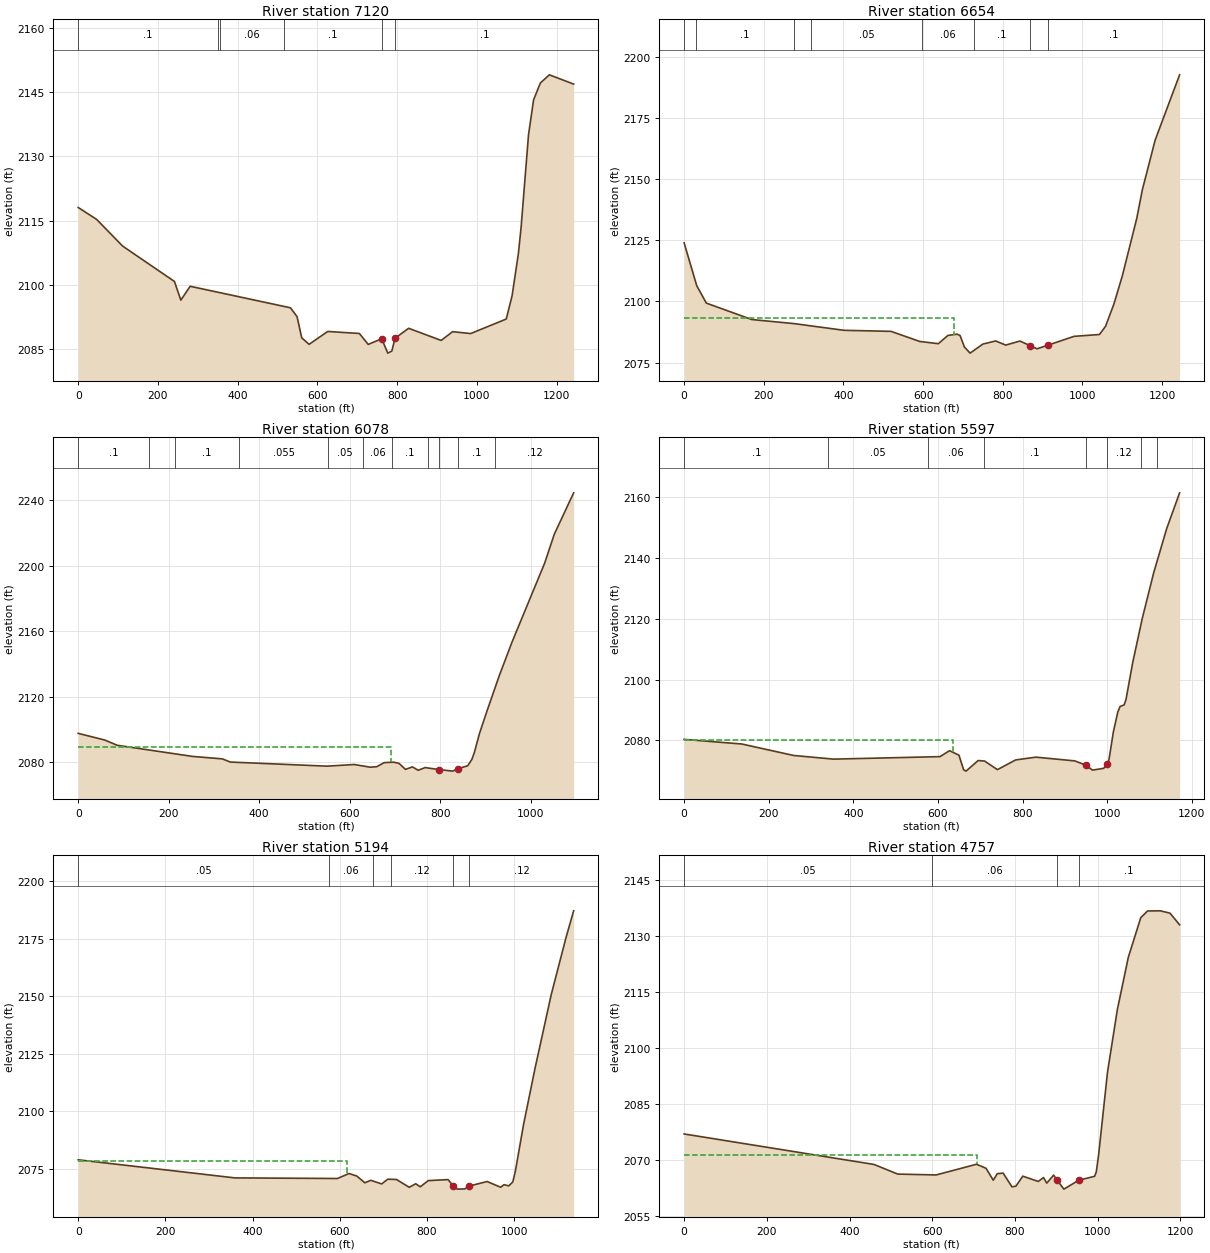
Type RM Length L Ch R = 1 ,7120    ,469.1,465.4,460.2
XS GIS Cut Line= 2
2222498.64546455348196.6422520582223462.18717264348981.364435896
#Sta/Elev= 30
       0 2118.09    46.3 2115.31   111.5 2109.09   241.4 2100.85   257.5 2096.49
   280.8 2099.72   532.4 2094.71     549 2092.64   560.6 2087.72   579.1 2086.19
   625.9 2089.19   705.2 2088.72   727.5 2086.17   761.3 2087.49   776.5 2084.14
   786.7 2084.62  794.642087.595   828.8 2089.93   910.4  2087.1   939.1 2089.14
   984.4  2088.7  1073.7 2092.09  1088.3 2097.51  1104.1 2107.37    1111 2113.57
  1129.5 2135.03  1142.2 2143.16  1159.1 2147.09  1181.8 2149.01  1242.7 2146.85
#Mann= 6 ,-1 , 0
       0      .1       0  350.11     .05       0  355.44     .06       0
  516.48      .1       0   761.3    .045       0  794.64      .1       0
Bank Sta=761.3,794.64
XS Rating Curve= 0 ,0
Exp/Cntr=0.3,0.1

Type RM Length L Ch R = 1 ,6654    ,567.8,576,579.6
XS GIS Cut Line= 3
2222173.99289864348620.2532814742222729.54821797349012.614373401
2223246.90938798349236.572586894
#Sta/Elev= 30
       0 2123.97    31.7  2106.4    55.8 2099.31   170.1 2092.58   276.7 2090.91
   401.2 2088.18   519.5 2087.75   591.4 2083.62   638.2  2082.7   662.3 2086.09
   685.7  2086.6   692.9 2086.02   703.6 2081.36   717.9 2078.84   750.1 2082.55
   782.2 2083.82   807.3 2082.13   843.1 2083.78     868 2081.94   885.9  2080.6
     913 2082.07   978.9 2085.71  1042.7 2086.46    1058 2089.83    1079 2098.94
  1100.1 2110.45  1136.2 2133.88  1150.5 2145.76  1182.6 2166.07  1243.9 2192.74
#Mann= 8 ,-1 , 0
       0      .1       0   28.83      .1       0   276.7     .12       0
  319.49     .05       0  597.75     .06       0  728.24      .1       0
     868    .045       0     913      .1       0
#XS Ineff= 2 , 0
          676.63 2093.24
Permanent Ineff=
       F       F
Bank Sta=868,913
XS Rating Curve= 0 ,0
Exp/Cntr=0.3,0.1

Type RM Length L Ch R = 1 ,6078    ,484.8,481.5,480.5
XS GIS Cut Line= 3
2221911.83987963349059.4892796432222493.43714164349453.586588562
2222797.25674397349701.850527734
#Sta/Elev= 30
       0 2097.64    58.6 2093.57    86.4 2090.35   252.8 2083.56   318.6 2082.06
   336.1 2080.12   550.1 2077.61   610.1 2078.62   645.2 2076.98   659.7 2077.28
   676.3 2079.77   697.5 2080.04   709.2 2079.28   723.2 2075.65   738.7 2077.17
   751.4 2075.08   766.6 2076.75   797.7 2075.53   827.6 2074.58   839.8 2076.11
   860.8 2077.85     870 2081.73   875.5 2085.98   886.9 2097.66   903.9 2111.67
   930.7 2132.97   958.7 2153.35    1031 2201.67    1052 2219.12  1094.9 2244.48
#Mann= 11 ,-1 , 0
       0      .1       0  155.63      .1       0   213.2      .1       0
  356.39    .055       0  550.96     .05       0  629.51     .06       0
  694.03      .1       0  772.24      .1       0   797.7    .045       0
   839.8      .1       0  922.05     .12       0
#XS Ineff= 2 , 0
          691.34  2089.4
Permanent Ineff=
       F       F
Bank Sta=797.7,839.8
XS Rating Curve= 0 ,0
Exp/Cntr=0.3,0.1

Type RM Length L Ch R = 1 ,5597    ,397.5,402.9,410.2
XS GIS Cut Line= 3
2221609.55267354349484.4589573812222151.42338997349800.808991224
2222620.17343672350076.850433901
#Sta/Elev= 30
       0 2080.34   136.3 2078.82   258.7 2075.05     353 2073.84   604.8 2074.66
   627.5 2076.62   649.7 2075.15   660.8 2070.35   666.5 2069.89   695.1 2073.37
   710.3 2073.21   740.7 2070.38   783.9 2073.58   831.8 2074.49   923.6 2073.26
   950.2 2071.84   965.4 2070.22   992.1 2070.82   999.3 2072.17  1004.4 2073.62
  1014.9 2082.87  1025.2 2089.29  1030.7 2091.17  1040.3  2091.7  1044.6 2093.41
  1060.6 2105.67  1083.4 2120.32  1110.1 2135.17  1140.9 2149.74  1171.4 2161.51
#Mann= 8 ,-1 , 0
       0      .1       0  341.03     .05       0  577.01     .06       0
  709.83      .1       0   950.2    .045       0   999.3     .12       0
 1079.64      .1       0 1118.58     .12       0
#XS Ineff= 2 , 0
           635.8 2080.26
Permanent Ineff=
       F       F
Bank Sta=950.2,999.3
XS Rating Curve= 0 ,0
Exp/Cntr=0.3,0.1

Type RM Length L Ch R = 1 ,5194    ,426.9,437.3,442.6
XS GIS Cut Line= 3
2221496.90960714349684.4893419742221984.75672856350078.586650893
2222345.86788297350437.961588308
#Sta/Elev= 30
       0 2078.93   359.6 2071.07     595 2070.81   621.1 2072.97     639 2071.89
   657.5 2068.95   671.4 2070.01   696.2 2068.45   710.2  2070.5   730.2 2070.38
   759.4 2066.97   774.3 2068.53   784.6  2067.2   803.2 2069.89   848.5 2070.33
   860.1 2067.68   869.4 2066.19   886.9 2066.27   897.2 2067.54   938.1 2069.49
   969.1 2067.02   976.9 2068.13   987.7  2067.6     997 2069.29  1003.2 2074.34
  1021.8 2094.38    1048 2118.67  1085.1 2150.66  1119.4 2175.74  1136.6 2187.13
#Mann= 6 ,-1 , 0
       0     .05       0  574.47     .06       0  676.75      .1       0
  716.54     .12       0   860.1    .045       0   897.2     .12       0
#XS Ineff= 2 , 0
          616.64 2078.47
Permanent Ineff=
       F       F
Bank Sta=860.1,897.2
XS Rating Curve= 0 ,0
Exp/Cntr=0.3,0.1

Type RM Length L Ch R = 1 ,4757    ,428.7,436.8,443.8
XS GIS Cut Line= 5
2221417.33176985 349787.587872292221638.01129358350139.281003546
2221743.58467225 350307.819762462221832.81260911350450.967859225
2222052.71954614350803.309353577
#Sta/Elev= 30
       0 2076.97   459.1 2068.82   516.6 2066.24   609.4 2066.01   707.1 2068.87
     730 2067.79   747.6  2064.6   757.2 2066.35   771.4  2066.5   792.8 2062.83
   802.3 2063.01   818.9 2065.69   856.4 2064.27     869 2065.32   876.9 2063.82
   893.6 2065.97   900.7 2064.78   918.3 2062.22   954.3  2064.6   992.7 2065.65
   996.8  2066.9  1002.4 2071.51  1023.8 2093.51  1047.6 2110.23  1074.1 2124.21
  1104.2 2134.79  1120.6  2136.6  1151.5 2136.63  1174.7 2136.02  1198.1  2132.9
#Mann= 4 ,-1 , 0
       0     .05       0  599.92     .06       0   900.7    .045       0
   954.3      .1       0
#XS Ineff= 2 , 0
           707.4 2071.39
Permanent Ineff=
       F       F
Bank Sta=900.7,954.3
XS Rating Curve= 0 ,0
Exp/Cntr=0.5,0.3