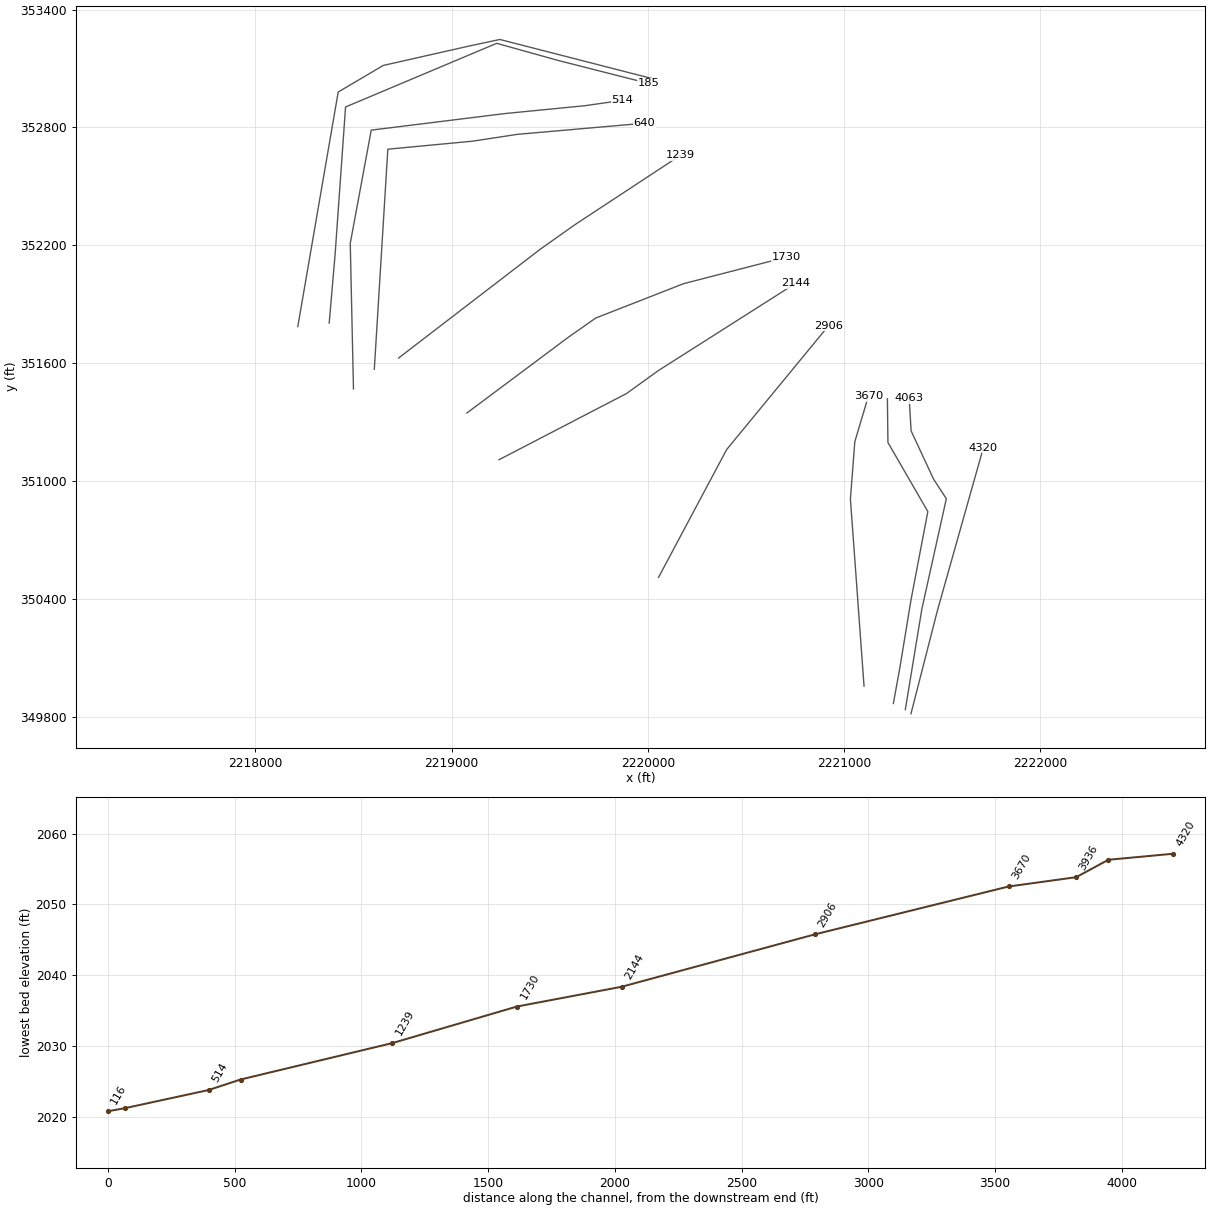
HEC-RAS study MEADOWCK1.prj: MEADOWCK1

--- MEADOWCK1.g01 (geometry) --- (continued)

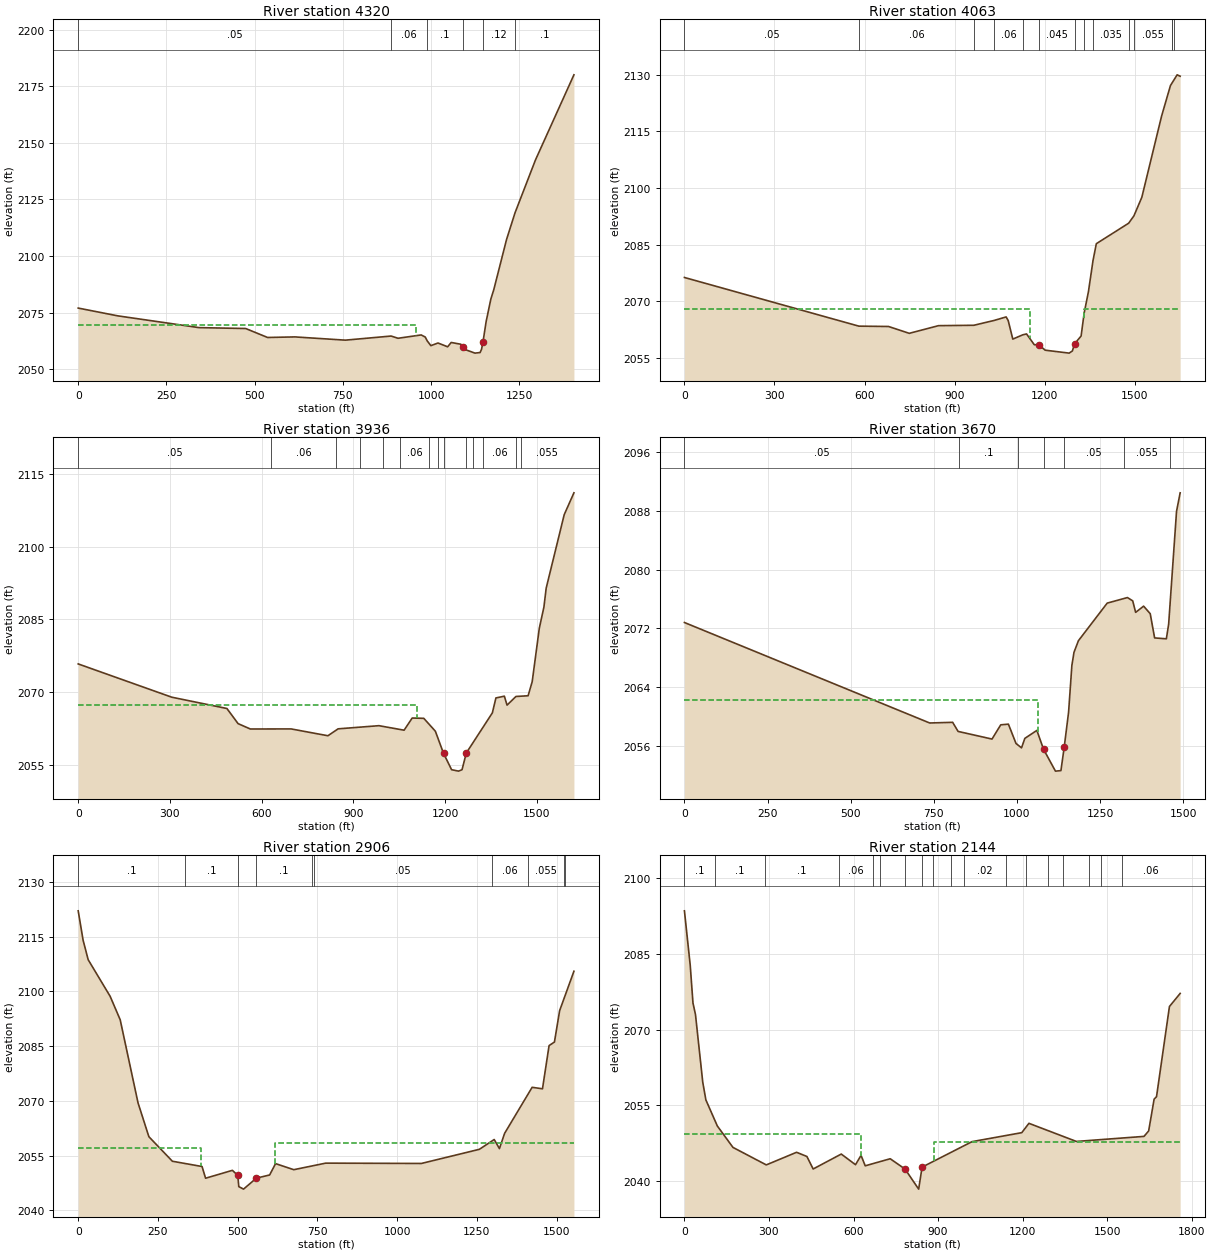
Type RM Length L Ch R = 1 ,4320    ,189.6,256.5,280.4
XS GIS Cut Line= 3
2221340.26831708349815.3253963672221475.23920398350341.436404498
2221709.37237514351170.543281187
#Sta/Elev= 30
       0 2077.04   112.1 2073.61   342.4 2068.41   474.5 2068.02   536.7 2064.06
     614 2064.31     757 2062.88   886.6 2064.69   906.3 2063.71   971.8 2065.18
   983.4 2064.25   989.1 2062.53   999.3 2060.45  1019.5 2061.62  1046.8 2059.95
    1057 2061.86  1084.3 2061.07  1089.92060.074  1097.9 2058.64  1124.3 2057.15
  1138.8 2057.41  1142.9 2058.83  1146.92061.964  1155.9 2071.07  1169.3 2081.04
  1177.5 2085.11  1213.8 2107.34  1237.7 2119.07  1295.7 2142.44  1404.7 2180.04
#Mann= 6 ,-1 , 0
       0     .05       0   886.6     .06       0   989.1      .1       0
  1089.9    .045       0  1146.9     .12       0  1237.7      .1       0
#XS Ineff= 2 , 0
          958.47 2069.67
Permanent Ineff=
       F       F
Bank Sta=1089.9,1146.9
XS Rating Curve= 0 ,0
Exp/Cntr(USF)=0,0
Exp/Cntr=0.3,0.1

Type RM Length L Ch R = 1 ,4063    ,153.3,127.4,131.9
XS GIS Cut Line= 6
2221311.62283098349836.8806111712221395.95252828350349.321757558
2221520.54981127350910.1837409732221455.52600018351009.883176184
2221341.15227495351255.2493160472221331.10956727351422.690844515
#Sta/Elev= 30
       0 2076.32   581.1 2063.44     680 2063.35   749.1 2061.54   846.6 2063.57
   964.2 2063.67  1031.4 2064.94  1071.8 2065.88  1078.7 2064.92    1094 2060.01
  1126.8 2061.13  1139.8 2061.38  1165.7 2058.51  1180.1 2058.56  1201.8 2057.08
  1281.8  2056.3  1292.6 2056.88  1299.7 2058.75  1321.6 2060.83  1331.8 2066.93
    1346 2072.56  1361.3 2080.82  1372.3 2085.26    1480 2090.68  1497.6 2092.64
  1523.9 2097.54  1589.7 2119.02  1619.3 2127.12  1641.5 2129.95  1651.6 2129.58
#Mann= 14 ,-1 , 0
       0     .05       0   581.1     .06       0   964.2      .1       0
  1031.4     .06       0  1126.8      .1       0  1180.1    .045       0
  1299.7      .1       0  1331.8     .06       0  1361.3    .035       0
    1480     .06       0  1497.6    .055       0  1622.9    .055       0
  1625.7     .12       0  1631.6    .055       0
#XS Ineff= 2 , 0
          1150.1  2067.9  1329.7          2067.9
Permanent Ineff=
       F       F
Bank Sta=1180.1,1299.7
XS Rating Curve= 0 ,0
Exp/Cntr=0.5,0.3

Type RM Length L Ch R = 1 ,3936    ,284.4,266.2,242
XS GIS Cut Line= 6
2221250.74496397349867.6666568452221284.85369241350056.204952732
2221340.62728637350395.6523825582221426.28879216350844.807212069
2221222.99587243351196.3481163612221220.29500289351418.933707729
#Sta/Elev= 30
       0 2075.87   306.1 2069.03   486.4 2066.71     523  2063.6     563  2062.5
   696.6 2062.51   816.8 2061.11   850.2 2062.53   983.8 2063.18    1066 2062.25
  1092.5 2064.75  1130.4 2064.69  1168.3 2062.04  1194.9 2057.51  1221.4 2054.13
  1244.1 2053.84  1255.5 2054.13  1269.5 2057.57  1354.7 2065.81  1366.3 2068.88
    1394 2069.24  1402.7  2067.4  1431.8 2069.18  1471.6 2069.33    1485 2072.22
  1508.2 2083.18  1523.4 2087.58  1530.7 2091.43  1589.7 2106.54  1621.5 2111.03
#Mann= 14 ,-1 , 0
       0     .05       0   630.9     .06       0   843.8    .055       0
   922.6     .06       0   996.7     .05       0  1053.1     .06       0
    1147     .05       0  1177.3     .06       0  1194.9    .045       0
  1269.5     .06       0  1290.2     .05       0  1323.8     .06       0
    1433     .05       0  1447.2    .055       0
#XS Ineff= 2 , 0
         1108.35 2067.38
Permanent Ineff=
       F       F
Bank Sta=1194.9,1269.5
XS Rating Curve= 0 ,0
Exp/Cntr=0.5,0.3

Type RM Length L Ch R = 1 ,3670    ,761.3,764,739.1
XS GIS Cut Line= 4
2221101.26276064  349955.97075442221031.81834573350909.095816642
2221054.38785438351200.7625561512221123.83226931351433.401526555
#Sta/Elev= 30
       0 2072.78   737.6 2059.09   806.7 2059.18   823.1 2057.94   925.1  2056.9
   951.4 2058.84   974.4 2058.93   997.3  2056.3  1013.9  2055.7  1023.8 2056.99
    1060 2058.08  1080.1 2055.51  1115.9 2052.53  1132.4  2052.6  1142.3 2055.81
  1155.4 2060.55  1165.3 2066.93  1171.7 2068.72    1185  2070.3  1271.5 2075.42
  1332.4 2076.18  1348.3 2075.73  1357.1 2074.16  1381.1 2075.01    1401 2073.98
  1414.2 2070.68  1449.5 2070.56  1456.4 2072.56  1480.1 2087.93    1491 2090.45
#Mann= 7 ,-1 , 0
       0     .05       0  824.87      .1       0 1004.36     .05       0
  1080.1    .045       0  1142.3     .05       0 1322.33    .055       0
 1461.02      .1       0
#XS Ineff= 2 , 0
         1062.14 2062.25
Permanent Ineff=
       F       F
Bank Sta=1080.1,1142.3
XS Rating Curve= 0 ,0
Exp/Cntr=0.3,0.1

Type RM Length L Ch R = 1 ,2906    ,755.2,762,719.5
XS GIS Cut Line= 3
2220054.38788588350509.7901848112220401.60996047351160.831861734
2220920.70734747351791.040246978
#Sta/Elev= 30
       0 2122.12    15.4 2114.05    31.3 2108.71   100.3 2098.65   131.7 2092.23
   187.6 2069.44   221.6 2060.16   295.3 2053.43   388.3 2051.98   399.4 2048.77
   483.4 2050.93   500.4 2049.54   503.5 2046.47   518.4 2045.78   558.6 2048.79
   600.2 2049.66   618.8 2052.78   675.9 2051.11     776 2052.91    1076 2052.82
  1257.8  2056.7  1304.4 2059.39  1320.7 2056.89    1337 2061.09  1423.3 2073.71
  1455.7  2073.3  1476.4 2085.15  1493.2 2086.13  1509.5 2094.74  1554.3 2105.55
#Mann= 10 ,-1 , 0
       0      .1       0   335.2      .1       0   500.4    .045       0
   558.6      .1       0  731.79      .1       0  739.01     .05       0
 1297.83     .06       0 1411.16    .055       0 1524.48     .06       0
 1527.36      .1       0
#XS Ineff= 2 , 0
          383.93 2056.96  618.45         2058.34
Permanent Ineff=
       F       F
Bank Sta=500.4,558.6
XS Rating Curve= 0 ,0
Exp/Cntr=0.3,0.1

Type RM Length L Ch R = 1 ,2144    ,416.3,413.3,409.8
XS GIS Cut Line= 4
2219241.88787048351108.7486325652219891.19333039351445.554061309
2220052.65166889351561.8737105582220752.30446905352006.318031639
#Sta/Elev= 30
       0 2093.54    20.6 2082.72    30.3 2075.28    39.2 2072.99      65 2059.59
    76.1 2056.07   116.8  2050.9   172.2 2046.66   290.5 2043.19     398 2045.69
   434.6 2044.86   456.8 2042.38   556.6 2045.34   607.1 2043.23   626.8 2045.08
   641.6 2043.01   730.3 2044.41   782.9 2042.37   831.3 2038.39   843.4 2042.75
  1020.7  2047.8  1197.2 2049.58  1222.6 2051.43    1391 2047.84  1630.9 2048.84
  1647.5 2049.92  1666.9 2056.22  1675.4 2056.71  1721.3 2074.58  1759.3 2077.17
#Mann= 18 ,-1 , 0
       0      .1       0  106.86      .1       0  286.96      .1       0
   548.6     .06       0  668.05      .1       0  694.91      .1       0
   782.9    .045       0   843.4      .1       0  882.92    .055       0
  946.45    .035       0  993.75     .02       0 1141.58    .035       0
 1212.26     .02       0  1289.4    .035       0 1345.17     .02       0
 1437.23    .055       0 1478.08    .035       0 1552.67     .06       0
#XS Ineff= 2 , 0
          627.05 2049.35  883.98         2047.68
Permanent Ineff=
       F       F
Bank Sta=782.9,843.4
XS Rating Curve= 0 ,0
Exp/Cntr=0.3,0.1

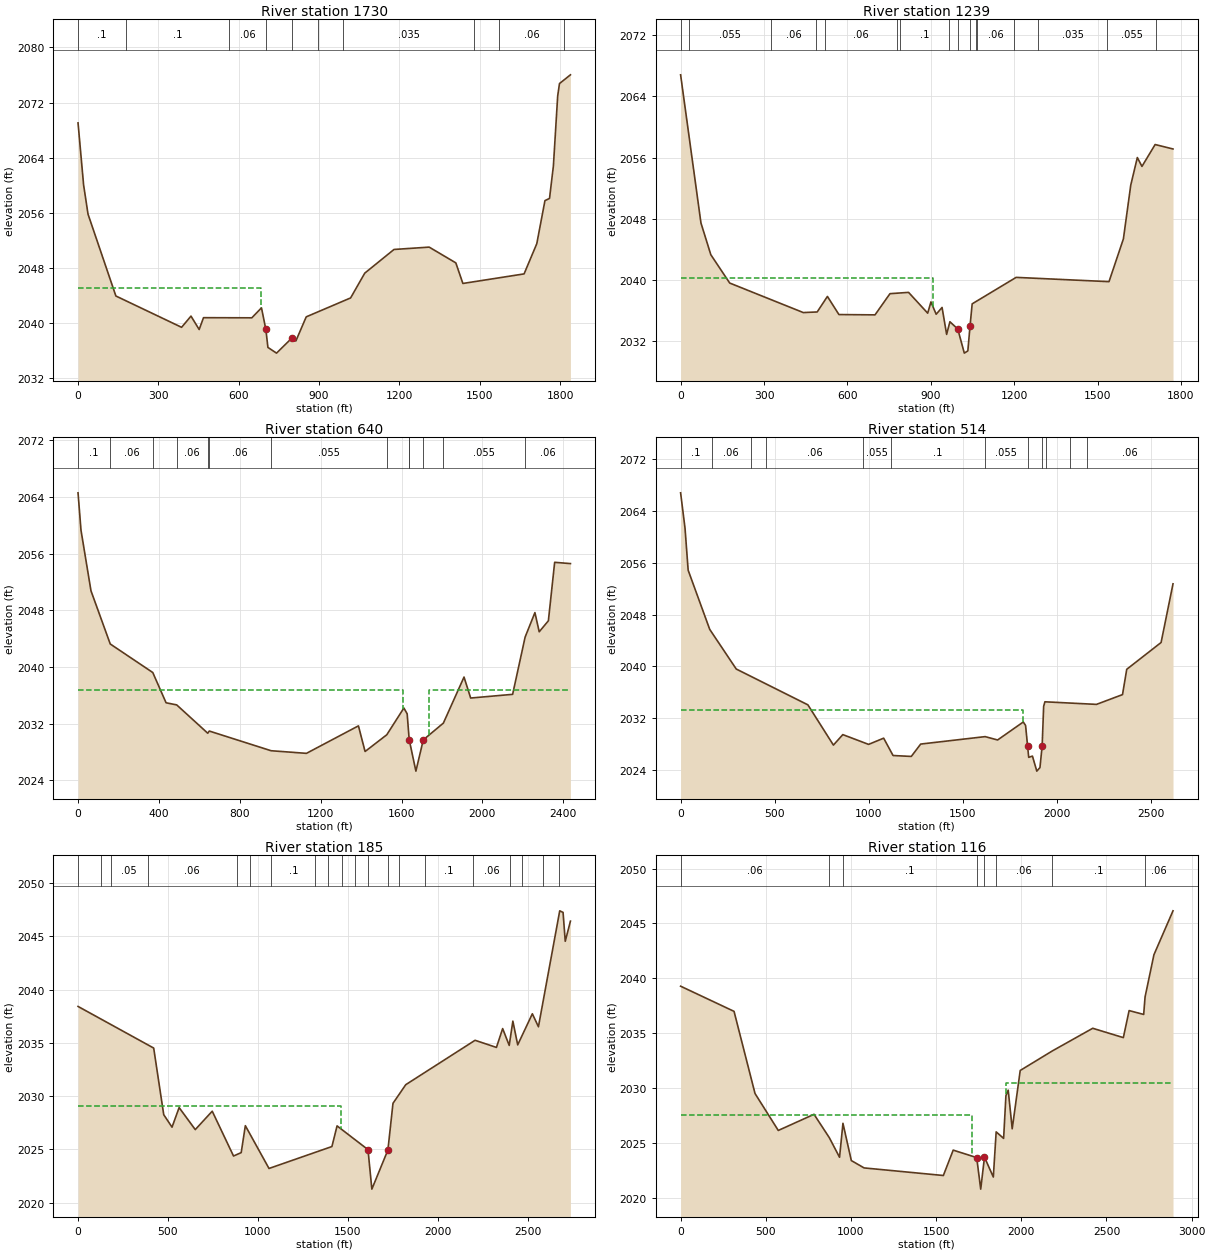
Type RM Length L Ch R = 1 ,1730    ,500.1,491.9,480.9
XS GIS Cut Line= 5
2219078.09292246351346.5562278032219594.75954005 351731.97277981
 2219734.3429223 351829.889578732220182.25967738 352004.88955681
2220707.25961164352140.305952638
#Sta/Elev= 30
       0 2069.05    20.8 2060.03    37.3 2055.79   141.3  2043.9   386.6 2039.35
   421.7 2040.98   452.2 2039.03   468.4 2040.75   648.8 2040.73   684.8 2042.18
   701.1 2039.06   708.9 2036.43     741  2035.6     797 2037.74   813.1 2037.36
   851.9 2040.87  1017.6 2043.62  1070.4 2047.22  1179.6 2050.66  1310.9    2051
  1410.4 2048.71  1436.7 2045.72  1665.2 2047.11  1712.6  2051.5  1743.1 2057.76
  1760.1 2058.07  1774.6 2062.79  1790.6 2072.95  1797.3 2074.76  1838.2 2076.03
#Mann= 10 ,-1 , 0
       0      .1       0  178.41      .1       0  565.43     .06       0
   701.1    .045       0     797    .055       0  897.64     .02       0
     990    .035       0 1477.04    .055       0 1572.17     .06       0
 1815.47    .055       0
#XS Ineff= 2 , 0
          683.64 2045.08
Permanent Ineff=
       F       F
Bank Sta=701.1,797
XS Rating Curve= 0 ,0
Exp/Cntr=0.3,0.1

Type RM Length L Ch R = 1 ,1239    ,611.8,598.7,581.6
XS GIS Cut Line= 4
2218729.73502339351626.1098025592219453.69322114352181.665449977
2219630.77652839 352306.665199982220167.23510113352659.095925555
#Sta/Elev= 30
       0 2066.81    73.2 2047.45   108.7  2043.3   176.6  2039.6   441.3 2035.74
   491.3 2035.82   528.1 2037.85   569.5 2035.48   699.3 2035.44   753.1 2038.21
     820 2038.38   888.8 2035.66   900.5 2037.13   919.3 2035.52   940.5 2036.41
   956.9 2032.89   968.7 2034.54     997 2033.59  1020.5 2030.44  1033.2 2030.73
  1041.2 2034.02  1048.8 2036.88    1207 2040.34    1541 2039.78  1592.8 2045.37
  1619.2 2052.39  1642.9    2056  1659.5 2054.84  1706.9  2057.7  1771.2 2057.12
#Mann= 16 ,-1 , 0
       0      .1       0   28.54    .055       0  326.66     .06       0
  488.35    .055       0  520.77     .06       0   778.1      .1       0
  790.31      .1       0  964.01      .1       0     997    .045       0
  1041.2      .1       0 1061.66      .1       0 1065.79     .06       0
 1198.53    .055       0  1284.3    .035       0 1535.49    .055       0
  1708.9     .06       0
#XS Ineff= 2 , 0
          907.75 2040.25
Permanent Ineff=
       F       F
Bank Sta=997,1041.2
XS Rating Curve= 0 ,0
Exp/Cntr=0.5,0.3

Type RM Length L Ch R = 1 ,640     ,135.2,125.8,130.3
XS GIS Cut Line= 6
 2218606.3814501351569.3161304332218675.28159037352689.351762279
2219107.04988556352730.1318727282219334.48020497352764.853916138
2219928.89346158 352816.914937162219981.43721128352821.359583599
#Sta/Elev= 30
       0 2064.59    14.7  2059.3      64 2050.76   159.3 2043.25   369.7 2039.22
   435.4 2034.95     488 2034.65   641.6 2030.65   649.1 2030.96   954.8 2028.18
  1129.7 2027.81  1386.8 2031.69  1419.7 2028.07  1526.9 2030.43  1611.6 2034.21
  1627.8 2033.39  1637.5 2029.87  1637.8 2029.75    1671  2025.3  1707.5 2029.71
  1806.9 2032.08    1909 2038.58  1941.9 2035.62  2149.4 2036.14  2211.2 2044.22
  2259.7 2047.68  2280.9 2044.97  2326.3 2046.53  2357.3 2054.78  2435.3  2054.6
#Mann= 13 ,-1 , 0
       0      .1       0   159.3     .06       0   369.7    .055       0
     488     .06       0   641.6    .055       0   649.1     .06       0
   954.8    .055       0  1526.9    .035       0  1637.5    .055       0
  1637.8    .045       0  1707.5    .055       0  1806.9    .055       0
  2211.2     .06       0
#XS Ineff= 2 , 0
          1607.8  2036.7  1737.5          2036.7
Permanent Ineff=
       F       F
Bank Sta=1637.8,1707.5
XS Rating Curve= 0 ,0
Exp/Cntr=0.5,0.3

Type RM Length L Ch R = 1 ,514     ,310.3,329.1,326.7
XS GIS Cut Line= 6
2218500.19521955 351468.674005992218483.82626604352210.247518638
2218590.74088221 352786.405520872219273.57908006352870.945600044
2219681.68191046352910.9806040372219870.80131081352938.222663894
#Sta/Elev= 30
       0 2066.81    23.5 2061.34    40.1 2054.86   154.7 2045.72   295.8 2039.59
   676.5 2034.06   812.2 2027.84   862.1 2029.46   999.1 2027.95  1079.2 2028.91
  1129.2 2026.23    1226 2026.09    1276    2028  1618.6 2029.15  1684.8 2028.63
  1821.3 2031.41  1833.5 2030.87  1844.3 2027.65  1850.1 2025.95    1870 2026.14
  1893.1 2023.82  1909.9 2024.37  1921.6 2027.73  1929.5 2033.82  1936.2 2034.53
  2210.3 2034.13  2348.6 2035.64  2371.1 2039.55  2553.7 2043.69    2617 2052.75
#Mann= 12 ,-1 , 0
       0      .1       0   164.7     .06       0   371.6    .055       0
     454     .06       0   969.2    .055       0  1115.9      .1       0
  1618.6    .055       0  1844.3    .045       0  1921.6     .06       0
  1942.8      .1       0  2072.1    .055       0    2160     .06       0
#XS Ineff= 2 , 0
         1821.73 2033.25
Permanent Ineff=
       F       F
Bank Sta=1844.3,1921.6
XS Rating Curve= 0 ,0
Exp/Cntr=0.5,0.3

Type RM Length L Ch R = 1 ,185     ,72.8,68.8,89.9
XS GIS Cut Line= 6
2218376.51510534351804.3959613352218406.73037204352155.042477722
2218459.86542837352904.2463338942219229.91129338353228.270202346
2219545.84030996353140.340811264 2220003.6047329353024.021162014
#Sta/Elev= 30
       0 2038.43   420.8 2034.52   476.7 2028.26   522.8 2027.09   562.3 2028.93
   652.1 2026.86   746.4 2028.59   864.9 2024.38   907.6  2024.7   930.6 2027.23
  1062.2 2023.21  1412.1 2025.27  1440.8 2027.21  1612.8 2024.98  1634.3 2021.27
  1723.5 2024.94  1751.8 2029.33  1822.8 2031.08  2208.4 2035.25  2327.2 2034.58
  2361.8 2036.35  2398.3 2034.77  2418.6 2037.05  2445.5 2034.82    2527 2037.74
  2560.8 2036.52  2679.3 2047.41  2697.8 2047.26    2710 2044.55  2738.8 2046.44
#Mann= 20 ,-1 , 0
       0      .1       0  125.77     .06       0  181.46     .05       0
  386.54     .06       0  882.36     .05       0  957.25    .055       0
 1075.84      .1       0 1320.42      .1       0 1389.94      .1       0
 1467.73      .1       0 1542.78      .1       0  1612.8    .045       0
  1723.5      .1       0 1784.32     .06       0 1930.25      .1       0
 2197.58     .06       0 2401.96      .1       0 2469.94     .06       0
 2585.04    .055       0 2676.12     .06       0
#XS Ineff= 2 , 0
          1461.8 2029.08
Permanent Ineff=
       F       F
Bank Sta=1612.8,1723.5
XS Rating Curve= 0 ,0
Exp/Cntr=0.3,0.1

Type RM Length L Ch R = 1 ,116     ,,,
XS GIS Cut Line= 6
2218216.60826362351786.6152814132218422.42135673352980.331221422
2218651.75594619353115.5798254632219081.02325466353212.605997927
2219245.67372915353247.888242459 2220024.8232959353047.955523442
#Sta/Elev= 30
       0 2039.29   313.7    2037   436.9 2029.52   573.4 2026.16   783.2 2027.63
   873.1  2025.5     933 2023.72     953 2026.81  1002.2 2023.42  1077.2 2022.75
  1542.4 2022.06  1600.2 2024.37  1738.2 2023.69  1761.7 2020.82  1783.9 2023.73
  1835.7 2021.92  1852.4 2026.03  1896.2 2025.44  1909.7 2029.33  1923.1 2029.83
  1946.6 2026.31  1993.6 2031.62  2182.4  2033.4  2419.2 2035.46    2599 2034.61
  2632.9 2037.07  2718.4 2036.72  2726.5 2038.31  2778.5 2042.15  2890.5 2046.15
#Mann= 8 ,-1 , 0
       0     .06       0   873.1    .055       0     953      .1       0
  1738.2    .045       0  1783.9      .1       0  1852.4     .06       0
  2182.4      .1       0  2726.5     .06       0
#XS Ineff= 2 , 0
         1710.48 2027.59 1912.97         2030.52
Permanent Ineff=
       F       F
Bank Sta=1738.2,1783.9
XS Rating Curve= 0 ,0
Exp/Cntr(USF)=0,0
Exp/Cntr=0.3,0.1
LCMann Table=0

Chan Stop Cuts=-1
Use User Specified Reach Order=0
Composite Channel Slope=5